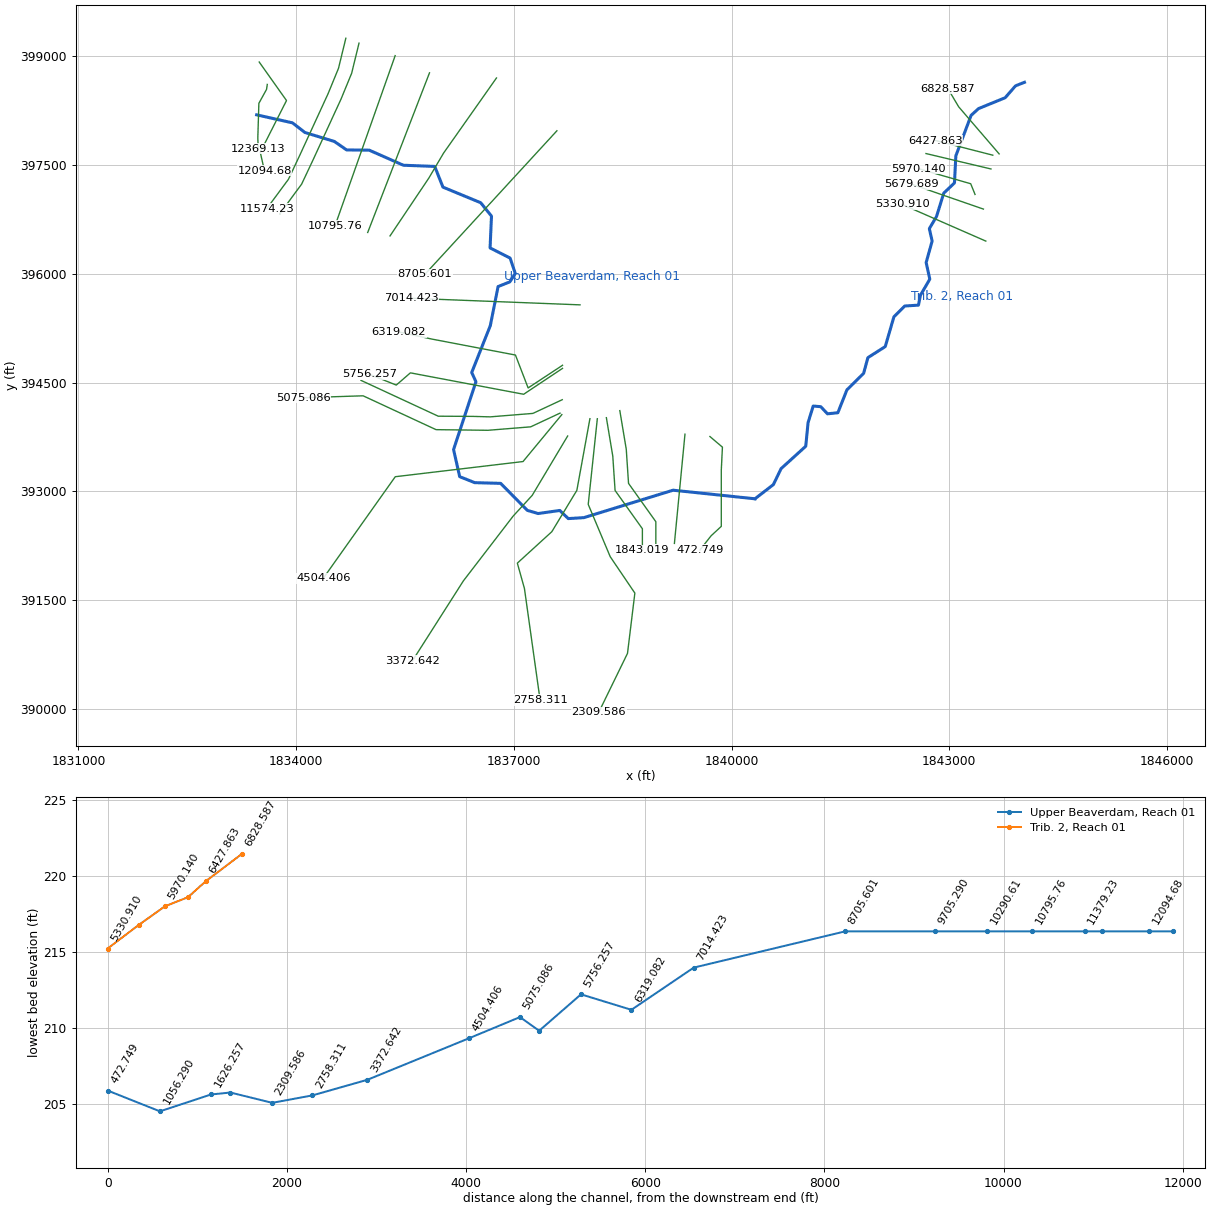
--- gum_limited.prj (project) ---

Proj Title=Gum Swamp
Current Plan=p01
Default Exp/Contr=.3,.1
English Units
Geom File=g02
Geom File=g01
Flow File=f01
Plan File=p01
Y Axis Title=Elevation
X Axis Title(PF)=Main Channel Distance
X Axis Title(XS)=Station
BEGIN DESCRIPTION:
Approximate Study of Gum Swamp
END DESCRIPTION:

--- gum_limited.p01 (plan) ---

Plan Title=Plan 01
Version=September 1998 Version 2.2
Short Identifier=Plan 01
Geom File=g02
Flow File=f01
Interactive Comp Mode
Subcritical Flow
K Sum by GR= 0
Std Step Tol= 0.01
Critical Tol= 0.01
Num of Std Step Trials= 20
Max Error Tol= 0.3
Flow Tol Ratio= 0.001
Log Output Level= 0
Friction Slope Method= 1
Parabolic Critical Depth
Global Vel Dist= 0 , 0 , 0
Global Log Level= 0
Encroach Param=-1 ,0,0, 2
Encroach River=Gum Swamp
Encroach Reach=Reach 01
Encroach Node=56146.35
       4      .7
Encroach Node=55715.47
       4      .7
Encroach Node=54913.09
       4      .7
Encroach Node=54413.84
       4      .7
Encroach Node=53529.10
       4      .7
Encroach Node=52578.30
       4      .7
Encroach Node=51804.38
       1  984.16 1127.88
Encroach Node=51706.27
       1  984.16 1127.88
Encroach Node=51657.32
       1  984.16 1127.88
Encroach Node=51231.95
       4      .7
Encroach Node=50886.07
       4      .7
Encroach Node=50341.72
       4      .7
Encroach Node=49454.01
       4      .7
Encroach Node=49021.30
       4      .7
Encroach Node=48514.24
       4      .7
Encroach Node=47983.48
       4      .7
Encroach Node=47150.46
       1    1227    1420
Encroach Node=46448.20
       1 1403.76 1607.61
Encroach Node=46329.17
       1 1403.76 1607.61
Encroach Node=46217.82
       1 1403.76 1607.61
Encroach Node=46024.32
       4      .7
Encroach Node=45018.92
       4      .7
Encroach Node=44090.86
       4      .7
Encroach Node=43843.40
       4      .7
Encroach Node=43384.39
       4      .7
Encroach Node=42971.19
       4      .7
Encroach Node=42298.41
       4      .7
Encroach Node=41484.61
       4      .7
Encroach Node=40470.89
       4      .7
Encroach Node=39840.25
       4      .7
Encroach Node=38842.49
       4      .7
Encroach Node=38023.16
       4      .7
Encroach Node=37601.33
       4      .7
Encroach Node=36917.14
       4      .7
Encroach Node=36277.55
       4      .7
Encroach Node=35243.74
       4      .7
Encroach Node=34630.08
       4      .7
Encroach Node=33946.92
       4      .7
Encroach Node=33037.82
       4      .7
Encroach Node=32020.60
       4      .7
Encroach Node=31357.68
       4      .7
Encroach Node=30580.02
       4      .7
Encroach Node=29957.96
       4      .7
Encroach Node=29308.58
       4      .7
Encroach Node=29253.65
       4      .7
Encroach Node=29207.37
       4      .7
Encroach Node=28801.93
       4      .7
Encroach Node=28165.00
       4      .7
Encroach Node=27053.20
       4      .7
Encroach Node=25965.19
       4      .7
Encroach Node=25315.44
       4      .7
Encroach Node=24673.87
       4      .7
Encroach Node=23693.31
       4      .7
Encroach Node=22171.62
       4      .7
Encroach Node=20876.17
       4       2
Encroach Node=20239.78
       4       3
Encroach Node=19112.35
       4     1.8
Encroach Node=18440.30
       4     1.6
Encroach Node=16996.56
       4       2
Encroach Node=12863.95
       4      .7
Encroach Node=12808.44
       1    1335    1509
Encroach Node=12765.25
       1    1335    1509
Encroach Node=12563.38
       1 1365.73 1558.73
Encroach Node=12122.96
       4      .7
Encroach Node=11652.89
       4      .7
Encroach Node=11500.32
       4      .7
Encroach Node=11008.94
       4      .7
Encroach Node=10111.95
       4       1
Encroach Node=9119.055
       4     1.5
Encroach Node=7985.959
       4     1.5
Encroach Node=7683.269
       4       2
Encroach Node=6889.063
       4     2.2
Encroach Node=6535.935
       4     1.7
Encroach Node=5960.443
       4       2
Encroach Node=5017.899
       1   953.4 1055.77
Encroach Node=4945.23
       1   953.4 1055.77
Encroach Node=4872.627
       1   953.4 1055.77
Encroach Node=4392.048
       4      .7
Encroach Node=4036.102
       4      .7
Encroach Node=3653.810
       1  1714.5  1814.5
Encroach Node=3562.55
       1  1714.5  1814.5
Encroach Node=3371.178
       1  1714.5  1814.5
Encroach Node=2708.859
       4      .7
Encroach Node=2236.808
       4      .7
Encroach Node=1407.654
       4      .7
Encroach Node=777.945
       4      .7
Encroach Node=278.122
       4      .7
Encroach Node=0.282
       1  711.27 1054.29
Encroach River=Upper Beaverdam
Encroach Reach=Reach 01
Encroach Node=12369.13
       4      .7
Encroach Node=12094.68
       4      .7
Encroach Node=11574.23
       4      .7
Encroach Node=11475.16
       4      .7
Encroach Node=11379.23
       4      .7
Encroach Node=10795.76
       4      .7
Encroach Node=10290.61
       4      .7
Encroach Node=9705.290
       4      .7
Encroach Node=8705.601
       4      .7
Encroach Node=7014.423
       4      .7
Encroach Node=6319.082
       4      .7
Encroach Node=5756.257
       4      .7
Encroach Node=5289.573
       4      .7
Encroach Node=5075.086
       4      .7
Encroach Node=4504.406
       4      .7
Encroach Node=3372.642
       4      .7
Encroach Node=2758.311
       4      .7
Encroach River=Trib. 2
Encroach Reach=Reach 01
Encroach Node=6828.587
       4      .7
Encroach Node=6427.863
       4      .7
Encroach Node=6227.342
       4      .7
Encroach Node=5970.140
       4      .7
Encroach Node=5679.689
       4      .7
Encroach Node=5330.910
       4      .7
Encroach Node=4815.267
       4      .7
Encroach Node=4012.392
       4      .7
Encroach Node=3553.549
       4      .7
Encroach Node=3178.985
       1 1433.71 1590.94
Encroach Node=3062.70
       1 1433.71 1590.94
Encroach Node=2979.742
       1 1433.71 1590.94
Encroach Node=2474.057
       4      .7

--- gum_limited.f01 (steady flow) ---

Flow Title=Gum Swamp Flow Data
Version=September 1998 Version 2.2
Number of Profiles= 2
Profile Names=100yr,floodway
River Rch & RM=Gum Swamp,Reach 01        ,56146.35
    1921    1921
River Rch & RM=Gum Swamp,Reach 01        ,25965.19
    2307    2307
River Rch & RM=Gum Swamp,Reach 01        ,15314.28
    2422    2422
River Rch & RM=Trib. 2,Reach 01        ,6828.587
     252     252
River Rch & RM=Upper Beaverdam,Reach 01        ,12369.13
     559     559
River Rch & RM=Upper Beaverdam,Reach 01        ,10795.76
     666     666
Boundary for River Rch & Prof#=Gum Swamp,Reach 01        , 1
Up Type= 0
Dn Type= 1
Dn Known WS=189.06
Boundary for River Rch & Prof#=Gum Swamp,Reach 01        , 2
Up Type= 0
Dn Type= 3
Dn Slope=.00133
Boundary for River Rch & Prof#=Trib. 2,Reach 01        , 1
Up Type= 0
Dn Type= 1
Dn Known WS=210.36
Boundary for River Rch & Prof#=Trib. 2,Reach 01        , 2
Up Type= 0
Dn Type= 3
Dn Slope=.000012
Boundary for River Rch & Prof#=Upper Beaverdam,Reach 01        , 1
Up Type= 0
Dn Type= 1
Dn Known WS=210.36
Boundary for River Rch & Prof#=Upper Beaverdam,Reach 01        , 2
Up Type= 0
Dn Type= 3
Dn Slope=.00012
DSS Import GetInterval= 0
DSS Import GetPeak= 0
DSS Import FillOption= 0

--- gum_limited.g02 (geometry) ---

Geom Title=Modified Geometry
Version=September 1998 Version 2.2

River Reach=Upper Beaverdam ,Reach 01
Reach XY= 30
      1833455.13      398189.727     1833948.531      398079.361
     1834120.572      397946.273      1834526.33      397822.923
     1834695.125      397706.064     1835006.747      397702.818
     1835477.426       397495.07     1835909.152       397478.84
     1836022.764      397193.187     1836542.134      396978.947
     1836691.453      396793.921     1836671.976      396355.703
     1836947.891      396216.122     1837019.305      396005.128
     1836944.645       395888.27     1836782.342      395823.349
     1836675.222      395284.503     1836418.783      394638.537
     1836477.212       394511.94     1836168.837      393577.075
     1836253.234      393203.778     1836460.982      393121.003
     1836818.049      393111.265     1837184.854      392739.591
     1837334.173      392695.769      1837632.81      392737.968
     1837749.668      392625.979     1837963.908      392638.963
     1839194.165      393017.129     1840321.629      392898.851

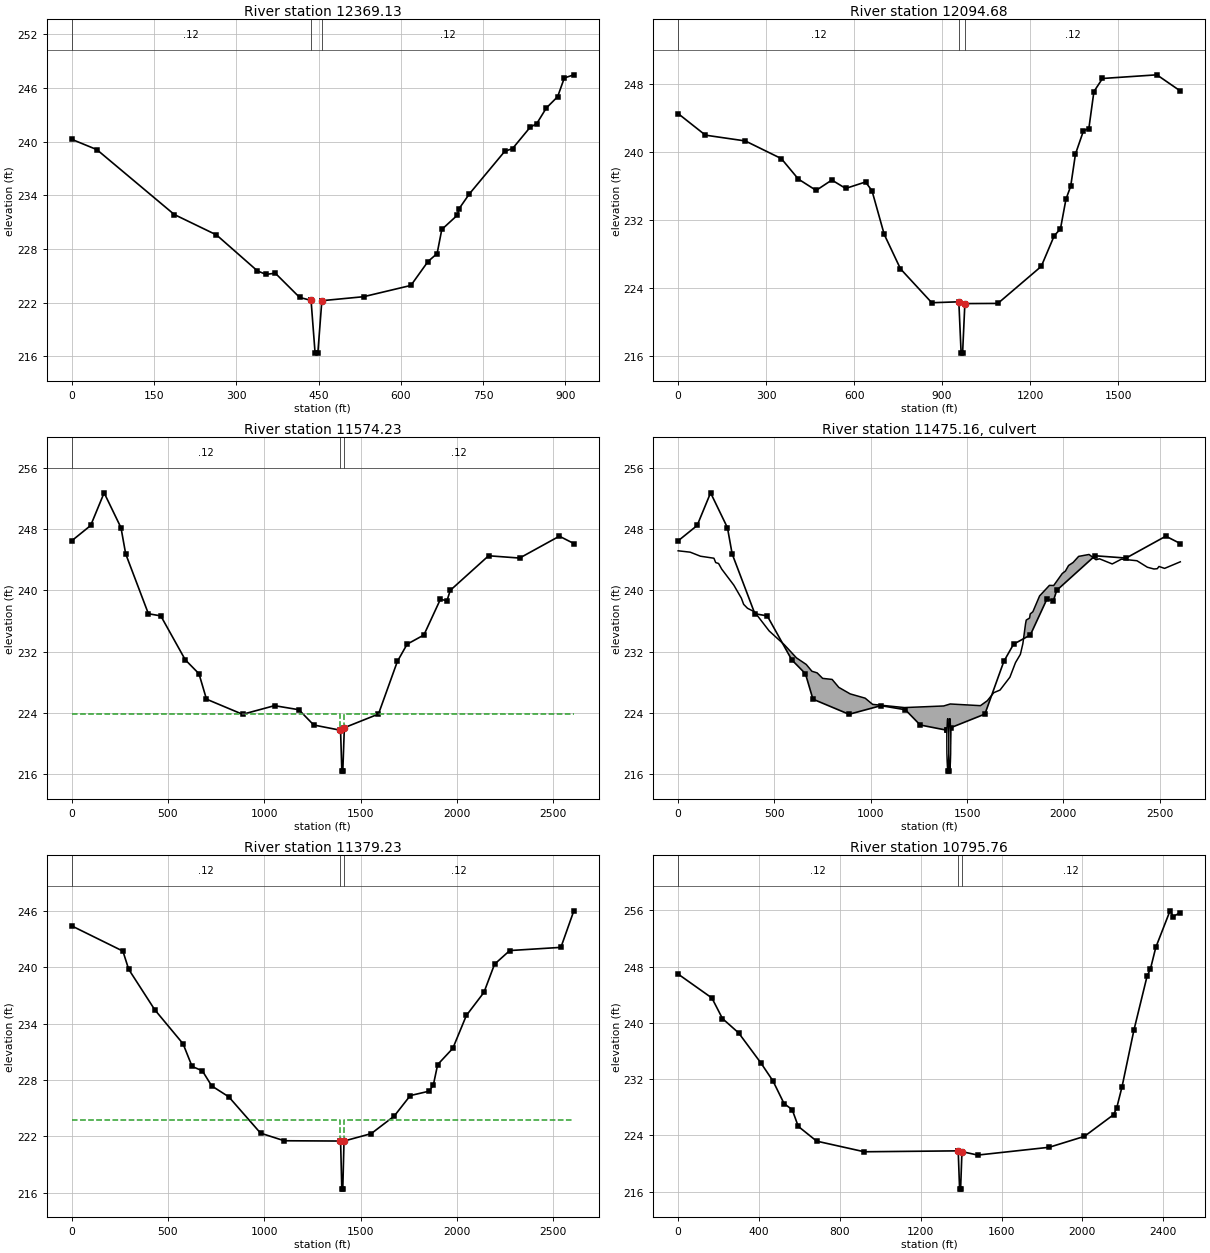
Type RM Length L Ch R = 1 ,12369.13,322.48,274.45,218.99
XS GIS Cut Line= 5
     1833601.627      398608.562     1833591.985      398541.067
     1833485.921      398348.223     1833471.457      397875.756
     1833476.279      397721.481
#Sta/Elev= 30
       0  240.25   45.83   239.1  187.04  231.85     264  229.57  338.65  225.55
  354.34  225.16  371.12   225.3  415.54  222.59  435.69  222.27  436.34  222.27
  443.71  216.37  448.71  216.37  456.03  222.23  456.74  222.23     532  222.67
  618.33  223.93  649.47   226.6  666.11  227.49  674.63  230.18  703.23  231.79
   705.6  232.45  724.99  234.16  789.42  238.91  803.54  239.21  835.48  241.58
  847.68     242   865.1  243.74  885.79  245.01  897.94   247.1  915.31  247.45
#Mann= 3 , 0 , 0
       0     .12       0  435.69    .055       0  456.74     .12       0
Bank Sta=435.69,456.74
Exp/Cntr=.3,.1

Type RM Length L Ch R = 1 ,12094.68,490.89,520.45,501.31
XS GIS Cut Line= 4
     1833490.742      398917.112     1833866.787      398386.792
     1833505.205       397673.27     1833563.058      397417.751
#Sta/Elev= 30
       0  244.56   93.12  242.02  228.98  241.34  351.87  239.26  409.99  236.85
  470.53  235.52  524.09  236.74   571.2  235.75  638.91  236.51  660.92  235.48
  702.65  230.34  758.02  226.29  864.77   222.3  957.01  222.41  964.79  216.37
  969.79  216.37  977.56   222.2 1090.05  222.22 1238.04  226.58 1282.28  230.19
 1303.39  230.99  1322.2  234.48 1338.38  236.02  1354.6   239.8 1381.97  242.54
 1400.22   242.8 1417.51  247.15 1446.74  248.69 1632.09  249.12 1712.01  247.22
#Mann= 3 , 0 , 0
       0     .12       0  957.01    .055       0  977.56     .12       0
Bank Sta=957.01,977.56
Exp/Cntr=.5,.3

Type RM Length L Ch R = 1 ,11574.23,195.99,195.01,198.9
XS GIS Cut Line= 6
     1834684.289        399244.7     1834583.046      398830.085
     1834438.413      398478.145     1834052.725      397639.275
     1833893.629      397301.798     1833594.721      396896.826
#Sta/Elev= 30
    -.08  246.48   98.69  248.49  168.48  252.76  256.02   248.2  280.39  244.78
  398.31  236.95  462.64  236.67  589.65  230.93  660.95   229.1  699.81  225.78
  887.15   223.8 1053.05  224.93 1179.41   224.4 1256.69   222.4 1394.67  221.72
 1395.87  221.76  1402.6  216.37  1407.6  216.37 1415.53  222.05 1592.62  223.83
 1690.93  230.72 1741.46  232.97 1828.52  234.17    1914  238.83  1948.4  238.66
 1965.49  240.01 2164.35  244.53  2325.5  244.23 2531.73  247.09 2606.94  246.13
#Mann= 3 , 0 , 0
    -.08     .12       0 1394.67    .055       0 1415.53     .12       0
#XS Ineff= 2 , 0
       0 1394.18  223.78 1416.04       0  223.78
Bank Sta=1394.67,1415.53
Exp/Cntr=.5,.3

Type RM Length L Ch R = 2 ,11475.16,,,
BEGIN DESCRIPTION:
SR 1001 (NCDOT # 99)
END DESCRIPTION:
Bridge Culvert--1,0,-1,-1, 0
Deck Dist Width WeirC Skew NumUp NumDn MinLoCord MaxHiCord MaxSubmerge Is_Ogee
79.07,40,2.6,0, 60, 60,224.68,,.95,0,0,0,,
       0   62.73  116.06  185.78  195.07  209.92  226.14  289.04   328.2  340.11
  360.23  396.02  472.55  551.15  614.26     665  694.54  721.57  750.06  799.47
  834.24  893.11  970.97 1009.54 1174.69 1378.44 1412.52 1569.37 1605.16 1638.71
 1671.11 1722.32 1751.42 1776.76  1789.6 1803.32 1807.17 1824.47 1827.94 1841.53
 1876.48 1927.53 1949.65 1994.08 2010.51 2026.94 2050.44 2079.16 2133.25 2169.25
 2187.73 2253.52 2301.53 2381.99 2436.07 2470.27 2487.37 2496.36 2525.43 2607.02
  245.18     245  244.47  244.21  243.64  243.52  242.79  240.69  238.99  238.18
  237.66  237.21   234.7   232.9  231.18  230.32  229.43  229.22   228.5  228.36
  227.32  226.47  225.91   225.1  224.68  224.89  225.15  224.93  225.58  226.63
  226.97  228.65  230.56  231.64  233.03  235.59  236.12  236.39  236.93  237.21
  239.28  240.66  240.64  242.21  242.53  243.26  243.65  244.45   244.7  244.01
  244.13  243.46  244.09  243.88  243.03   242.8  242.84  243.13  242.88  243.74
                                                                                
                                                                                
                                                                                
                                                                                
                                                                                
                                                                                
       0   62.73  116.06  185.78  195.07  209.92  226.14  289.04   328.2  340.11
  360.23  396.02  472.55  551.15  614.26     665  694.54  721.57  750.06  799.47
  834.24  893.11  970.97 1009.54 1174.69 1378.44 1412.52 1569.37 1605.16 1638.71
 1671.11 1722.32 1751.42 1776.76  1789.6 1803.32 1807.17 1824.47 1827.94 1841.53
 1876.48 1927.53 1949.65 1994.08 2010.51 2026.94 2050.44 2079.16 2133.25 2169.25
 2187.73 2253.52 2301.53 2381.99 2436.07 2470.27 2487.37 2496.36 2525.43 2607.02
  245.18     245  244.47  244.21  243.64  243.52  242.79  240.69  238.99  238.18
  237.66  237.21   234.7   232.9  231.18  230.32  229.43  229.22   228.5  228.36
  227.32  226.47  225.91   225.1  224.68  224.89  225.15  224.93  225.58  226.63
  226.97  228.65  230.56  231.64  233.03  235.59  236.12  236.39  236.93  237.21
  239.28  240.66  240.64  242.21  242.53  243.26  243.65  244.45   244.7  244.01
  244.13  243.46  244.09  243.88  243.03   242.8  242.84  243.13  242.88  243.74
                                                                                
                                                                                
                                                                                
                                                                                
                                                                                
                                                                                
Multiple Barrel Culv=3,6.58,9.75,40,.027,.7,1,34,2,216.69,216.67, 2,Culvert #1  , 0 ,79.07
 1399.73 1399.73 1410.48 1410.48
BC Design=,, 0 ,, 0 ,,,,,,

Type RM Length L Ch R = 1 ,11379.23,549.18,583.47,577.79
XS GIS Cut Line= 6
     1834865.925      399177.781     1834764.681      398763.167
     1834620.049      398411.227     1834234.361      397572.356
     1834075.265      397234.879     1833776.357      396829.907
#Sta/Elev= 30
     .08   244.4  266.18  241.71     296  239.78  431.39  235.47  578.53  231.84
  625.33  229.43  678.44  228.97  727.12  227.36  815.55   226.2  980.84  222.33
  1103.8  221.52 1394.18  221.49 1396.24  221.46 1402.61  216.37 1407.61  216.37
 1413.99  221.48 1416.04   221.5  1555.3  222.28 1674.71  224.15 1758.01  226.33
 1855.95   226.8 1877.88  227.47 1900.12  229.63 1978.86  231.36 2049.18  234.86
  2140.5  237.32 2195.55  240.32 2274.33  241.77 2539.96  242.11  2607.1     246
#Mann= 3 , 0 , 0
     .08     .12       0 1394.18    .055       0 1416.04     .12       0
#XS Ineff= 2 , 0
       0 1394.18  223.78 1416.04       0  223.78
Bank Sta=1394.18,1416.04
Exp/Cntr=.5,.3

Type RM Length L Ch R = 1 ,10795.76,538.11,505.15,496.19
XS GIS Cut Line= 2
     1835364.223      399005.258     1834536.144      396662.977
#Sta/Elev= 30
       0  246.94  167.07  243.54   219.5  240.61  299.27  238.58  409.39  234.31
  469.38  231.74  524.12  228.53  564.35  227.67  594.32  225.29  685.46  223.19
  921.04  221.68 1383.78  221.81 1385.68  221.79 1392.46  216.37 1397.46  216.37
 1404.13  221.71 1406.14  221.69 1482.04  221.21 1835.82  222.32 2009.95  223.87
 2154.16  226.95 2169.73  227.91 2196.03  230.92 2254.95  238.98 2320.23  246.67
 2336.57  247.66 2363.06  250.73 2433.49  255.93  2449.5  255.12 2484.35  255.68
#Mann= 3 , 0 , 0
       0     .12       0 1383.78    .055       0 1406.14     .12       0
Bank Sta=1383.78,1406.14
Exp/Cntr=.3,.1

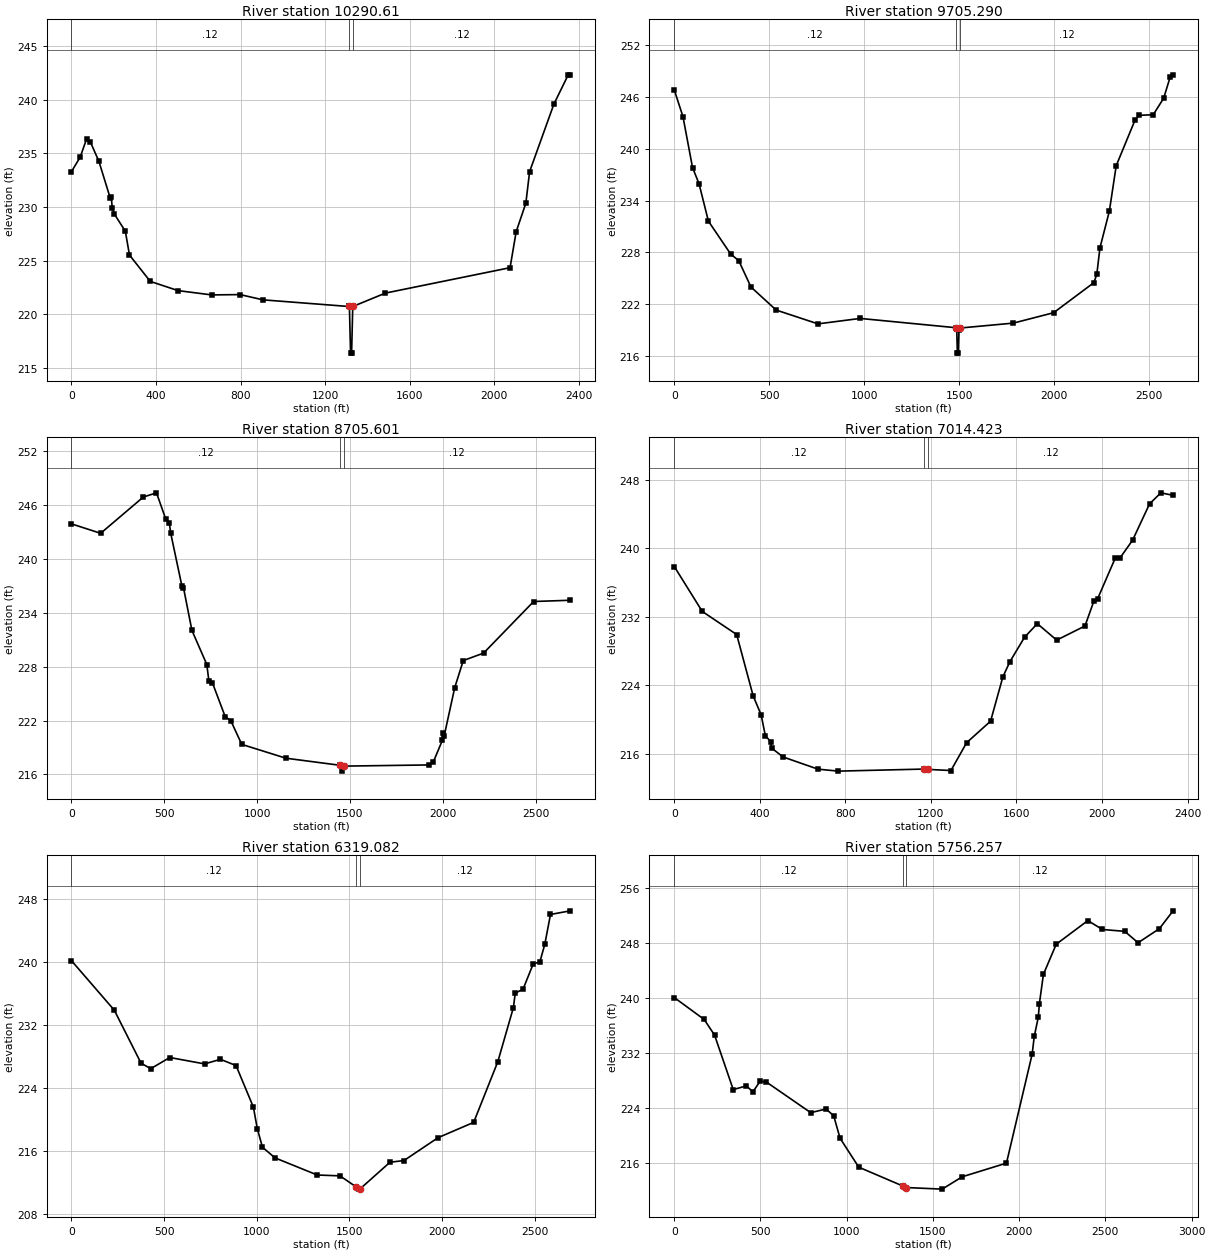
Type RM Length L Ch R = 1 ,10290.61,676.45,585.32,551.23
XS GIS Cut Line= 2
     1835837.411      398768.664     1834985.672       396568.34
#Sta/Elev= 30
       0   233.3   41.32  234.66   71.44  236.35   88.42  236.11  129.66  234.26
   182.6  230.88  187.93  230.95  192.83  229.92  203.11  229.33  254.76  227.74
  274.23  225.52  372.74  223.06  504.47   222.2  663.38   221.8  797.73  221.83
  905.74  221.34 1311.84  220.72 1314.53  220.72 1319.96  216.37 1324.96  216.37
 1330.41  220.73 1333.08  220.74 1484.85  221.97 2074.41  224.34 2103.37   227.7
    2149  230.35 2166.89   233.3 2281.76   239.6 2348.77   242.3 2359.43  242.33
#Mann= 3 , 0 , 0
       0     .12       0 1311.84    .055       0 1333.08     .12       0
Bank Sta=1311.84,1333.08
Exp/Cntr=.3,.1

Type RM Length L Ch R = 1 ,9705.290,996.58,999.69,914.5
XS GIS Cut Line= 4
     1836760.128      398697.686     1836031.242      397662.601
     1835827.945       397317.88     1835293.245      396521.021
#Sta/Elev= 30
       0  246.79   45.78   243.7   96.11  237.82  130.57  235.93  179.76  231.62
  297.53   227.8  339.45  227.06  403.69  224.01  536.21  221.35  756.66  219.75
  978.55  220.38 1480.95  219.31 1486.74  219.19 1490.26  216.37 1495.26  216.37
 1498.55     219 1504.58  219.27 1785.07  219.84 1997.01  221.04 2209.07  224.52
 2224.35   225.5 2240.68  228.53 2290.32  232.78 2326.33  238.03 2424.99  243.28
 2446.89  243.85 2521.25  243.92  2576.2  245.83  2610.4  248.28  2625.8  248.53
#Mann= 3 , 0 , 0
       0     .12       0 1480.95    .055       0 1504.58     .12       0
Bank Sta=1480.95,1504.58
Exp/Cntr=.3,.1

Type RM Length L Ch R = 1 ,8705.601,1551.41,1691.18,1216.06
XS GIS Cut Line= 2
     1837593.008      397970.081     1835774.002      395991.911
#Sta/Elev= 30
       0  243.92  157.21  242.87  386.91  246.91  457.94  247.38  507.58  244.47
  526.85  244.07   534.2  242.92  594.68  237.01  603.32  236.82  648.84  232.05
  729.08  228.25  740.45  226.38  759.51   226.2  828.21  222.43  857.83  222.01
  917.34  219.35 1155.22  217.81 1447.09  217.02 1455.65  216.37 1469.99  216.93
 1927.98  217.06 1950.25  217.44 1997.82  219.79 2002.73  220.63  2007.3  220.25
 2064.62  225.67 2110.62  228.69 2220.03  229.52 2489.77  235.27 2687.37  235.41
#Mann= 3 , 0 , 0
       0     .12       0 1447.09    .055       0 1469.99     .12       0
Bank Sta=1447.09,1469.99
Exp/Cntr=.3,.1

Type RM Length L Ch R = 1 ,7014.423,694.27,695.34,669.2
XS GIS Cut Line= 2
     1837911.335      395571.266     1835580.732      395662.216
#Sta/Elev= 30
       0  237.89  130.89  232.64  291.83  229.94  369.03  222.76  406.21  220.56
  425.81  218.13  450.35  217.43   456.2  216.65  509.25  215.63  671.94  214.21
  767.01  213.98 1165.93  214.22  1186.8  214.18 1293.67  214.05 1366.93   217.3
 1479.02  219.82  1536.3  224.98 1569.11  226.76 1637.96  229.63 1697.47  231.21
 1788.09  229.29 1920.42  230.94 1961.51  233.82 1979.34  234.11 2061.49  238.85
  2085.3  238.93  2143.1  240.97 2222.35  245.21 2275.01   246.5 2332.38  246.21
#Mann= 3 , 0 , 0
       0     .12       0 1165.93    .055       0  1186.8     .12       0
Bank Sta=1165.93,1186.8
Exp/Cntr=.3,.1

Type RM Length L Ch R = 1 ,6319.082,514.85,562.83,524.33
XS GIS Cut Line= 5
     1837670.632      394738.668     1837196.237      394426.261
      1837021.62      394879.693     1835878.762      395097.908
     1835414.359      395197.637
#Sta/Elev= 30
       0  240.15  230.99  233.88  375.71  227.15  428.17  226.47  530.53  227.88
  718.59  227.07  804.06  227.65  888.26  226.86  981.91  221.58 1002.85  218.87
 1030.74  216.51 1098.55  215.16 1326.37  212.99 1449.35  212.88 1534.67  211.51
 1550.28   211.2 1556.21   211.2 1719.17  214.61 1794.47  214.82 1978.48  217.72
 2170.79  219.66 2301.11  227.35 2385.19  234.21 2395.17  236.04 2437.28  236.54
 2491.39   239.7 2528.53  240.04 2554.67  242.23 2585.34  246.01 2692.41  246.47
#Mann= 3 , 0 , 0
       0     .12       0 1534.67    .055       0 1556.21     .12       0
Bank Sta=1534.67,1556.21
Exp/Cntr=.3,.1

Type RM Length L Ch R = 1 ,5756.257,430.29,466.68,484.62
XS GIS Cut Line= 5
     1837670.632      394696.243     1837134.821      394339.109
     1835573.889       394634.21     1835379.342      394465.781
      1835005.53      394615.248
#Sta/Elev= 30
       0  240.05  173.43  236.87  233.79  234.59  341.96  226.68  418.21  227.22
  455.97  226.35  497.43  227.88  531.73  227.82  791.25  223.33  880.38  223.86
  924.55  222.87  961.19  219.62 1069.74  215.41 1324.73  212.68 1344.98  212.45
  1553.5  212.22  1669.3  214.01 1926.24     216 2075.12  231.82 2087.47  234.42
 2110.89   237.2 2117.02  239.15 2140.54  243.43 2214.85   247.8 2397.95  251.23
 2482.76  249.94 2612.07  249.67 2689.29  248.01 2812.88  250.06 2892.42  252.65
#Mann= 3 , 0 , 0
       0     .12       0 1324.73    .055       0 1344.98     .12       0
Bank Sta=1324.73,1344.98
Exp/Cntr=.3,.1

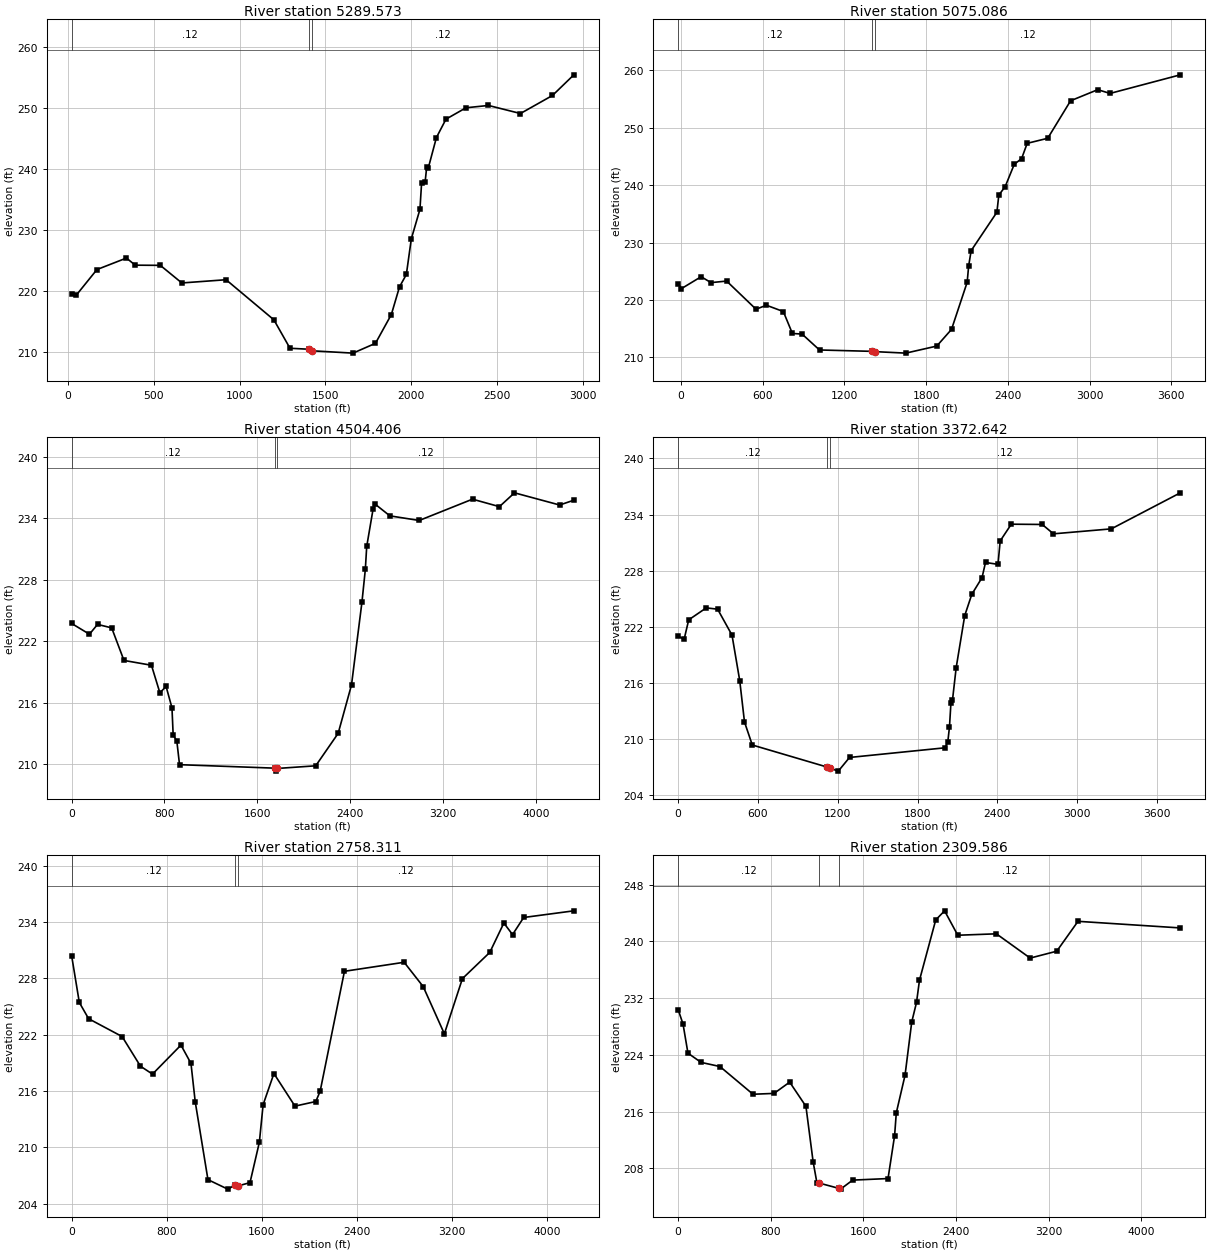
Type RM Length L Ch R = 1 ,5289.573,186.72,214.49,201
XS GIS Cut Line= 6
     1837666.776      394264.272     1837261.803      394075.285
     1836672.308      394027.776     1836437.834      394034.229
     1835958.179      394036.717     1834893.681      394530.397
#Sta/Elev= 30
   21.63  219.49   49.56  219.37  168.93  223.54  340.94  225.43  392.01  224.26
  538.31  224.23  663.58  221.34  921.36  221.87 1199.84  215.29 1293.72  210.62
 1401.93  210.46 1424.02   210.2 1660.87  209.82 1791.78  211.43 1884.32  216.16
 1931.83   220.7 1971.73  222.73 2000.69  228.59 2050.94  233.43 2060.63  237.81
 2080.92  237.87 2090.12  240.32 2100.31  240.29 2146.84  245.21  2202.6  248.23
 2319.04   250.1 2450.01  250.48 2636.59  249.16 2823.08  252.12 2947.58  255.51
#Mann= 3 , 0 , 0
   21.63     .12       0 1401.93    .055       0 1424.02     .12       0
Bank Sta=1401.93,1424.02
Exp/Cntr=.3,.1

Type RM Length L Ch R = 1 ,5075.086,607.33,570.68,642.48
XS GIS Cut Line= 6
      1837635.92      394079.142     1837230.948      393890.155
     1836641.453      393842.645     1835927.324      393851.586
     1834922.294      394317.925     1834095.307       394291.27
#Sta/Elev= 30
  -21.63  222.84    3.19  221.97  147.44  224.04  219.74  223.01  334.75  223.28
  550.47  218.37  626.52  219.07  751.01  217.97  817.51  214.15  888.71  214.04
 1016.68  211.27  1401.9  211.03 1424.03  210.98 1650.29  210.72 1877.67  211.95
 1986.18  214.86 2101.03  223.07 2111.89   225.9  2130.2  228.58 2319.39  235.28
 2333.45  238.27 2379.94  239.73 2446.83  243.63 2500.92  244.63 2541.81  247.29
 2692.66  248.17 2860.67  254.71 3059.86  256.64 3150.37  255.99 3666.28  259.23
#Mann= 3 , 0 , 0
  -21.63     .12       0  1401.9    .055       0 1424.03     .12       0
Bank Sta=1401.9,1424.03
Exp/Cntr=.3,.1

Type RM Length L Ch R = 1 ,4504.406,665.29,1131.76,1349.61
XS GIS Cut Line= 4
     1837661.221      394059.217     1837126.043      393412.034
     1835365.625      393203.082     1834373.105      391803.107
#Sta/Elev= 30
       0  223.74  153.47  222.69  223.16  223.65  345.08  223.31  450.95  220.13
  687.88  219.66  760.55  216.97  814.04  217.59  864.71   215.5  875.03  212.85
  906.37  212.28   929.9  209.95 1753.12  209.61 1764.59  209.32 1770.43  209.58
 2103.72  209.84 2297.19  213.01 2412.24  217.74  2502.3  225.83 2531.43  229.02
 2543.31  231.26 2598.18  234.91 2617.49  235.38 2743.08  234.25 2996.03   233.8
 3455.18  235.88 3687.08  235.15 3817.12   236.5 4206.31  235.31 4328.68  235.78
#Mann= 3 , 0 , 0
       0     .12       0 1753.12    .055       0 1770.43     .12       0
Bank Sta=1753.12,1770.43
Exp/Cntr=.3,.1

Type RM Length L Ch R = 1 ,3372.642,493.98,614.33,577.91
XS GIS Cut Line= 5
     1837740.803      393763.628     1837251.945      392945.075
     1836990.462      392660.855     1836304.246      391767.817
     1835600.696       390664.32
#Sta/Elev= 30
       0  221.02   44.95  220.66   79.54  222.75  211.62  224.03  296.88  223.89
  405.03  221.12  463.08  216.26  498.88  211.84  557.51  209.38 1121.04  207.02
 1139.92  206.91 1203.78  206.59 1288.41  208.05 2004.53  209.08 2026.54  209.65
 2039.58  211.31 2050.41  213.85  2062.2  214.18 2089.91  217.64  2154.3  223.21
 2207.42  225.48 2284.33  227.26 2310.36  228.88 2404.21  228.68 2420.71  231.18
 2504.24  232.97 2736.69  232.94 2821.09  231.94 3255.89  232.47 3774.56  236.32
#Mann= 3 , 0 , 0
       0     .12       0 1121.04    .055       0 1139.92     .12       0
Bank Sta=1121.04,1139.92
Exp/Cntr=.3,.1

Type RM Length L Ch R = 1 ,2758.311,345.03,448.73,747
XS GIS Cut Line= 6
      1838047.76      394002.373     1837867.821      393015.026
     1837523.051      392445.633     1837047.686      392012.058
     1837145.578      391662.359     1837361.113       390126.27
#Sta/Elev= 30
       0  230.41   64.54  225.44  142.68  223.71  424.71  221.81  579.29  218.65
  680.54  217.81  920.05   220.9 1004.33  218.95  1039.9  214.88 1147.22  206.57
 1313.74  205.56 1377.98     206 1399.11   205.9 1501.13  206.25 1579.92  210.55
 1611.47  214.55 1702.45  217.87 1879.59   214.4 2054.91  214.89 2091.69  215.99
 2296.07  228.76 2798.68  229.72 2958.93  227.13 3137.16   222.1 3289.04  227.98
 3519.33  230.77 3637.78   233.9 3711.06  232.67 3804.65  234.49 4226.92   235.2
#Mann= 3 , 0 , 0
       0     .12       0 1377.98    .085       0 1399.11     .12       0
Bank Sta=1377.98,1399.11
Exp/Cntr=.3,.1

Type RM Length L Ch R = 1 ,2309.586,451.69,466.57,506.64
XS GIS Cut Line= 6
     1838149.906      394002.322     1838024.535      392821.746
     1838327.514      392100.863     1838667.061      391599.379
     1838565.671      390768.546     1838170.801      389959.109
#Sta/Elev= 30
       0  230.38   42.61  228.32   84.92  224.23  198.57  222.93  361.12  222.35
   646.8  218.44  828.58  218.56  963.63  220.15 1104.02  216.74 1165.83  208.96
 1199.31  205.92 1214.56  205.94 1388.06  205.18 1403.35  205.07 1507.54  206.34
  1813.1  206.56 1869.98  212.62 1884.44  215.81 1959.92  221.11 2017.94  228.63
 2059.17  231.38  2084.9  234.52  2225.2  243.01 2301.66  244.29 2415.62  240.85
 2748.92  241.05 3040.88  237.63 3270.41   238.6  3453.9  242.81  4337.7  241.88
#Mann= 3 , 0 , 0
       0     .12       0 1214.56    .085       0 1388.06     .12       0
Bank Sta=1214.56,1388.06
Exp/Cntr=.3,.1

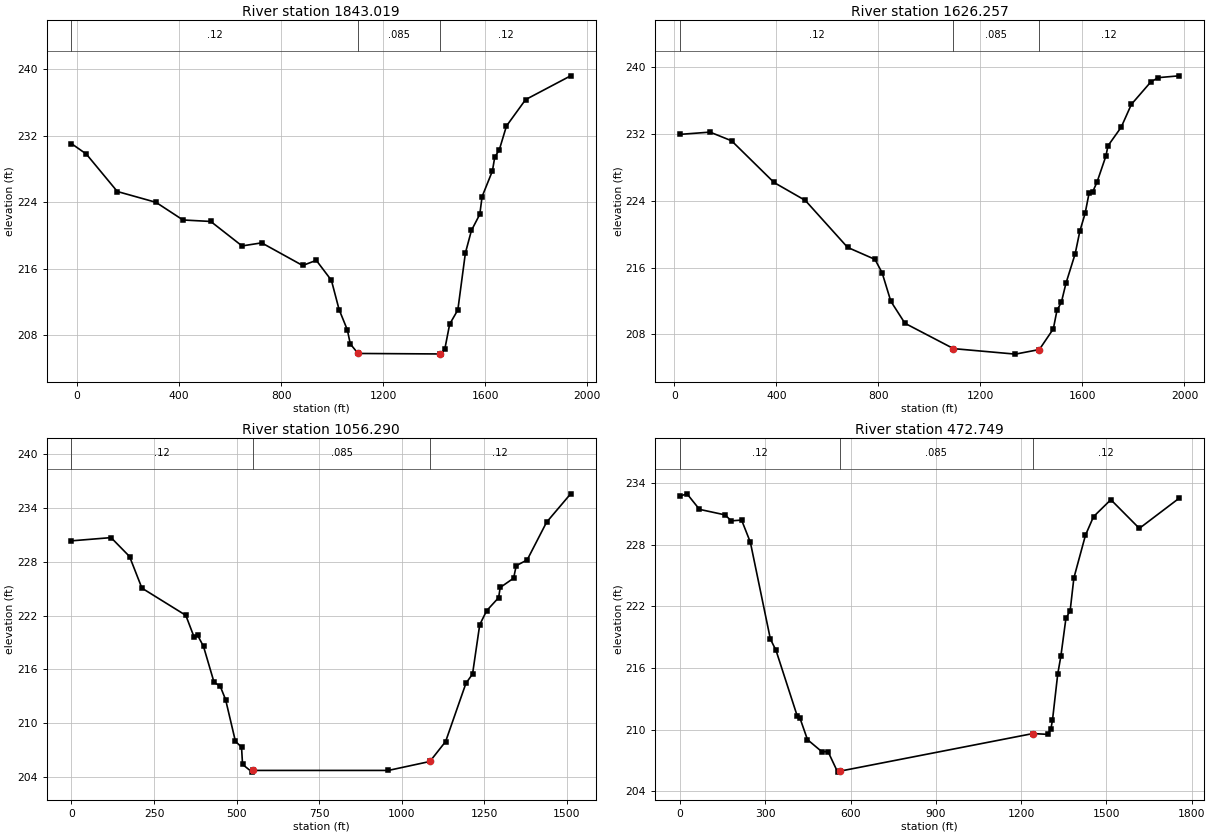
Type RM Length L Ch R = 1 ,1843.019,209.48,216.76,212.41
XS GIS Cut Line= 5
       1838274.5       394016.52     1838363.304      393483.694
     1838394.647      393013.553      1838770.76       392485.95
      1838770.76      392188.194
#Sta/Elev= 30
  -22.02  231.04   36.07  229.79  157.64  225.29  309.19  223.99     415  221.87
  524.08  221.69  646.63  218.75  723.57  219.12   884.3   216.4   937.7  217.02
  996.99  214.62 1027.12  211.11 1059.54  208.66 1071.05  206.98 1101.33  205.83
 1424.24  205.77 1425.83  205.75 1441.92   206.4 1460.68  209.35  1492.7  211.06
 1522.34   217.9 1546.03  220.61 1578.77  222.55 1587.89  224.68 1628.29  227.76
 1637.28  229.39 1655.56  230.33 1683.38  233.16 1758.32  236.33 1935.04  239.19
#Mann= 3 , 0 , 0
  -22.02     .12       0 1101.33    .085       0 1424.24     .12       0
Bank Sta=1101.33,1424.24
Exp/Cntr=.3,.1

Type RM Length L Ch R = 1 ,1626.257,675.33,569.97,495.82
XS GIS Cut Line= 5
     1838459.824       394113.87     1838548.628      393581.044
     1838579.971      393110.903     1838956.084        392583.3
     1838956.084      392285.544
#Sta/Elev= 30
   22.02  231.97  139.97  232.24  224.47   231.2  390.82   226.2  513.47  224.05
  679.22  218.42  786.68  216.98  814.78  215.36  848.76  211.96  904.07  209.32
 1094.49  206.28 1337.15  205.62  1431.1  206.17 1485.93  208.65 1500.42   210.9
 1517.35  211.82 1535.39  214.11 1571.62  217.66 1589.91  220.37 1610.46  222.49
 1626.03  224.92 1640.16  225.08 1657.28  226.25 1692.02  229.37 1700.19   230.6
 1752.03  232.83 1791.94  235.57 1867.63  238.24 1896.93  238.77 1979.08  238.99
#Mann= 3 , 0 , 0
   22.02     .12       0 1094.49    .085       0  1431.1     .12       0
Bank Sta=1094.49,1431.1
Exp/Cntr=.3,.1

Type RM Length L Ch R = 1 ,1056.290,565.95,583.54,605.41
XS GIS Cut Line= 2
     1839357.748      393789.283     1839212.079      392284.032
#Sta/Elev= 30
       0  230.34  119.85   230.7  175.87  228.59  213.32  225.06  346.33  222.02
  371.86  219.55  382.34  219.78  399.97  218.54  431.91  214.54  450.48  214.11
  466.87  212.61  496.57  207.96   515.2  207.29  518.21  205.37  547.29  204.51
  550.47   204.7  960.06   204.7 1085.82   205.7 1133.51  207.93 1195.11  214.44
    1215  215.46 1236.78  220.97 1257.85  222.54 1293.99  223.99 1298.86  225.13
  1339.5  226.17 1347.26  227.56 1380.53  228.21 1439.38  232.42 1512.28  235.59
#Mann= 3 , 0 , 0
       0     .12       0  550.47    .085       0 1085.82     .12       0
Bank Sta=550.47,1085.82
Exp/Cntr=.3,.1

Type RM Length L Ch R = 1 ,472.749 ,234.25,472.75,336.3
XS GIS Cut Line= 6
     1839701.371      393756.804     1839873.756      393610.538
     1839858.085      393291.887     1839858.085      392518.766
     1839717.043      392388.171     1839565.553      392194.891
#Sta/Elev= 30
       0  232.72   24.81  232.94   68.61  231.43  158.91  230.89  180.45  230.31
  216.87  230.39  247.76  228.22  318.07  218.82  337.87  217.72   412.3  211.36
  421.81  211.16  448.58  209.04  499.42  207.86  520.88  207.88  554.83  205.88
  561.93  205.97 1241.51  209.63 1294.61  209.55 1304.88  210.08 1310.58  210.94
 1329.02  215.42 1340.07  217.16 1357.77  220.82 1372.75  221.59 1385.82  224.76
 1426.62  228.92 1454.92  230.72 1515.86  232.37 1616.14  229.58 1756.02  232.51
#Mann= 3 , 0 , 0
       0     .12       0  561.93    .085       0 1241.51     .12       0
Bank Sta=561.93,1241.51
Exp/Cntr=.3,.1

River Reach=Trib. 2         ,Reach 01
Reach XY= 30
      1844035.66      398638.162     1843912.822      398589.364
     1843769.793      398425.301     1843402.964       398275.54
     1843300.319      398182.151     1843089.982      397623.494
     1843071.472      397251.617     1842923.394       397110.27
     1842824.115      396788.874     1842724.836      396621.446
     1842763.538      396450.652     1842681.086      396153.655
     1842731.567      395925.649     1842601.999      395702.691
     1842575.075      395567.234     1842386.613      395555.455
     1842236.853      395406.536     1842117.381      394995.957
     1841878.437      394843.672     1841819.543      394627.445
     1841589.013      394399.439     1841464.493      394084.774
     1841321.463       394069.63     1841228.915      394168.068
     1841124.587      394176.482     1841053.914      393948.476
     1841021.943      393622.873     1840682.037      393314.097
     1840576.027      393094.505     1840326.635      392901.931

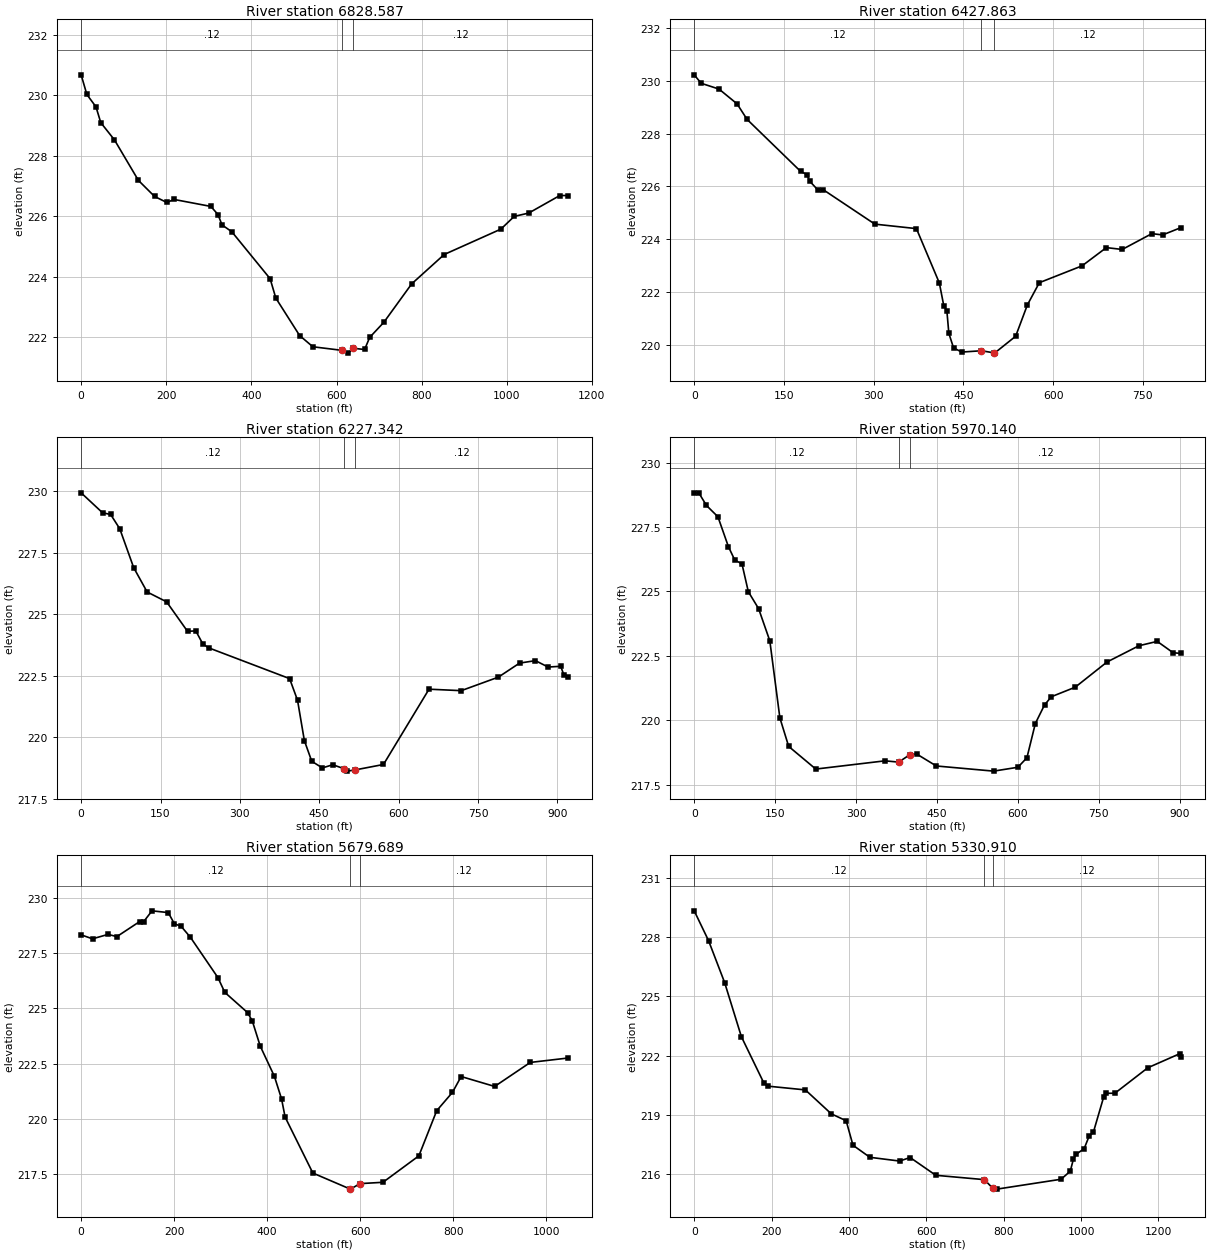
Type RM Length L Ch R = 1 ,6828.587,349.65,400.72,437.1
XS GIS Cut Line= 3
     1843686.682      397651.755     1843129.611      398299.776
     1842981.961      398548.594
#Sta/Elev= 30
       0  230.67   13.44  230.02   34.92  229.61   46.12  229.09   78.25  228.52
  134.56  227.18  172.47  226.65  201.28  226.45  218.39  226.55  304.78  226.32
   321.6  226.05  330.95  225.71  354.18  225.48  444.03  223.93  457.41  223.29
  513.43  222.05  544.48  221.68  613.95  221.56   627.6  221.47  639.43  221.63
  666.01  221.59  677.97  221.99  711.28  222.49  776.65  223.76  852.99  224.73
  986.28  225.57 1017.52  225.99 1051.58   226.1 1124.66  226.68 1143.88  226.68
#Mann= 3 , 0 , 0
       0     .12       0  613.95    .055       0  639.43     .12       0
Bank Sta=613.95,639.43
Exp/Cntr=.3,.1

Type RM Length L Ch R = 1 ,6427.863,198.88,200.52,201.72
XS GIS Cut Line= 2
     1843599.266      397633.733     1842810.911      397835.875
#Sta/Elev= 30
       0  230.23   11.59  229.91   41.45  229.69   71.62  229.13    88.4  228.54
  177.85  226.57  188.41  226.45  192.96   226.2  206.52  225.87  215.36  225.88
  301.97  224.57  371.45   224.4  409.76  222.34  417.17  221.48  422.33  221.29
  425.64  220.43  433.51  219.88  447.13  219.72  480.18  219.77  501.34  219.69
  502.05  219.68  537.33  220.32  556.98  221.51  576.91  222.35  648.43  222.99
  688.95  223.68  715.48  223.61  765.08  224.21   782.9  224.16  813.86  224.44
#Mann= 3 , 0 , 0
       0     .12       0  480.18    .055       0  501.34     .12       0
Bank Sta=480.18,501.34
Exp/Cntr=.3,.1

Type RM Length L Ch R = 1 ,6227.342,258.48,257.2,254.04
XS GIS Cut Line= 2
     1843574.035      397443.738     1842678.797      397656.167
#Sta/Elev= 30
       0  229.93   40.42  229.12   55.76  229.05   73.01  228.47    99.3  226.89
  124.77   225.9  161.55   225.5   201.1   224.3  216.67  224.32  229.93  223.79
   241.1  223.63  393.98  222.38  408.96   221.5  421.89  219.86  435.82  219.02
  455.93  218.75  475.52  218.88  496.73  218.72  503.34  218.62  518.01  218.67
  571.37  218.89  657.46  221.95  718.34  221.89  788.52  222.44  828.58  223.01
  858.56  223.11  882.49  222.85  906.29  222.88  912.52  222.52   920.1  222.43
#Mann= 3 , 0 , 0
       0     .12       0  496.73    .055       0  518.01     .12       0
Bank Sta=496.73,518.01
Exp/Cntr=.3,.1

Type RM Length L Ch R = 1 ,5970.140,280.51,290.45,258.45
XS GIS Cut Line= 3
     1843354.705       397092.93     1843295.192      397240.169
     1842580.348      397446.142
#Sta/Elev= 30
       0  228.83    8.76  228.82   22.65  228.34   43.95   227.9   63.39  226.74
   75.14  226.22   88.54  226.07  100.32  224.99  119.41  224.33   140.2  223.08
  158.81  220.09  175.15  218.98   225.4   218.1   353.8  218.42  379.15  218.37
  399.91  218.66  412.88  218.68  448.92  218.22   555.2  218.02  600.17  218.17
  616.92  218.54  632.51  219.87  649.52  220.59  662.22  220.91  706.49  221.28
  765.51  222.26  824.58  222.89  858.52  223.06  887.92  222.62  902.74  222.59
#Mann= 3 , 0 , 0
       0     .12       0  379.15    .055       0  399.91     .12       0
Bank Sta=379.15,399.91
Exp/Cntr=.3,.1

Type RM Length L Ch R = 1 ,5679.689,353.02,348.78,343.01
XS GIS Cut Line= 2
     1843470.206      396890.923     1842480.653      397233.461
#Sta/Elev= 30
       0  228.34   24.45  228.16   57.88  228.36   76.86  228.26  125.74  228.94
  134.18  228.93  152.44  229.43  187.33  229.35   200.7  228.84  214.96  228.73
  235.02  228.23  294.18   226.4  309.01  225.73  358.03  224.81  368.19  224.43
  385.23  223.29  415.66  221.92  431.13  220.89  438.72  220.07  498.38  217.53
  579.08   216.8  600.02  217.05   649.2  217.11   726.4  218.31  764.81  220.36
  798.63  221.19  817.37  221.91  889.44  221.46  966.11  222.55 1047.16  222.75
#Mann= 3 , 0 , 0
       0     .12       0  579.08    .055       0  600.02     .12       0
Bank Sta=579.08,600.02
Exp/Cntr=.3,.1

Type RM Length L Ch R = 1 ,5330.910,492.62,515.64,508.7
XS GIS Cut Line= 2
     1843503.057      396450.043     1842349.911      396954.544
#Sta/Elev= 30
       0  229.32   37.11  227.81   78.65  225.69  121.98  222.95  180.25   220.6
  190.38  220.45  287.34  220.26  354.33  219.05  392.78   218.7  410.46  217.46
  454.15  216.85  531.12  216.66  558.16  216.84  624.55  215.94  750.17  215.72
  771.57  215.29  782.52  215.24  948.48  215.74  972.33  216.15  980.16  216.75
  987.35     217 1008.16  217.29 1020.95  217.92 1031.83  218.11 1058.27  219.88
 1065.71  220.09 1087.46  220.09 1172.71  221.38 1256.27   222.1 1258.68  221.94
#Mann= 3 , 0 , 0
       0     .12       0  750.17    .055       0  771.57     .12       0
Bank Sta=750.17,771.57
Exp/Cntr=.3,.1