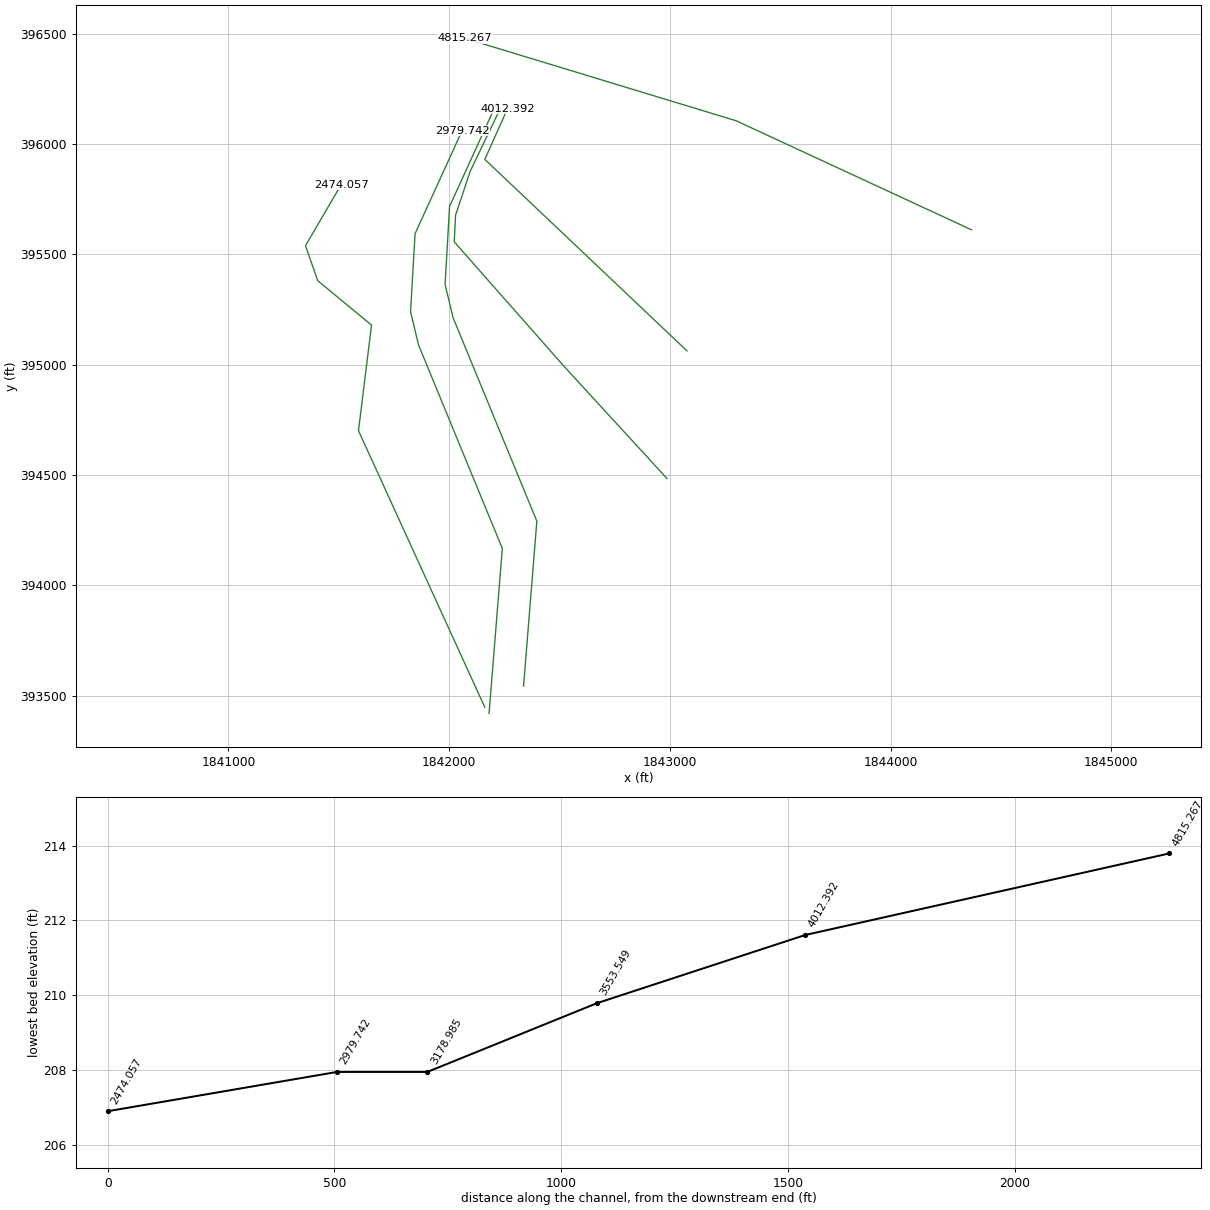
HEC-RAS study gum_limited.prj: Gum Swamp

--- gum_limited.g02 (geometry) --- (continued)

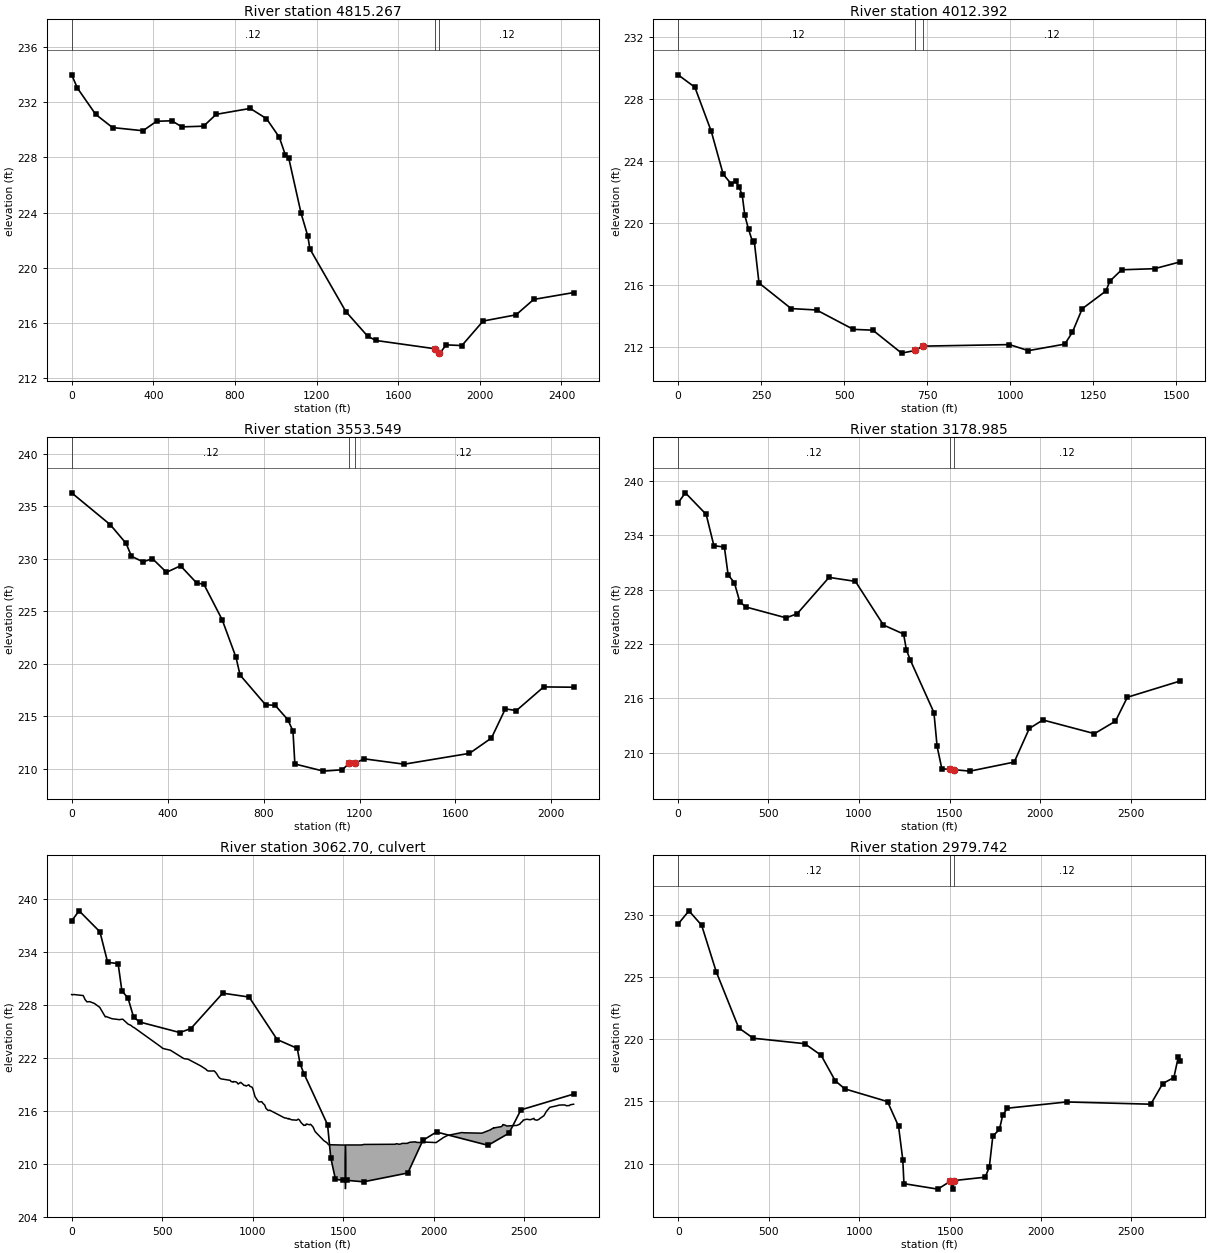
Type RM Length L Ch R = 1 ,4815.267,810.22,802.88,694.97
XS GIS Cut Line= 3
     1844367.135      395610.443     1843300.468      396104.605
     1842071.088       396478.24
#Sta/Elev= 30
       0     234   28.47  233.03  117.57  231.13  200.35  230.17  349.56  229.94
  416.41  230.63  491.22  230.66   539.6  230.22  646.29  230.27  707.97  231.13
  874.72  231.56   954.4  230.82 1017.36  229.47 1047.06  228.18 1063.54  227.96
 1124.17  223.94  1157.4  222.27 1167.07  221.36 1343.28  216.81 1450.25  215.02
  1490.4  214.71 1778.93  214.11 1801.07  213.81 1804.09  213.79  1835.3  214.39
 1911.89  214.34 2016.03  216.12 2177.37  216.57 2263.84  217.69 2460.48  218.19
#Mann= 3 , 0 , 0
       0     .12       0 1778.93    .055       0 1801.07     .12       0
Bank Sta=1778.93,1801.07
Exp/Cntr=.3,.1

Type RM Length L Ch R = 1 ,4012.392,428.36,458.84,386.07
XS GIS Cut Line= 3
     1843077.492      395062.043     1842161.484      395929.841
     1842263.932      396158.843
#Sta/Elev= 30
       0  229.54    50.5  228.74   99.98  225.89  135.74  223.14  159.89  222.51
  172.93  222.67  183.44  222.33   193.2  221.78  200.89  220.48  212.03   219.6
  224.29  218.77  229.42  218.81  243.59  216.13  340.48  214.48  416.98  214.39
  527.77  213.14  586.52  213.09  673.08  211.61  713.98  211.78  736.67  212.06
  998.15  212.16 1055.01  211.77 1164.71  212.19 1187.44  212.95 1217.26  214.47
 1288.54  215.61 1300.21  216.24 1336.01  216.98 1434.95  217.05 1512.68  217.49
#Mann= 3 , 0 , 0
       0     .12       0  713.98    .055       0  736.67     .12       0
Bank Sta=713.98,736.67
Exp/Cntr=.3,.1

Type RM Length L Ch R = 1 ,3553.549,343.51,374.56,262.37
XS GIS Cut Line= 6
     1842987.096      394483.512      1842517.04      394995.753
     1842022.877      395556.206     1842028.904      395676.733
     1842095.194      395875.603       1842233.8      396164.869
#Sta/Elev= 30
       0  236.26  160.96  233.23  226.91  231.45  249.38  230.23   297.5  229.69
  336.81     230  395.33   228.7  453.93  229.32  521.67  227.67  551.01  227.57
  627.28   224.2  685.16  220.61  702.03  218.93  808.42   216.1  848.21  216.05
   900.9  214.69  922.61  213.61  930.51  210.47 1049.55  209.79 1128.59  209.92
  1157.7  210.56 1180.73  210.53 1219.21  210.96 1386.16  210.45 1658.44  211.48
 1750.09  212.94 1807.87  215.71  1854.1  215.55 1967.85   217.8 2093.49  217.77
#Mann= 3 , 0 , 0
       0     .12       0  1157.7    .055       0 1180.73     .12       0
Bank Sta=1157.7,1180.73
Exp/Cntr=.5,.3

Type RM Length L Ch R = 1 ,3178.985,222.91,199.24,272.7
XS GIS Cut Line= 6
     1842336.959      393543.151     1842397.223      394290.421
     1842017.562      395212.455     1841981.403      395363.114
     1842001.749      395716.612     1842214.423      396182.701
#Sta/Elev= 30
    1.29  237.58   41.19  238.69  156.16  236.31  198.86  232.85  256.74   232.7
  277.43  229.62   311.5  228.78  341.88  226.65  375.49  226.08   597.7  224.88
  658.82  225.34  834.57  229.35  980.06  228.91  1134.9  224.09 1246.24  223.09
 1261.65  221.34 1283.01  220.23 1413.62  214.42 1431.14  210.68 1457.23  208.22
 1501.24  208.13 1523.42  208.11 1612.59  207.95 1856.89  208.95 1940.07  212.66
 2015.25   213.6 2299.93  212.09 2415.93  213.47 2481.46  216.11 2773.83  217.91
#Mann= 3 , 0 , 0
    1.29     .12       0 1501.24    .055       0 1523.42     .12       0
Bank Sta=1501.24,1523.42
Exp/Cntr=.5,.3

Type RM Length L Ch R = 2 ,3062.70 ,,,
BEGIN DESCRIPTION:
SR 1337 (NCDOT 82 2047)
END DESCRIPTION:
Bridge Culvert--1,0,-1,-1, 0
Deck Dist Width WeirC Skew NumUp NumDn MinLoCord MaxHiCord MaxSubmerge Is_Ogee
103.29,26,2.6,0,171,171,212.12,,.95,0,0,0,,
       0     2.9    9.33   63.57   69.32   74.04   84.98   99.78  125.99  155.09
  186.01  189.97  222.51   255.1  260.65  280.83  282.12  301.02  311.13  319.01
  325.86  336.32  348.72  491.04  503.43  506.57   508.8  545.26  617.07   623.1
  641.81  712.39  712.74  712.89  743.86  745.48  751.09  753.75  778.13  786.16
  793.85  802.62  809.01  815.26  824.14  876.06  880.35  892.23  894.85  911.14
  919.85  928.31  929.41   933.3  941.29  943.65  952.45  958.65  963.54  978.55
  984.69  997.02 1001.32  1013.2 1026.53 1033.98 1048.36 1050.27 1054.12  1066.4
 1073.11 1084.68 1094.66  1176.7 1184.46 1196.34  1199.7 1202.57 1213.48 1236.15
 1243.02 1251.75 1258.63 1266.43 1281.66 1282.89 1283.25 1284.61 1293.09    1296
 1314.25 1319.09  1324.7 1333.91 1344.24 1393.45 1409.87 1418.84 1486.62 1499.95
 1522.13 1597.69    1610 1613.13 1777.81 1786.51 1794.31 1809.79 1819.13 1825.15
 1852.22 1868.52 1897.71 1901.58 1903.35  1947.6 1959.67 2012.97 2054.03 2073.63
 2076.27 2155.02 2165.66 2168.46 2263.34 2268.71 2311.86 2314.63 2316.68 2329.18
 2330.83 2331.68 2373.36 2379.61 2381.69  2383.8 2396.37 2403.78 2448.98 2459.91
 2471.99 2475.13 2479.88 2492.11 2493.74 2495.75 2513.65 2531.26 2532.48 2535.98
 2553.79 2555.51 2569.41 2579.88  2586.9 2607.12 2608.62 2621.63 2641.03 2642.77
  2645.9 2685.59  2687.1 2688.13 2700.81 2716.92 2724.72 2733.59 2748.96 2754.41
 2772.55
  229.19  229.15   229.2  229.08  228.85  228.62  228.36  228.39  228.18  227.74
  226.66   226.7  226.45  226.37  226.34   226.4   226.4  226.05  225.85  225.77
  225.72  225.54  225.39  223.29  223.08  223.08  223.05  222.88  221.96  221.91
  221.87   221.1   221.1   221.1  220.69  220.62  220.56  220.52  220.52  220.54
   220.4  220.16  219.93  219.76  219.63  219.46  219.33  219.26  219.33  219.26
  219.04  219.17  219.19  219.23   219.1  219.06  218.88  218.89  218.81  218.96
  218.78  218.68  218.47   217.6   217.2  217.01  217.03  217.04  216.91  216.66
  216.29  216.05  216.07  215.19  215.19  215.08  215.14   215.1  214.99  214.95
  214.94  215.06  214.95  214.69  214.35  214.34  214.35  214.37  214.37  214.51
  214.42  214.48  214.37  214.15  213.66  212.61  212.39  212.16  212.13  212.12
  212.13  212.13  212.16  212.19  212.22  212.21  212.27  212.21  212.25  212.31
  212.31  212.44  212.48  212.47  212.43  212.38  212.45   212.4  212.98  213.19
  213.21  213.54  213.52  213.51  213.47  213.49  213.85  213.86  213.91  214.05
  214.01  214.06  214.21  214.33  214.44  214.44  214.36  214.28  214.34  214.35
  214.47  214.47  214.62  214.85  214.95  214.95  215.05     215  214.99  215.01
  215.15  215.01  214.94  215.02  215.14  215.42  215.45  215.92   216.4  216.41
  216.42  216.61  216.61  216.64  216.66  216.67  216.66  216.58   216.6  216.69
  216.75
                                                                                
                                                                                
                                                                                
                                                                                
                                                                                
                                                                                
                                                                                
                                                                                
                                                                                
                                                                                
                                                                                
                                                                                
                                                                                
                                                                                
                                                                                
                                                                                
                                                                                
        
       0     2.9    9.33   63.57   69.32   74.04   84.98   99.78  125.99  155.09
  186.01  189.97  222.51   255.1  260.65  280.83  282.12  301.02  311.13  319.01
  325.86  336.32  348.72  491.04  503.43  506.57   508.8  545.26  617.07   623.1
  641.81  712.39  712.74  712.89  743.86  745.48  751.09  753.75  778.13  786.16
  793.85  802.62  809.01  815.26  824.14  876.06  880.35  892.23  894.85  911.14
  919.85  928.31  929.41   933.3  941.29  943.65  952.45  958.65  963.54  978.55
  984.69  997.02 1001.32  1013.2 1026.53 1033.98 1048.36 1050.27 1054.12  1066.4
 1073.11 1084.68 1094.66  1176.7 1184.46 1196.34  1199.7 1202.57 1213.48 1236.15
 1243.02 1251.75 1258.63 1266.43 1281.66 1282.89 1283.25 1284.61 1293.09    1296
 1314.25 1319.09  1324.7 1333.91 1344.24 1393.45 1409.87 1418.84 1486.62 1499.95
 1522.13 1597.69    1610 1613.13 1777.81 1786.51 1794.31 1809.79 1819.13 1825.15
 1852.22 1868.52 1897.71 1901.58 1903.35  1947.6 1959.67 2012.97 2054.03 2073.63
 2076.27 2155.02 2165.66 2168.46 2263.34 2268.71 2311.86 2314.63 2316.68 2329.18
 2330.83 2331.68 2373.36 2379.61 2381.69  2383.8 2396.37 2403.78 2448.98 2459.91
 2471.99 2475.13 2479.88 2492.11 2493.74 2495.75 2513.65 2531.26 2532.48 2535.98
 2553.79 2555.51 2569.41 2579.88  2586.9 2607.12 2608.62 2621.63 2641.03 2642.77
  2645.9 2685.59  2687.1 2688.13 2700.81 2716.92 2724.72 2733.59 2748.96 2754.41
 2772.55
  229.19  229.15   229.2  229.08  228.85  228.62  228.36  228.39  228.18  227.74
  226.66   226.7  226.45  226.37  226.34   226.4   226.4  226.05  225.85  225.77
  225.72  225.54  225.39  223.29  223.08  223.08  223.05  222.88  221.96  221.91
  221.87   221.1   221.1   221.1  220.69  220.62  220.56  220.52  220.52  220.54
   220.4  220.16  219.93  219.76  219.63  219.46  219.33  219.26  219.33  219.26
  219.04  219.17  219.19  219.23   219.1  219.06  218.88  218.89  218.81  218.96
  218.78  218.68  218.47   217.6   217.2  217.01  217.03  217.04  216.91  216.66
  216.29  216.05  216.07  215.19  215.19  215.08  215.14   215.1  214.99  214.95
  214.94  215.06  214.95  214.69  214.35  214.34  214.35  214.37  214.37  214.51
  214.42  214.48  214.37  214.15  213.66  212.61  212.39  212.16  212.13  212.12
  212.13  212.13  212.16  212.19  212.22  212.21  212.27  212.21  212.25  212.31
  212.31  212.44  212.48  212.47  212.43  212.38  212.45   212.4  212.98  213.19
  213.21  213.54  213.52  213.51  213.47  213.49  213.85  213.86  213.91  214.05
  214.01  214.06  214.21  214.33  214.44  214.44  214.36  214.28  214.34  214.35
  214.47  214.47  214.62  214.85  214.95  214.95  215.05     215  214.99  215.01
  215.15  215.01  214.94  215.02  215.14  215.42  215.45  215.92   216.4  216.41
  216.42  216.61  216.61  216.64  216.66  216.67  216.66  216.58   216.6  216.69
  216.75
                                                                                
                                                                                
                                                                                
                                                                                
                                                                                
                                                                                
                                                                                
                                                                                
                                                                                
                                                                                
                                                                                
                                                                                
                                                                                
                                                                                
                                                                                
                                                                                
                                                                                
        
Culvert=1,5,,26,.027,.7,1,2,2,207.12,1512.33,207.12,1512.33,Culvert #1  , 0 ,103.29
BC Design=,, 0 ,, 0 ,,,,,,

Type RM Length L Ch R = 1 ,2979.742,581.39,505.68,344.31
XS GIS Cut Line= 6
     1842180.583      393419.409     1842240.846      394166.679
     1841861.185      395088.714     1841825.027      395239.373
     1841845.372      395592.871     1842058.046      396058.959
#Sta/Elev= 30
   -1.29  229.24   58.61   230.3  128.65  229.14  209.12  225.41   333.2   220.9
  413.21  220.07  697.99  219.63  788.22   218.7  866.11  216.65  919.29     216
 1154.78  214.98 1215.71     213    1239  210.32 1245.56  208.39 1432.59  207.95
 1501.03  208.58 1514.23  207.96 1523.61  208.64 1694.11  208.91 1716.74  209.72
 1736.22  212.21 1772.53  212.74 1790.88   213.9  1816.9  214.45 2143.54  214.95
  2608.3  214.77 2674.36  216.43 2735.74  216.91 2760.67   218.6 2771.25  218.25
#Mann= 3 , 0 , 0
   -1.29     .12       0 1501.03    .055       0 1523.61     .12       0
Bank Sta=1501.03,1523.61
Exp/Cntr=.5,.3

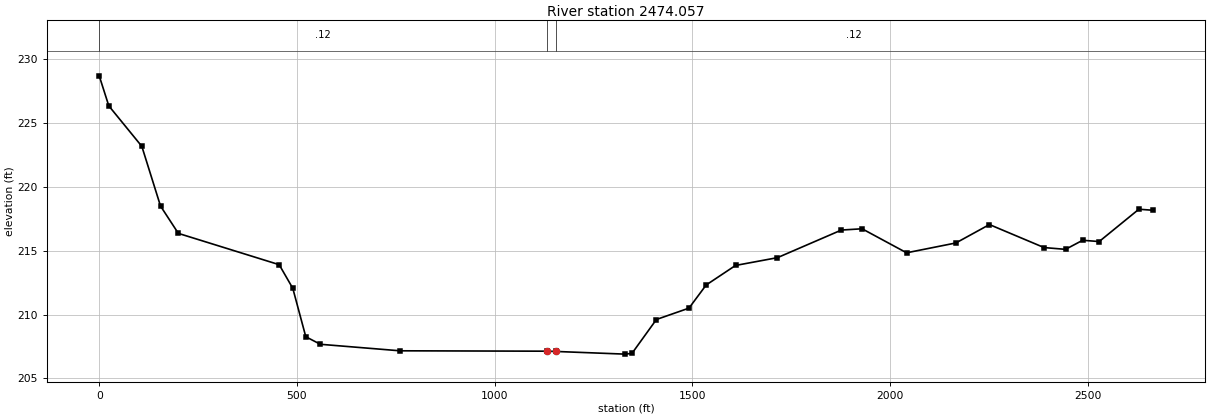
Type RM Length L Ch R = 1 ,2474.057,1574.89,2474.06,715.79
XS GIS Cut Line= 6
     1842161.484      393446.976     1841588.979      394700.461
     1841648.217      395178.818     1841404.643      395379.704
     1841348.756      395538.419     1841510.636       395815.34
#Sta/Elev= 30
       0  228.68   24.23  226.33   107.8  223.16  155.05  218.49  200.14  216.35
   455.2   213.9  489.65  212.05  522.51  208.26  559.46  207.67   760.8  207.16
 1131.92  207.13 1154.38  207.11 1330.01   206.9 1347.64  206.96 1409.34  209.61
 1491.76   210.5 1535.23  212.31 1609.47  213.84 1715.55  214.45 1877.21  216.61
 1929.61  216.71  2042.2  214.83 2166.88   215.6 2251.71  217.04  2389.9  215.24
 2444.19   215.1 2487.55  215.81 2529.31  215.71 2629.73  218.24 2664.81  218.16
#Mann= 3 , 0 , 0
       0     .12       0 1131.92    .055       0 1154.38     .12       0
Bank Sta=1131.92,1154.38
Exp/Cntr=.3,.1