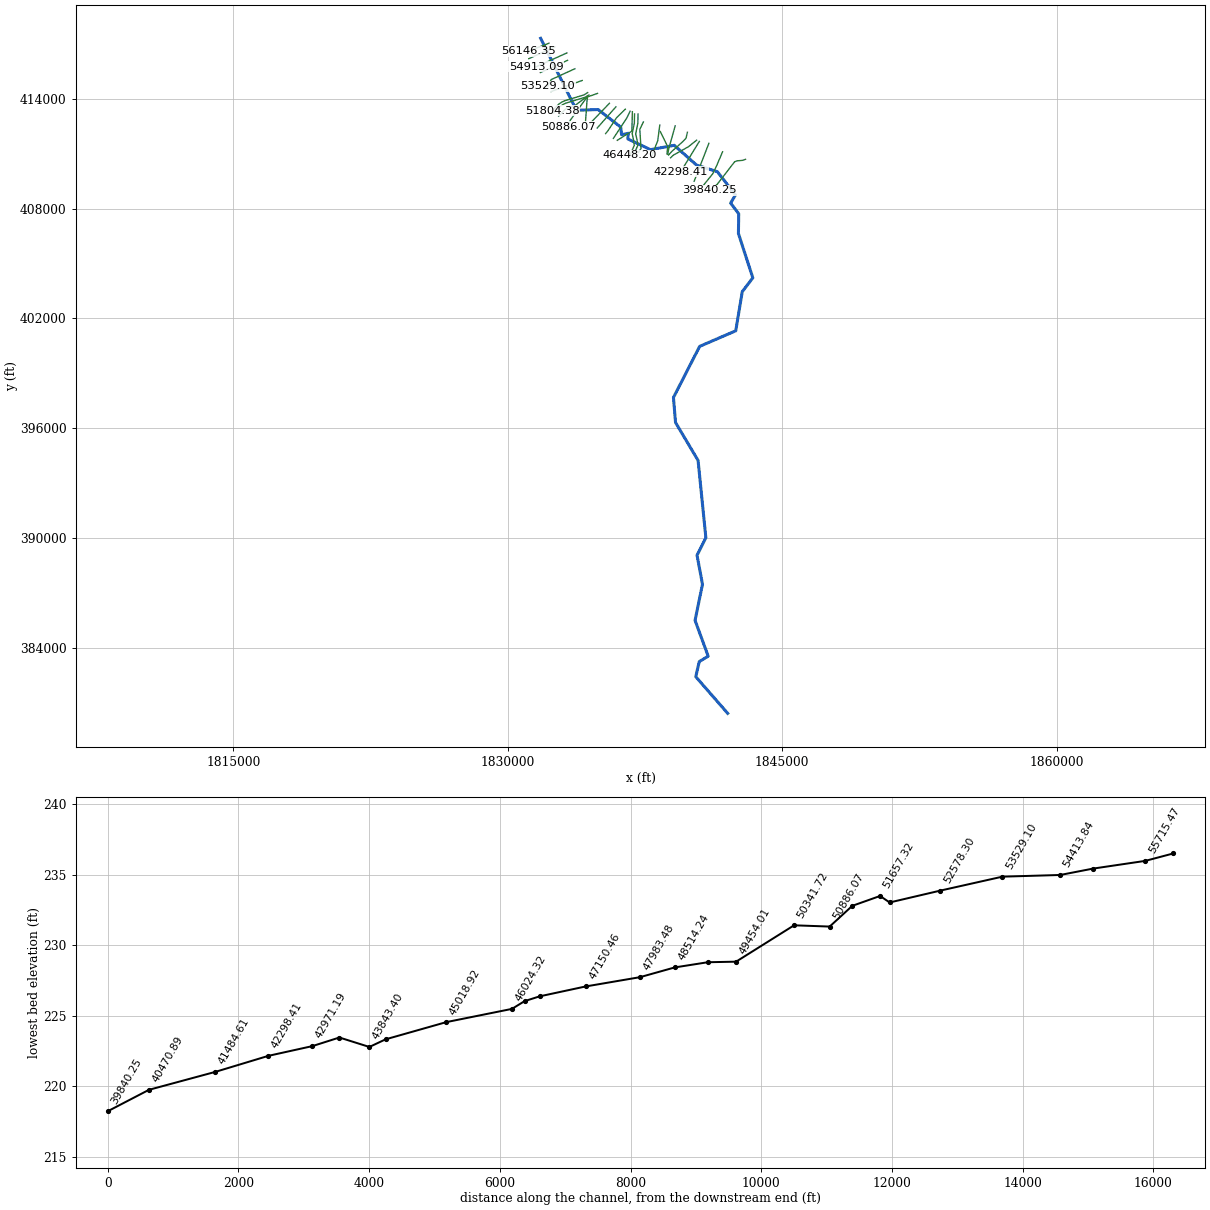
HEC-RAS study gum_limited.prj: Gum Swamp

--- gum_limited.g02 (geometry) --- (continued)

River Reach=Gum Swamp       ,Reach 01
Reach XY= 30
     1831793.425      417312.677     1833750.142      413377.682
     1834936.031      413420.805     1836170.434      412461.313
     1836218.947      412046.252     1836590.885      412121.717
     1836558.543      411814.464     1837798.336       411226.91
     1839097.424      411464.088     1840315.655      410386.007
     1841458.421      410019.459     1842444.865      408752.714
     1842180.735      408305.311     1842622.748      407723.147
     1842606.577      406645.066     1843393.576      404219.384
     1842816.803      403464.727     1842461.036      401324.737
     1840488.148      400473.053       1839054.3      397675.432
      1839168.61      396310.341     1840400.991      394237.731
     1840827.049      390011.567     1840344.068      389053.886
     1840642.136      387466.951     1840236.433      385493.632
     1840954.003      383535.492     1840465.503      383240.184
     1840275.071      382412.217     1842021.588      380409.559

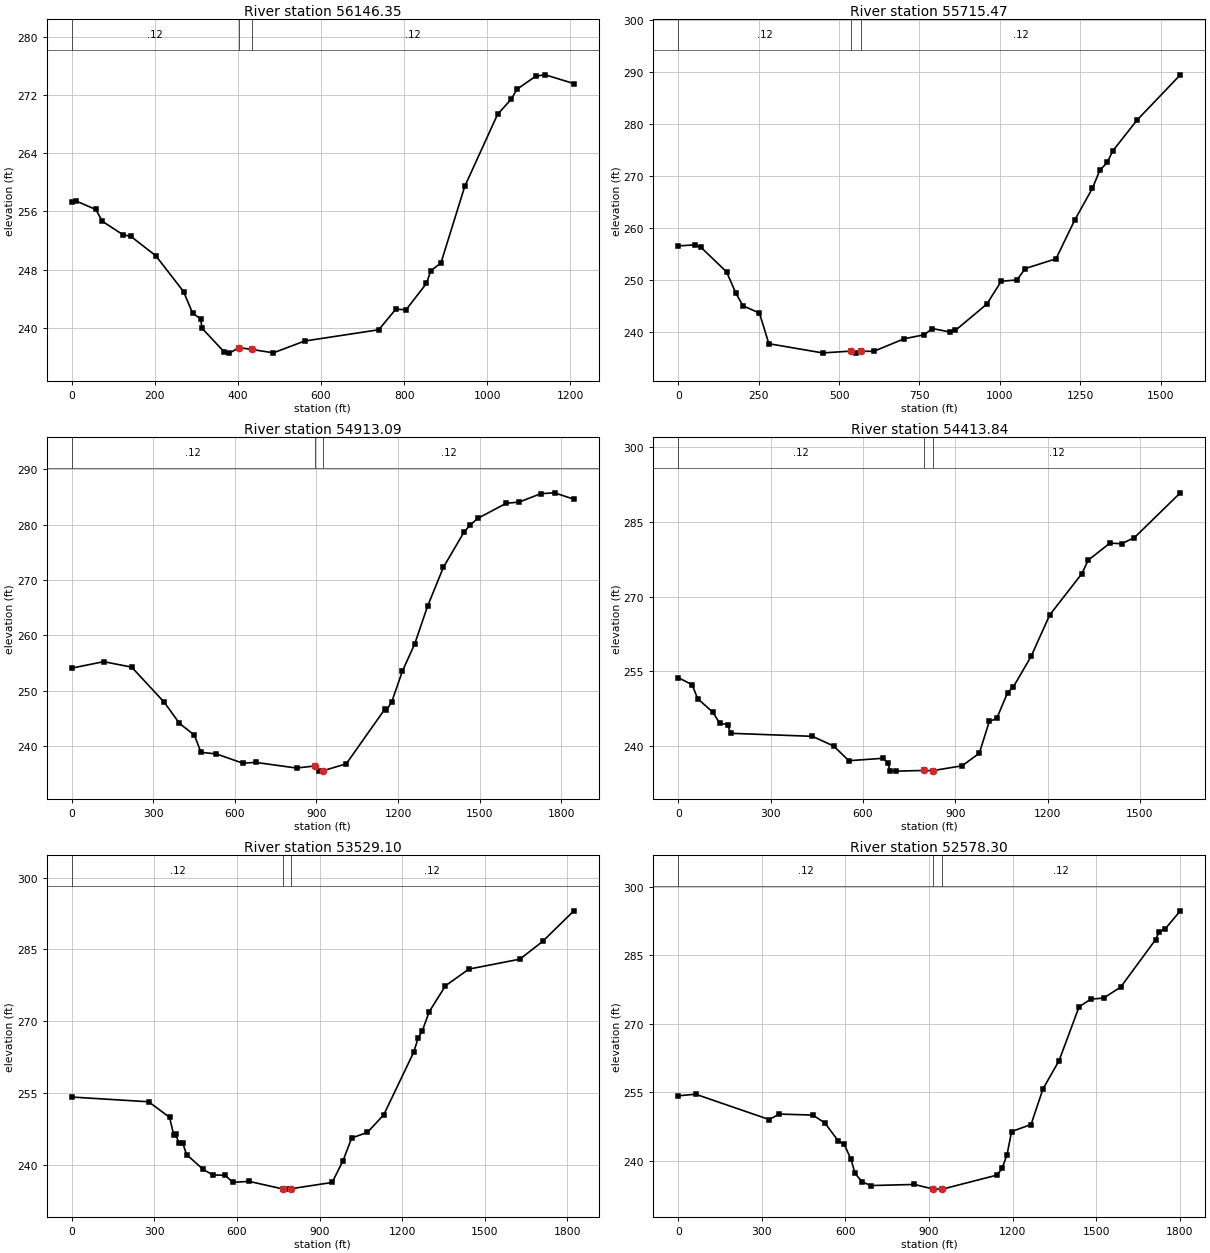
Type RM Length L Ch R = 1 ,56146.35,381.51,430.88,359.51
XS GIS Cut Line= 2
     1832251.916      417047.607     1831124.716      416612.098
#Sta/Elev= 30
       0  257.23   11.06  257.39   57.93  256.25   73.39  254.63  122.84  252.79
  142.26  252.55  202.24  249.89  269.11  244.96  290.91  241.99  310.17  241.22
  313.49  239.93  366.81  236.68  379.56  236.51   402.4  237.27  432.61  237.02
  485.24  236.55  560.33  238.17  738.83  239.72  779.88  242.55  804.62  242.47
  853.73  246.09  863.79  247.81  888.45  248.89  945.84  259.42 1025.02  269.34
 1057.95  271.41 1071.22  272.76 1117.07  274.57 1139.43  274.75 1208.41  273.55
#Mann= 3 , 0 , 0
       0     .12       0   402.4    .055       0  432.61     .12       0
Bank Sta=402.4,432.61
Exp/Cntr=.3,.1

Type RM Length L Ch R = 1 ,55715.47,602.68,802.38,587.97
XS GIS Cut Line= 2
     1832568.731      416844.907      1831147.04      416200.515
#Sta/Elev= 30
       0  256.61   51.15   256.8   70.11  256.37  150.23  251.61  179.43  247.48
  201.04   245.1  252.41  243.68  281.79  237.79  448.83  236.02   538.2  236.37
  552.51  235.98  568.17  236.37   607.1  236.31  702.24  238.74   764.6  239.51
  789.93  240.71   843.8  240.06  861.91  240.37  959.48  245.42 1004.04   249.8
 1053.17  250.06 1078.79  252.25 1174.56  254.13 1232.49  261.57  1287.8   267.7
 1310.48  271.13 1333.87  272.68 1350.85  274.88 1426.44  280.81 1560.91  289.52
#Mann= 3 , 0 , 0
       0     .12       0   538.2    .055       0  568.17     .12       0
Bank Sta=538.2,568.17
Exp/Cntr=.3,.1

Type RM Length L Ch R = 1 ,54913.09,403.79,499.25,384.19
XS GIS Cut Line= 2
     1833229.233      416514.656      1831545.62      415756.051
#Sta/Elev= 30
       0  254.06  117.33  255.23  220.28  254.24  340.27  247.88  395.88  244.08
  450.86  241.95   475.2  238.83  531.82  238.54  628.86  236.87  676.39  237.01
  826.62  235.99  893.64  236.36  909.01  235.43  925.16  235.51  1009.6  236.75
  1151.6  246.65 1157.48  246.48 1176.73  247.95 1215.82  253.48 1261.63  258.48
 1308.54  265.25  1366.8   272.3 1442.43  278.64  1464.3   279.9 1493.07  281.14
 1598.18  283.89 1645.94   284.1 1725.28  285.62 1775.51  285.77 1846.63  284.62
#Mann= 3 , 0 , 0
       0     .12       0  893.64    .055       0  925.16     .12       0
Bank Sta=893.64,925.16
Exp/Cntr=.3,.1

Type RM Length L Ch R = 1 ,54413.84,649.56,884.73,623.49
XS GIS Cut Line= 2
     1833266.829      416110.024     1831778.827      415442.434
#Sta/Elev= 30
       0  253.74   45.15  252.31   63.09  249.52  112.56  246.79  134.72  244.59
  160.17  244.33  170.27  242.57  435.97  241.96  505.33     240  554.15  237.07
  665.77  237.56  680.68  236.54  688.72  235.05  707.33  234.98  797.51  235.11
  826.86  235.08  922.11  236.05  978.04  238.57 1010.36  244.95 1034.78  245.56
 1069.71  250.71 1088.29  251.85  1146.2     258 1206.66  266.31 1311.19  274.61
 1331.38  277.29 1402.43  280.74 1439.93   280.6 1481.77  281.83  1630.9  290.82
#Mann= 3 , 0 , 0
       0     .12       0  797.51    .055       0  826.86     .12       0
Bank Sta=797.51,826.86
Exp/Cntr=.3,.1

Type RM Length L Ch R = 1 ,53529.10,701.43,950.8,678.49
XS GIS Cut Line= 3
     1833664.198      415648.754     1832367.358      415056.719
     1832194.178      414698.276
#Sta/Elev= 30
       0  254.12  279.39  253.13  355.22  249.88  369.91  246.28  378.23  246.37
  387.84  244.59  403.72  244.41  416.79   242.1  476.16  239.04  511.98  237.82
  557.24  237.76  584.87  236.27  643.49  236.49  767.77  234.88  788.59  234.86
  795.12  234.93  945.76  236.26   985.1  240.79 1016.64  245.55 1073.78  246.73
 1133.13   250.4 1241.68  263.45 1258.57  266.53 1272.91  267.91 1298.14  271.94
 1357.35  277.39 1442.37  280.88 1627.63  282.96 1710.11  286.66 1823.67  293.07
#Mann= 3 , 0 , 0
       0     .12       0  767.77    .055       0  795.12     .12       0
Bank Sta=767.77,795.12
Exp/Cntr=.3,.1

Type RM Length L Ch R = 1 ,52578.30,757.77,773.92,737.85
XS GIS Cut Line= 2
     1834063.065      415008.227     1832365.938      414404.983
#Sta/Elev= 30
       0  254.28   62.47  254.62  326.03  249.09  363.03  250.28  482.56  250.06
  525.55  248.38  573.28  244.47  595.46  243.64  620.09  240.36  634.03  237.31
  659.58  235.48  690.31  234.65  847.15  234.89  915.21  233.88  947.68  233.87
 1143.66  236.94 1161.92  238.44 1179.52  241.41 1195.95  246.46 1265.68     248
 1308.59   255.8 1366.27  261.97 1438.04  273.74 1480.55  275.42 1525.86  275.64
 1587.61  278.07 1712.32  288.41 1725.73  290.19 1747.09  290.78 1801.15  294.72
#Mann= 3 , 0 , 0
       0     .12       0  915.21    .055       0  947.68     .12       0
Bank Sta=915.21,947.68
Exp/Cntr=.5,.3

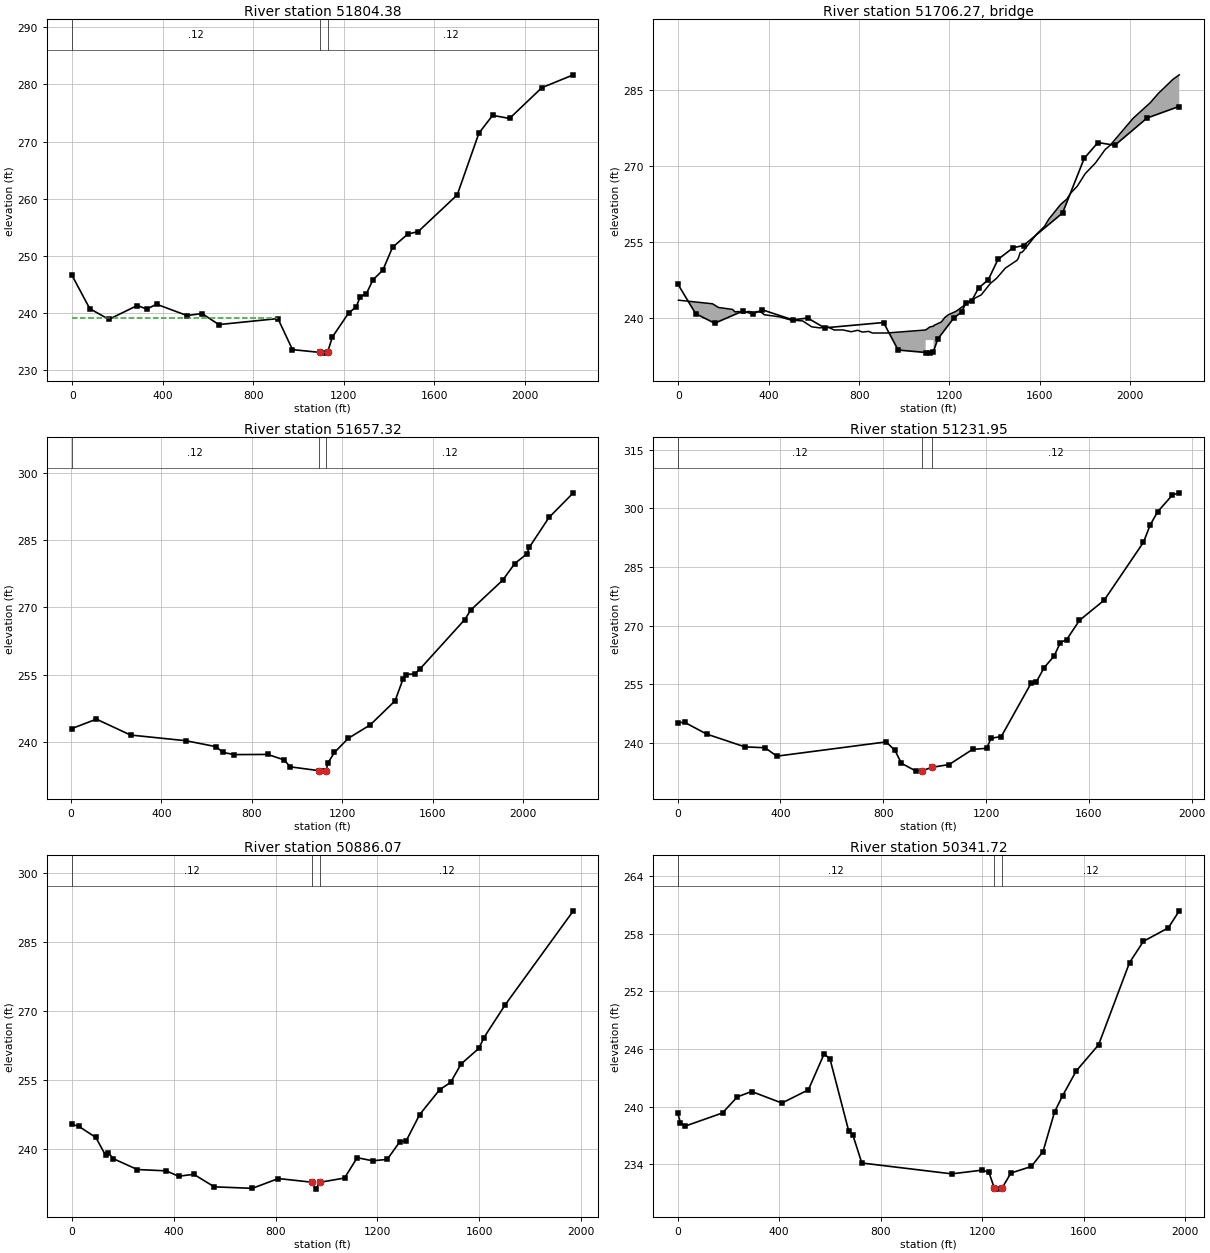
Type RM Length L Ch R = 1 ,51804.38,144.8,147.06,148.22
XS GIS Cut Line= 6
     1834365.974      414345.483     1834164.601      414220.632
     1833105.381      413898.436     1832940.256      413817.887
     1832795.268      413721.228     1832428.769      413358.757
#Sta/Elev= 30
   -3.31  246.71   76.41   240.8  160.85  238.93  286.03  241.35   328.2  240.74
  371.99  241.57  506.16   239.6  572.53  239.95  646.99  238.02  908.23  239.07
  972.61  233.64 1096.34  233.15 1112.28  233.03 1127.88   233.2 1148.69  235.83
 1220.92  240.05 1254.57  241.12 1272.13  242.92 1298.92  243.39 1328.67  245.86
 1371.96  247.52 1414.96  251.53 1482.28  253.84 1528.11  254.27 1700.93  260.69
 1796.82  271.48  1857.5   274.6 1932.27  274.05 2074.94  279.43  2214.3  281.68
#Mann= 3 , 0 , 0
   -3.31     .12       0 1096.34    .055       0 1127.88     .12       0
#XS Ineff= 2 , 0
          904.65  239.11
Bank Sta=1096.34,1127.88
Exp/Cntr=.5,.3

Type RM Length L Ch R = 3 ,51706.27,,,
BEGIN DESCRIPTION:
SR 1340 (NCDOT # 7)
END DESCRIPTION:
Bridge Culvert--1,0,-1,-1, 0
Deck Dist Width WeirC Skew NumUp NumDn MinLoCord MaxHiCord MaxSubmerge Is_Ogee
87.11,22,2.6,0, 60, 60,237,,.95,0,0,0,,
       0  150.94  177.52   239.5  250.73  265.51  290.56  310.17  336.83  346.04
  365.49  380.22   448.6   497.3   550.4  590.02  626.75  662.36  689.02  728.17
  765.03  793.61   814.5  842.69  858.74  921.71 1094.61 1112.94 1129.61 1132.12
 1164.53 1178.99 1194.55 1229.19  1301.3 1340.58 1381.99 1407.88 1447.84 1499.04
 1504.85  1513.6 1520.32  1527.8 1586.86  1620.8 1640.02 1692.57 1718.97 1738.12
 1765.51 1800.92 1846.29 1889.37 1910.83 2014.03 2088.83 2123.83 2189.02  2217.6
  243.48  242.77  242.04  241.66  241.17  241.24   240.9  241.27  240.99  241.24
  241.12  240.61  240.18  239.57  239.38  238.22  238.01  238.19   237.6  237.61
  237.25  237.54  237.19  237.32     237     237   237.6  238.19  238.35  238.51
   239.2  240.04   240.6  241.28  243.61  244.53  246.82  247.76  249.82  251.35
  251.75  252.92   252.9  253.24  256.56  258.05  259.48  262.39   263.4  264.67
  265.95  268.44  270.55  273.21  274.02  279.42  282.44  284.24  287.05  287.96
                                                                                
                                                                                
                                                   235.6   235.6   235.6
                                                                                
                                                                                
                                                                                
       0  150.94  177.52   239.5  250.73  265.51  290.56  310.17  336.83  346.04
  365.49  380.22   448.6   497.3   550.4  590.02  626.75  662.36  689.02  728.17
  765.03  793.61   814.5  842.69  858.74  921.71 1094.61 1112.94 1129.61 1132.12
 1164.53 1178.99 1194.55 1229.19  1301.3 1340.58 1381.99 1407.88 1447.84 1499.04
 1504.85  1513.6 1520.32  1527.8 1586.86  1620.8 1640.02 1692.57 1718.97 1738.12
 1765.51 1800.92 1846.29 1889.37 1910.83 2014.03 2088.83 2123.83 2189.02  2217.6
  243.48  242.77  242.04  241.66  241.17  241.24   240.9  241.27  240.99  241.24
  241.12  240.61  240.18  239.57  239.38  238.22  238.01  238.19   237.6  237.61
  237.25  237.54  237.19  237.32     237     237   237.6  238.19  238.35  238.51
   239.2  240.04   240.6  241.28  243.61  244.53  246.82  247.76  249.82  251.35
  251.75  252.92   252.9  253.24  256.56  258.05  259.48  262.39   263.4  264.67
  265.95  268.44  270.55  273.21  274.02  279.42  282.44  284.24  287.05  287.96
                                                                                
                                                                                
                                                   235.6   235.6   235.6
                                                                                
                                                                                
                                                                                
BR Coef=-1 , 1 , 0 ,, 0 ,,,.8,0,1.2,0,
WSPro=,,,, 1 ,,,, 0 ,,,, 0 ,,,,-1 ,-1 ,-1 , 0 , 0 , 0 , 0 , 0
BC Design=,, 0 ,, 0 ,,,,,,

Type RM Length L Ch R = 1 ,51657.32,276.96,425.37,285.74
XS GIS Cut Line= 6
     1834432.738      414217.089     1834231.366      414092.238
     1833172.146      413770.042      1833007.02      413689.493
     1832862.032      413592.834     1832495.534      413230.364
#Sta/Elev= 30
    3.31  242.96  112.28  245.07  263.15  241.53  508.31  240.26  640.14  238.95
  672.64  237.65  722.02  237.17  869.84  237.21  942.26  235.99  968.93  234.45
 1096.37  233.59 1112.93  233.49 1127.79   233.6 1135.94  235.31 1164.87  237.66
 1226.24  240.81 1322.77  243.78 1432.95  249.16 1468.58  254.09 1481.39  255.01
 1520.07  255.17 1544.05  256.31 1741.16  267.26 1767.21  269.36 1908.81  276.03
 1961.99  279.73 2015.64  281.88 2025.99  283.32 2113.59  290.01 2220.91  295.48
#Mann= 3 , 0 , 0
    3.31     .12       0 1096.37    .055       0 1127.79     .12       0
Bank Sta=1096.37,1127.79
Exp/Cntr=.5,.3

Type RM Length L Ch R = 1 ,51231.95,328.89,345.87,386.51
XS GIS Cut Line= 4
     1834360.947      414158.597     1833684.335      413651.138
     1833168.821      413457.821     1832778.158       413063.13
#Sta/Elev= 30
       0  245.19   27.12  245.28  112.37  242.28  261.46     239  340.26  238.77
  385.67  236.62  811.02  240.27  845.76  238.07  870.41   234.8   927.7  232.79
  952.41  232.93  991.45  233.79  1056.2  234.47 1147.47  238.36 1202.36  238.63
 1219.44  241.21 1259.04  241.63  1374.9  255.27 1395.59  255.61 1425.51  259.24
 1464.54  262.23 1489.11   265.7 1513.16  266.42 1563.45  271.38 1659.45  276.53
 1812.34  291.35 1838.81  295.83 1867.26  299.14 1924.88  303.45 1951.67  304.01
#Mann= 3 , 0 , 0
       0     .12       0  952.41    .055       0  991.45     .12       0
Bank Sta=952.41,991.45
Exp/Cntr=.3,.1

Type RM Length L Ch R = 1 ,50886.07,408.69,544.35,585.92
XS GIS Cut Line= 3
     1834352.892      414130.405     1833406.441      412825.511
     1833305.754      412483.177
#Sta/Elev= 30
       0  245.39   28.23  244.95    94.7  242.54  132.51  238.69  144.19  239.18
  163.43  237.93  257.51  235.58  370.98  235.29  419.28  234.12  479.11  234.54
  559.46  231.82  708.81  231.49     811  233.62  943.07  232.82  958.07  231.32
  972.92  232.79 1070.76  233.73 1120.35  238.15 1180.77  237.48 1238.23  237.78
 1287.61   241.6 1312.86  241.82 1365.58  247.52 1444.37  252.94 1486.95  254.51
 1528.34  258.52  1598.7  261.95 1616.64  264.14  1701.4  271.38 1968.83   291.8
#Mann= 3 , 0 , 0
       0     .12       0  943.07    .055       0  972.92     .12       0
Bank Sta=943.07,972.92
Exp/Cntr=.3,.1

Type RM Length L Ch R = 1 ,50341.72,960.52,887.71,761.47
XS GIS Cut Line= 4
     1834904.653      414303.585     1834360.947      414110.268
     1834330.256      413910.691     1834244.084      412715.771
#Sta/Elev= 30
       0  239.35   10.82  238.32   30.54  237.98  176.68  239.34  234.91  241.01
   291.3  241.57  410.93  240.37   515.2  241.75  577.05  245.48  600.24  244.97
  673.94  237.48  690.61  237.03  725.81  234.13 1079.94     233 1201.28  233.39
 1226.86  233.15 1247.48  231.56 1259.43  231.41 1279.31  231.55 1313.17  233.08
 1394.05  233.77 1439.97  235.32 1485.79  239.47 1517.33  241.14  1570.8  243.71
 1658.95  246.43 1780.98  254.99 1835.55   257.2 1933.84  258.61    1977  260.38
#Mann= 3 , 0 , 0
       0     .12       0 1247.48    .055       0 1279.31     .12       0
Bank Sta=1247.48,1279.31
Exp/Cntr=.3,.1

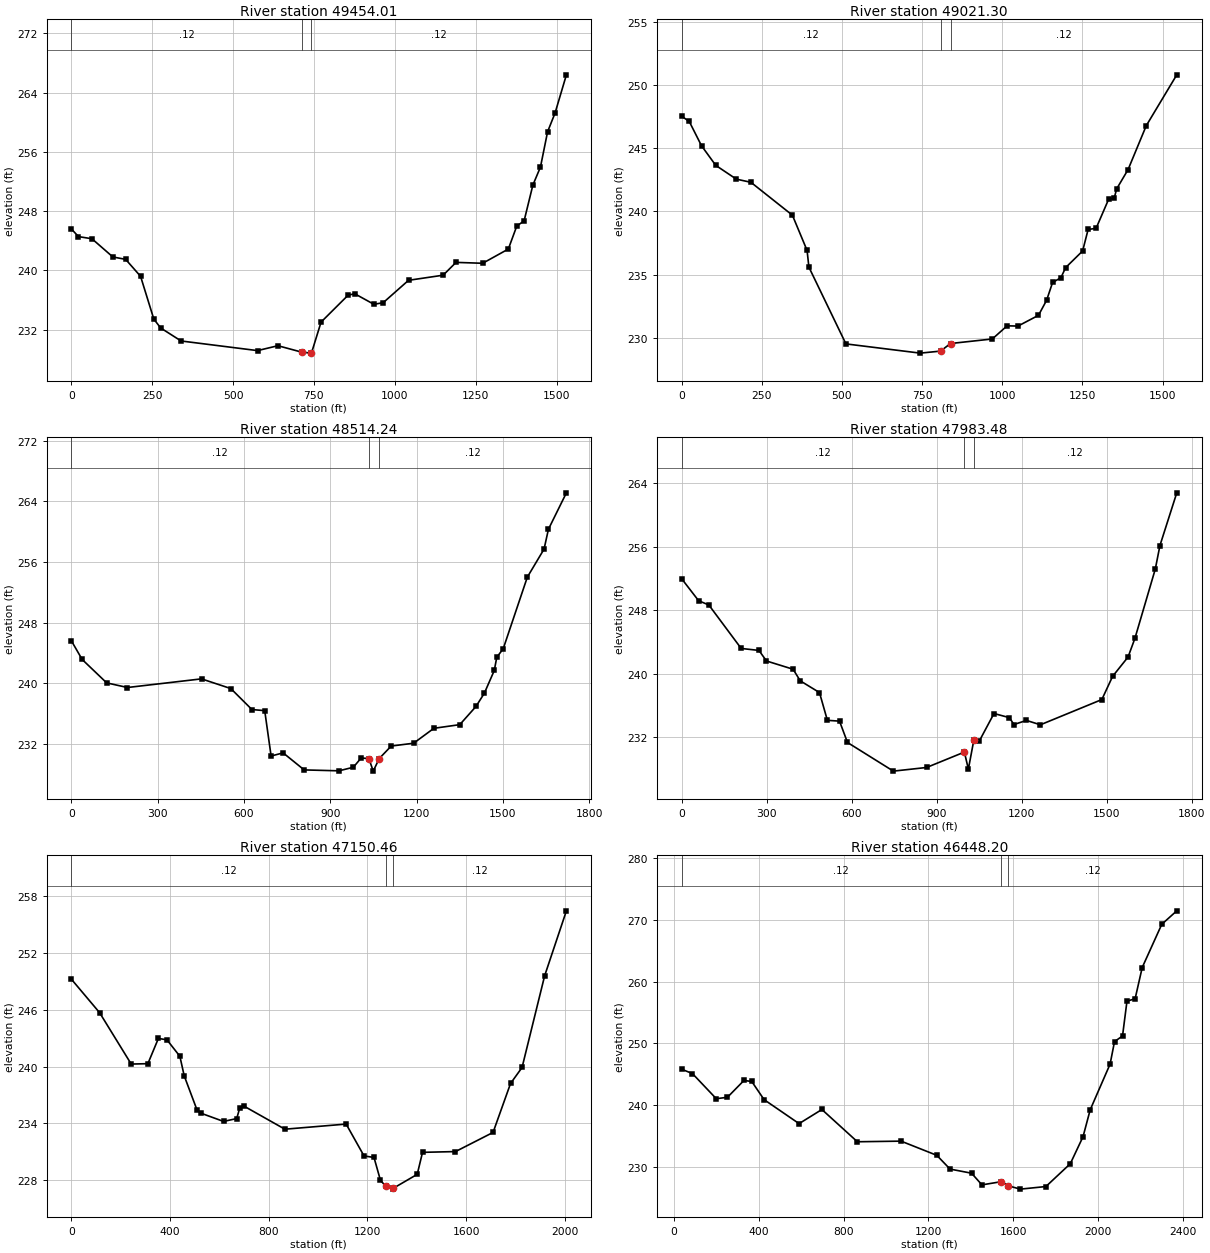
Type RM Length L Ch R = 1 ,49454.01,417.49,432.71,448.53
XS GIS Cut Line= 2
     1835555.135      413761.394     1834493.425      412659.469
#Sta/Elev= 30
       0   245.6   22.21  244.56   63.79  244.27  128.53  241.81  167.97  241.49
  214.09   239.2     255  233.43  276.16  232.23  339.36  230.47  575.55  229.17
  638.62  229.83  711.54  228.97  742.25  228.83  771.96  233.02  855.47  236.65
  875.84  236.85  935.34  235.42     964  235.64 1042.28  238.66  1149.2  239.35
 1189.09  241.08 1271.44  240.96 1350.72  242.88 1376.89  245.99 1399.45  246.68
 1426.53  251.51 1450.03  253.95 1472.04  258.71 1495.21  261.25 1530.19   266.4
#Mann= 3 , 0 , 0
       0     .12       0  711.54    .055       0  742.25     .12       0
Bank Sta=711.54,742.25
Exp/Cntr=.3,.1

Type RM Length L Ch R = 1 ,49021.30,448.7,507.06,494.18
XS GIS Cut Line= 2
     1835909.038      413568.356     1834887.545      412410.128
#Sta/Elev= 30
       0  247.52   23.45  247.12   61.88  245.19  106.26  243.64   170.5  242.55
  215.96   242.3  345.33   239.7  391.16  236.91  396.84  235.59  512.32  229.52
  744.03  228.79  807.54  228.95  838.57  229.55     969  229.91 1015.11  230.95
 1049.06  230.93 1112.91  231.78 1138.29  232.97 1156.95  234.38 1182.71  234.75
 1197.92  235.56 1250.64  236.87 1267.77  238.57 1292.64  238.66 1331.77  240.96
 1348.81  241.03 1357.04  241.79 1392.46  243.31 1449.19  246.78 1544.32   250.8
#Mann= 3 , 0 , 0
       0     .12       0  807.54    .055       0  838.57     .12       0
Bank Sta=807.54,838.57
Exp/Cntr=.3,.1

Type RM Length L Ch R = 1 ,48514.24,491.98,530.75,498.95
XS GIS Cut Line= 4
     1836421.645      413438.861     1835943.735      412970.499
     1835476.551      412265.695     1835347.672      412104.597
#Sta/Elev= 30
       0  245.63   37.75  243.15     123  240.06  195.27  239.45  452.61  240.59
  554.56  239.31  627.98  236.54  672.35   236.4  694.57  230.41  736.27  230.83
  809.56  228.58  930.33  228.46  980.34  228.93 1007.55  230.15 1034.48  230.08
 1049.55  228.42  1070.4  230.08 1112.12  231.73 1189.94   232.1 1260.45  234.07
 1350.39  234.55 1406.75  236.95 1435.87   238.7 1470.35   241.7 1479.12  243.45
 1501.31  244.55 1585.26  254.01 1643.39  257.71 1658.64  260.33 1721.04  265.13
#Mann= 3 , 0 , 0
       0     .12       0 1034.48    .055       0  1070.4     .12       0
Bank Sta=1034.48,1070.4
Exp/Cntr=.3,.1

Type RM Length L Ch R = 1 ,47983.48,604.09,833.02,405.68
XS GIS Cut Line= 3
     1836684.786      413328.942     1836507.578      412962.444
     1835770.555      411842.813
#Sta/Elev= 30
       0  251.97   59.91   249.2   95.82  248.67  210.02  243.19  272.82  242.94
  299.31  241.61  393.24  240.57  418.48  239.11  486.39  237.63  514.27  234.13
  557.17  234.03   585.2  231.34   747.2  227.73  864.53  228.19  997.84  230.13
 1011.94  227.98 1031.04  231.61 1050.63  231.53 1102.38  234.99 1156.67  234.47
 1172.81   233.6 1216.73  234.12 1266.22  233.57 1483.04  236.75 1520.99  239.67
 1575.59  242.11 1599.78  244.46 1671.74   253.2  1688.1  256.16 1747.53   262.8
#Mann= 3 , 0 , 0
       0     .12       0  997.84    .055       0 1031.04     .12       0
Bank Sta=997.84,1031.04
Exp/Cntr=.3,.1

Type RM Length L Ch R = 1 ,47150.46,418.16,702.26,775.76
XS GIS Cut Line= 3
     1836809.637      413304.777     1836781.445       412241.53
      1835984.01      411738.099
#Sta/Elev= 30
       0  249.22  114.67  245.68  242.82  240.26  310.39   240.3  352.96  242.96
  387.57  242.82  440.06  241.08  457.63  239.02  509.66  235.41  527.35  235.06
  617.02  234.21  670.36  234.51   682.9  235.64  701.54   235.8  865.79  233.39
 1113.98  233.93 1186.47  230.57 1226.89  230.41 1252.98     228 1274.24  227.38
 1303.12  227.07 1304.34  227.15 1402.06  228.63 1423.55  230.95 1557.17  231.03
 1709.46  233.05 1780.28  238.21    1827   239.9 1918.51  249.57 2006.67  256.42
#Mann= 3 , 0 , 0
       0     .12       0 1274.24    .055       0 1304.34     .12       0
Bank Sta=1274.24,1304.34
Exp/Cntr=.5,.3

Type RM Length L Ch R = 1 ,46448.20,219.62,230.38,192.73
XS GIS Cut Line= 6
     1836927.342      413178.914     1836917.594       412678.25
     1836798.464      412099.557     1836891.095      411672.648
     1836911.232      411459.193      1836677.64      410915.487
#Sta/Elev= 30
   36.77  245.81   87.64   245.1  199.89  241.03  252.63  241.26  330.49  243.99
  367.26  243.82  425.35  240.88  590.36  236.99  697.97  239.28  865.25  234.05
 1071.33  234.15 1239.83  231.85  1302.2  229.62 1403.77  228.95 1452.62  227.06
  1542.6  227.57 1577.62   226.9 1633.79  226.37 1754.25  226.79 1869.31  230.49
 1929.44  234.88 1963.11  239.23 2057.02  246.65 2077.79  250.29 2115.55   251.2
  2136.5  256.84 2174.99  257.24 2208.41   262.3 2300.68  269.31 2371.39  271.49
#Mann= 3 , 0 , 0
   36.77     .12       0  1542.6    .055       0 1577.62     .12       0
Bank Sta=1542.6,1577.62
Exp/Cntr=.5,.3

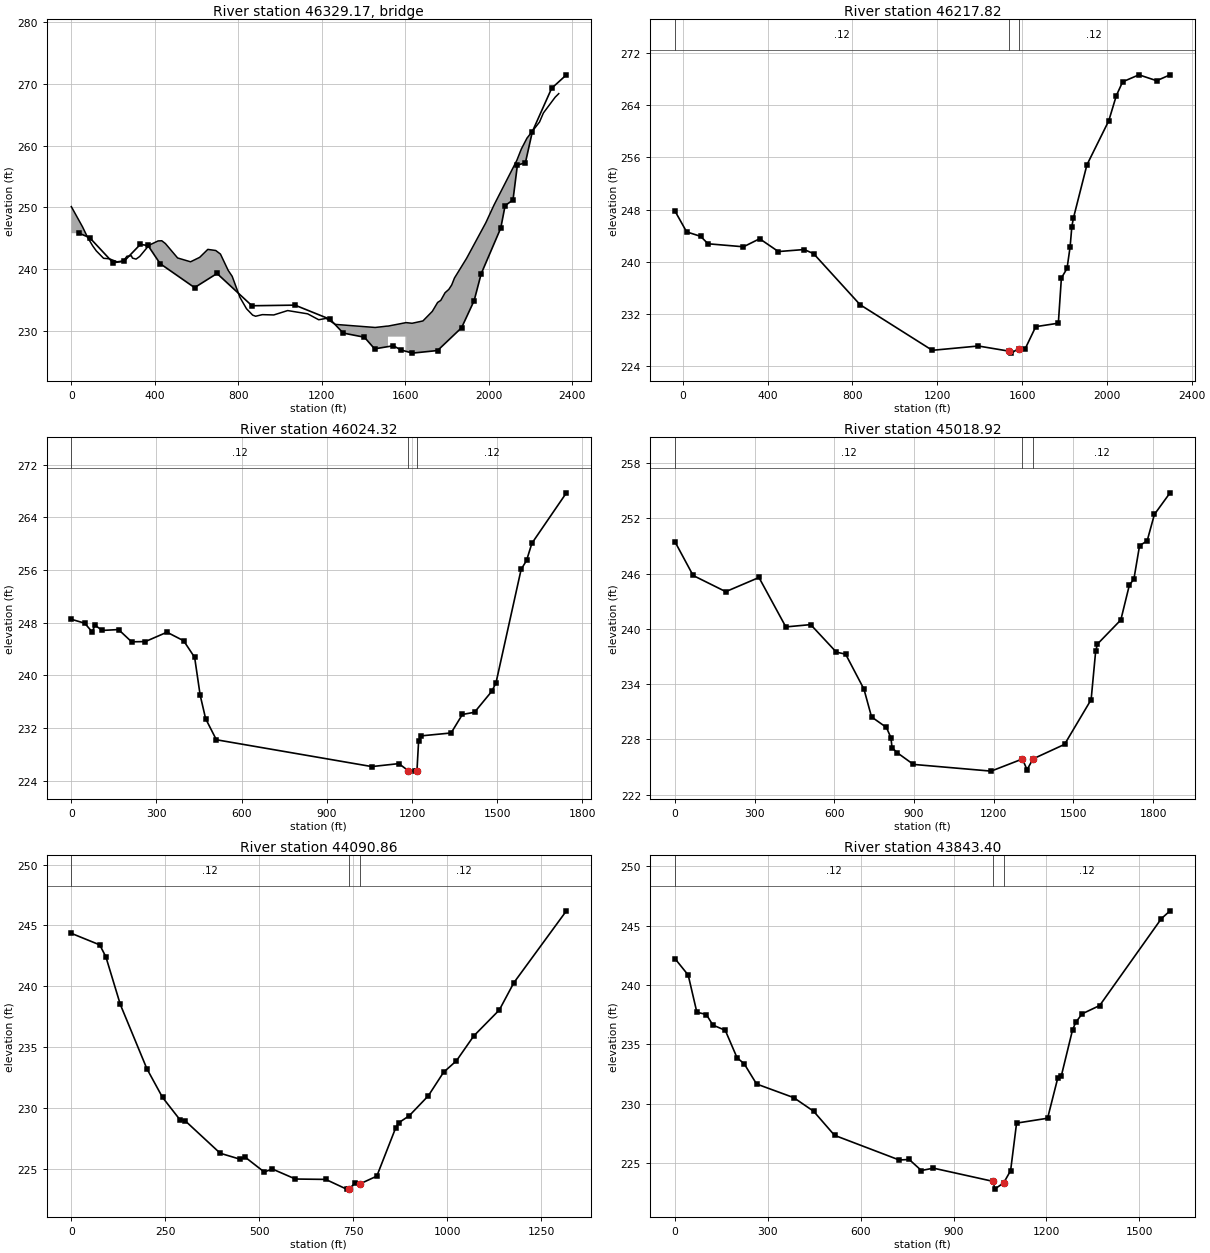
Type RM Length L Ch R = 3 ,46329.17,,,
BEGIN DESCRIPTION:
SR 1001 (NCDOT # 6)
END DESCRIPTION:
Bridge Culvert--1,0,-1,-1, 0
Deck Dist Width WeirC Skew NumUp NumDn MinLoCord MaxHiCord MaxSubmerge Is_Ogee
106.03,26,2.6,0, 60, 60,230.53,,.95,0,0,0,,
       0   53.59   78.19  102.87  119.85  154.64  181.66  218.88  249.71  266.42
  287.74  292.89  310.16  327.55  372.64   415.5  433.29  450.62  509.19  571.19
   614.8  653.82  691.76  714.34  751.55   770.6  807.58  839.09  868.69  882.87
  914.96  969.81 1036.25 1132.11 1185.08 1220.47  1264.6 1455.45 1512.27 1516.61
 1603.61 1632.12 1684.13 1728.99 1754.56 1769.59 1790.05 1808.25 1821.91 1835.16
  1893.2 1985.44 2024.63 2133.68 2155.51 2182.35 2242.59 2261.01 2317.41 2334.62
  250.13  246.86  245.13  243.74  242.94  241.74  241.67  241.18  241.31  242.08
  242.15  241.78  241.61  242.04  243.87  244.56  244.59  244.14   241.8  241.18
   241.9  243.19  243.01  242.43  239.78  238.82  235.42  233.57  232.53  232.35
  232.61  232.56  233.27  232.74  231.78     232  231.03  230.53  230.75  230.75
  231.32  231.21  231.59  233.14  234.59  234.92  236.16  236.71  237.42  238.55
  241.74  247.52  250.39  257.61  259.47  261.22  263.84   265.3  267.86  268.44
                                                                                
                                                                                
                                                                                
                                                                          229.04
  229.04
                                                                                
       0   53.59   78.19  102.87  119.85  154.64  181.66  218.88  249.71  266.42
  287.74  292.89  310.16  327.55  372.64   415.5  433.29  450.62  509.19  571.19
   614.8  653.82  691.76  714.34  751.55   770.6  807.58  839.09  868.69  882.87
  914.96  969.81 1036.25 1132.11 1185.08 1220.47  1264.6 1455.45 1512.27 1516.61
 1603.61 1632.12 1684.13 1728.99 1754.56 1769.59 1790.05 1808.25 1821.91 1835.16
  1893.2 1985.44 2024.63 2133.68 2155.51 2182.35 2242.59 2261.01 2317.41 2334.62
  250.13  246.86  245.13  243.74  242.94  241.74  241.67  241.18  241.31  242.08
  242.15  241.78  241.61  242.04  243.87  244.56  244.59  244.14   241.8  241.18
   241.9  243.19  243.01  242.43  239.78  238.82  235.42  233.57  232.53  232.35
  232.61  232.56  233.27  232.74  231.78     232  231.03  230.53  230.75  230.75
  231.32  231.21  231.59  233.14  234.59  234.92  236.16  236.71  237.42  238.55
  241.74  247.52  250.39  257.61  259.47  261.22  263.84   265.3  267.86  268.44
                                                                                
                                                                                
                                                                                
                                                                          229.04
  229.04
                                                                                
BR Coef=-1 , 1 , 0 ,, 0 ,,,.8,0,1.2,0,
WSPro=,,,, 1 ,,,, 0 ,,,, 0 ,,,,-1 ,-1 ,-1 , 0 , 0 , 0 , 0 , 0
BC Design=,, 0 ,, 0 ,,,,,,

Type RM Length L Ch R = 1 ,46217.82,221.29,193.51,178.78
XS GIS Cut Line= 6
     1837118.842      413173.875     1837109.094      412673.211
     1836989.964      412094.518     1837082.595      411667.608
     1837102.732      411454.153      1836869.14      410910.447
#Sta/Elev= 30
  -36.77  247.78   18.44  244.58   84.28   243.9  119.17  242.76  286.51   242.3
  362.77  243.53  450.99  241.57  572.38  241.88  617.09  241.25   836.2  233.44
 1176.68  226.46 1393.83  227.12 1536.76  226.34 1549.21  226.03 1583.46  226.72
  1614.5  226.68 1664.57  230.08 1771.06  230.61 1785.45  237.52 1812.02  238.98
  1826.6  242.29  1834.7  245.38 1841.76  246.63  1905.8  254.83 2008.84  261.58
 2044.34  265.41 2074.15  267.54 2151.26  268.61  2234.7  267.71 2297.85  268.61
#Mann= 3 , 0 , 0
  -36.77     .12       0 1536.76    .055       0 1583.46     .12       0
Bank Sta=1536.76,1583.46
Exp/Cntr=.5,.3

Type RM Length L Ch R = 1 ,46024.32,1016.97,1005.4,786.15
XS GIS Cut Line= 4
     1837409.728      412740.934      1837216.41      412338.189
     1837280.849      411291.052     1837147.943      411081.624
#Sta/Elev= 30
       0  248.52   47.14  247.93   73.68  246.59   83.31  247.63  108.75  246.83
  166.45  246.96  212.43   245.1  260.94  245.14  336.96  246.56  395.75  245.26
  434.44  242.74  453.83  237.02   473.1  233.44  510.89  230.24 1058.48  226.17
 1153.72  226.62 1187.59  225.52 1209.47  225.48 1217.43   225.5 1223.28  230.04
 1232.03  230.83 1337.73  231.27 1377.51  234.08 1420.17  234.41 1481.72  237.63
 1495.99  238.91 1584.37  256.09 1603.52  257.45 1622.23  260.05  1743.9  267.71
#Mann= 3 , 0 , 0
       0     .12       0 1187.59    .055       0 1217.43     .12       0
Bank Sta=1187.59,1217.43
Exp/Cntr=.3,.1

Type RM Length L Ch R = 1 ,45018.92,517.35,928.06,885.9
XS GIS Cut Line= 3
     1838307.849      412571.781     1838195.081      411713.934
      1837832.61      410783.593
#Sta/Elev= 30
       0  249.47   68.42   245.8  191.32  244.04  316.28  245.58  417.45  240.21
  510.98  240.46  607.48  237.47  642.46  237.25  711.47  233.45  740.07  230.43
   795.9  229.29  812.82  228.19  817.25  227.09  836.69  226.54  897.69  225.27
 1190.14  224.54 1308.04  225.86 1325.37  224.69  1347.9  225.87 1466.67  227.45
 1566.62  232.31 1583.65  237.57 1590.44  238.35 1678.38  240.97 1710.82  244.79
 1727.41  245.38 1748.89  249.04 1777.46  249.56  1804.7  252.43 1863.69  254.78
#Mann= 3 , 0 , 0
       0     .12       0 1308.04    .055       0  1347.9     .12       0
Bank Sta=1308.04,1347.9
Exp/Cntr=.3,.1

Type RM Length L Ch R = 1 ,44090.86,341.65,247.46,149.74
XS GIS Cut Line= 3
     1838336.041      412217.365     1838742.814      411383.683
     1838698.512      410997.048
#Sta/Elev= 30
       0  244.35    75.7   243.4   92.04  242.41  130.36   238.5  200.97  233.22
  242.66  230.86  289.33  229.01  302.41  228.95  396.01  226.27  447.76  225.79
  462.75  225.94     513  224.73  534.99  224.97  596.18  224.15  676.67  224.12
  732.02  223.32  738.72  223.35   754.2  223.79  769.01  223.77  812.56  224.39
  862.51  228.34  870.93  228.78  898.66  229.35  949.44  230.99  990.12  232.93
 1024.25  233.87 1070.25  235.91 1138.36  238.05 1177.01  240.29 1316.79   246.2
#Mann= 3 , 0 , 0
       0     .12       0  738.72    .055       0  769.01     .12       0
Bank Sta=738.72,769.01
Exp/Cntr=.3,.1

Type RM Length L Ch R = 1 ,43843.40,491.61,459.01,347.32
XS GIS Cut Line= 3
     1839149.587      412527.479     1838795.171      411266.887
     1838746.841      410980.938
#Sta/Elev= 30
       0  242.23   42.85  240.84   70.75  237.71  101.52  237.51  122.63  236.62
  162.57  236.18  200.58  233.87  223.85  233.35   263.7  231.65  383.71   230.5
  447.98  229.35  515.54  227.32  724.42  225.24  756.84  225.28   796.1  224.35
  834.97  224.55 1028.46  223.43 1032.88  222.78 1062.05  223.31 1084.39  224.34
 1103.67  228.35 1203.87  228.76 1236.47  232.13 1248.08  232.32  1284.4  236.21
  1294.8  236.85 1315.38  237.57  1372.1  238.27 1571.35   245.6 1599.47  246.26
#Mann= 3 , 0 , 0
       0     .12       0 1028.46    .055       0 1062.05     .12       0
Bank Sta=1028.46,1062.05
Exp/Cntr=.3,.1

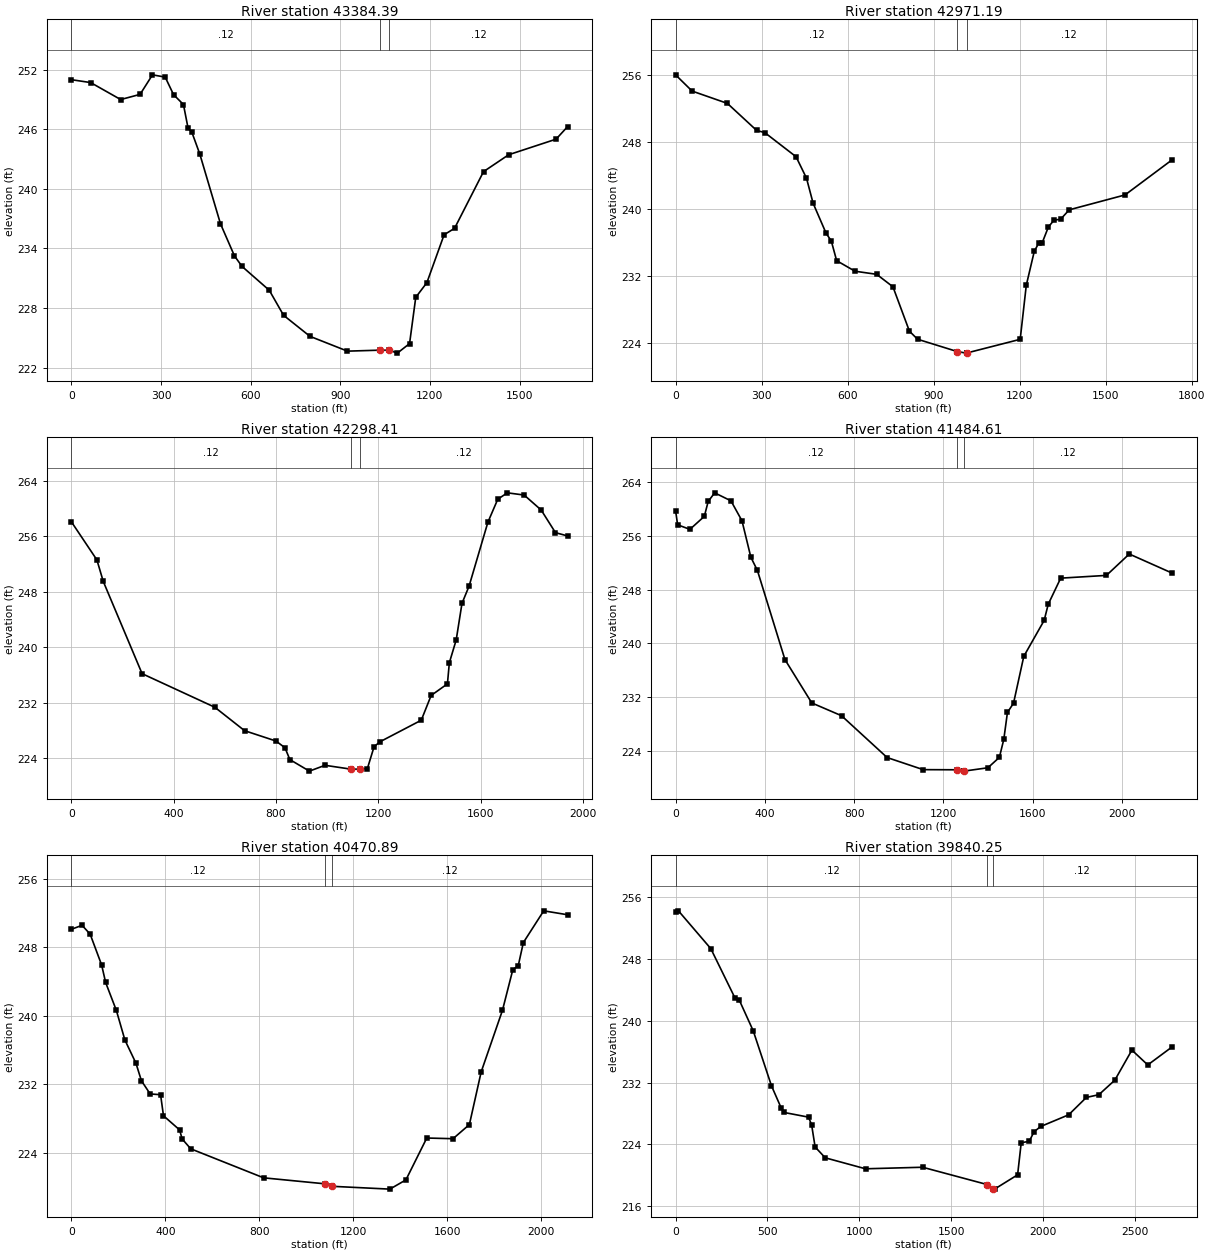
Type RM Length L Ch R = 1 ,43384.39,348.12,413.2,288.36
XS GIS Cut Line= 5
     1839818.144      412177.091     1839741.622      411850.867
     1839568.442      411669.632     1838960.296      411125.926
     1838787.116      410932.608
#Sta/Elev= 30
       0  250.99    64.6   250.7  165.08  248.99  229.97  249.51   271.5  251.48
  314.06  251.25  342.12  249.48  375.16  248.49  390.81  246.08  402.94  245.73
  429.91   243.5  499.06  236.48  545.92  233.24  571.33  232.18  662.44  229.78
  710.28  227.26  798.65  225.14  924.08  223.65 1034.61  223.75 1064.73  223.74
 1091.02  223.45 1131.93  224.41 1152.66  229.07 1189.93  230.55  1247.5  235.37
 1282.55  236.02 1379.46  241.73 1463.59  243.43 1622.28     245 1661.05  246.27
#Mann= 3 , 0 , 0
       0     .12       0 1034.61    .055       0 1064.73     .12       0
Bank Sta=1034.61,1064.73
Exp/Cntr=.3,.1

Type RM Length L Ch R = 1 ,42971.19,569.17,672.78,666.05
XS GIS Cut Line= 5
     1840321.575      411746.154     1839874.528       411387.71
      1839302.63      411065.514     1839056.955      410932.608
     1838895.857      410779.565
#Sta/Elev= 30
       0  256.07   57.74  254.13  180.72  252.66  282.85  249.43   311.3  249.17
  420.29  246.29  456.68  243.73  479.74  240.74  525.07  237.15  543.09  236.24
  561.86  233.88  625.88  232.62  701.41  232.25  758.18  230.76  815.69  225.46
  844.03   224.5  983.17  223.02 1014.83  222.84 1016.06  222.86 1202.03  224.49
 1223.24  230.94 1251.22  235.01 1266.44  235.95 1278.68  236.01 1300.34   237.9
 1320.16  238.73 1342.88  238.82 1372.92  239.95  1567.7  241.73 1730.94   245.9
#Mann= 3 , 0 , 0
       0     .12       0  983.17    .055       0 1016.06     .12       0
Bank Sta=983.17,1016.06
Exp/Cntr=.3,.1

Type RM Length L Ch R = 1 ,42298.41,704.41,813.8,756.26
XS GIS Cut Line= 2
     1840469.562      411678.192     1839455.445      410024.199
#Sta/Elev= 30
       0   258.1   99.83   252.6  124.69   249.5  276.49   236.2  560.83  231.36
  677.16  227.98  799.92  226.49  835.08  225.52  854.22  223.81  930.62  222.15
  991.52  222.99 1092.18  222.44 1127.22  222.43 1157.09   222.5 1183.41  225.67
 1206.83  226.39 1367.91  229.49 1406.47  233.06 1470.15  234.73 1477.64  237.77
 1504.41  241.06 1527.03  246.33 1554.84  248.83 1628.41  258.04 1666.94  261.35
 1704.46  262.27 1770.06  261.95 1836.68  259.79 1892.46  256.53 1940.14  256.05
#Mann= 3 , 0 , 0
       0     .12       0 1092.18    .055       0 1127.22     .12       0
Bank Sta=1092.18,1127.22
Exp/Cntr=.3,.1

Type RM Length L Ch R = 1 ,41484.61,865.6,1013.71,809.02
XS GIS Cut Line= 2
     1840992.373      411573.629     1840187.434       409501.35
#Sta/Elev= 30
       0  259.76    9.37  257.64   64.43  256.97  128.84   258.9  146.23  261.12
  175.15   262.4  248.11  261.21  297.58  258.24  337.31  252.82  366.71  250.85
  489.99   237.6  610.28  231.15  743.52  229.25   947.7  223.03 1109.29  221.23
 1260.51  221.21 1290.62  221.01 1291.63  221.01 1399.15  221.51 1450.62  223.06
 1470.41  225.75 1486.61  229.73 1513.97  231.12 1559.91  238.08 1651.19  243.43
 1669.39  245.83  1725.2  249.71 1930.11  250.12 2032.41   253.3 2223.12  250.48
#Mann= 3 , 0 , 0
       0     .12       0 1260.51    .055       0 1291.63     .12       0
Bank Sta=1260.51,1291.63
Exp/Cntr=.3,.1

Type RM Length L Ch R = 1 ,40470.89,671.26,630.64,565.59
XS GIS Cut Line= 4
     1841740.389       411110.32     1841402.579      410318.882
     1841209.541      409916.719     1840702.816      409289.346
#Sta/Elev= 30
       0  250.09   45.67  250.56   80.09  249.52  128.84  245.93  145.94  243.88
  191.54  240.62  227.98  237.16  274.86  234.46  298.34   232.4   335.5  230.86
  379.86  230.77  392.26  228.31  460.82  226.66  471.76   225.6  508.26  224.45
   818.6  221.06 1079.78  220.36 1109.36  220.07 1356.11  219.74 1424.45  220.82
 1513.21  225.71 1625.01  225.63 1694.67  227.28 1744.83  233.43 1835.53  240.63
 1879.74  245.39 1902.55  245.82 1924.41  248.54  2011.2  252.25 2113.06  251.79
#Mann= 3 , 0 , 0
       0     .12       0 1079.78    .055       0 1109.36     .12       0
Bank Sta=1079.78,1109.36
Exp/Cntr=.3,.1

Type RM Length L Ch R = 1 ,39840.25,994.82,997.76,850.49
XS GIS Cut Line= 6
     1842995.803      410699.016     1842838.732      410642.632
     1842552.783      410618.467      1842399.74       410566.11
     1841437.179      409321.628     1841034.434      409007.487
#Sta/Elev= 30
       0  254.06    15.6  254.21  191.82  249.32   322.6  242.97  346.77  242.66
  422.74  238.68  521.62  231.59  573.72  228.76   591.3  228.13  723.18  227.53
  740.13  226.54  759.21  223.67  814.25  222.27 1033.32  220.85 1343.93  221.05
 1695.39  218.81 1725.09  218.29 1735.18  218.22 1860.61  220.07 1880.31  224.22
 1923.72   224.4 1950.42  225.65 1986.24  226.32 2138.32  227.83 2234.72  230.08
 2302.55  230.43 2389.44  232.31 2482.33   236.2  2568.7  234.28 2699.67  236.59
#Mann= 3 , 0 , 0
       0     .12       0 1695.39    .055       0 1725.09     .12       0
Bank Sta=1695.39,1725.09
Exp/Cntr=.3,.1