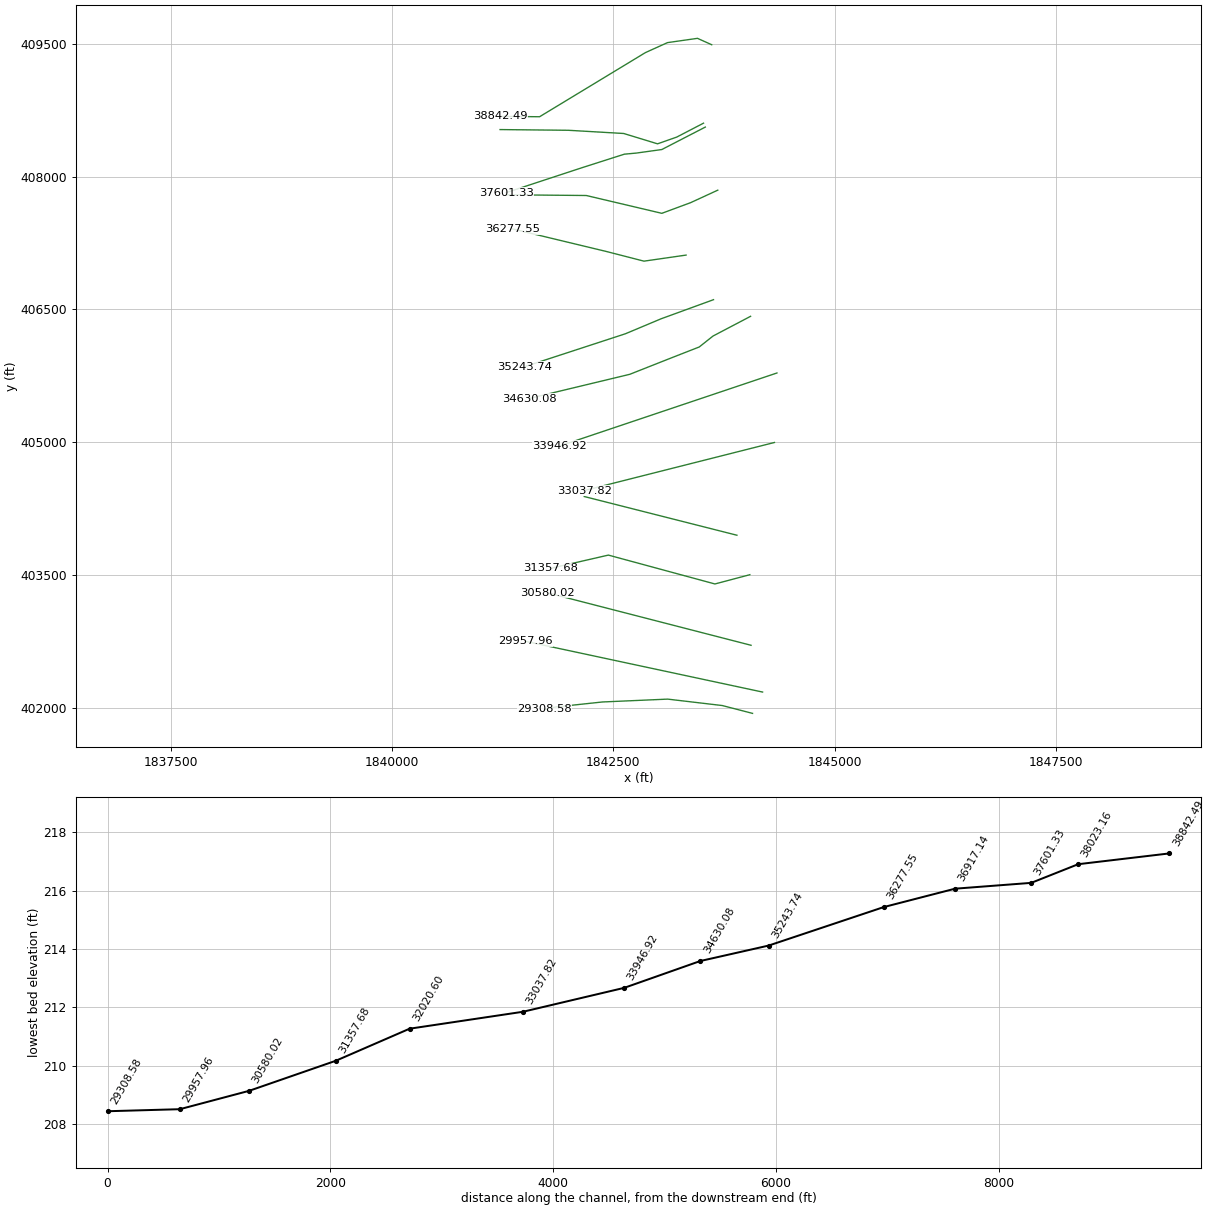
HEC-RAS study gum_limited.prj: Gum Swamp

--- gum_limited.g02 (geometry) --- (continued)

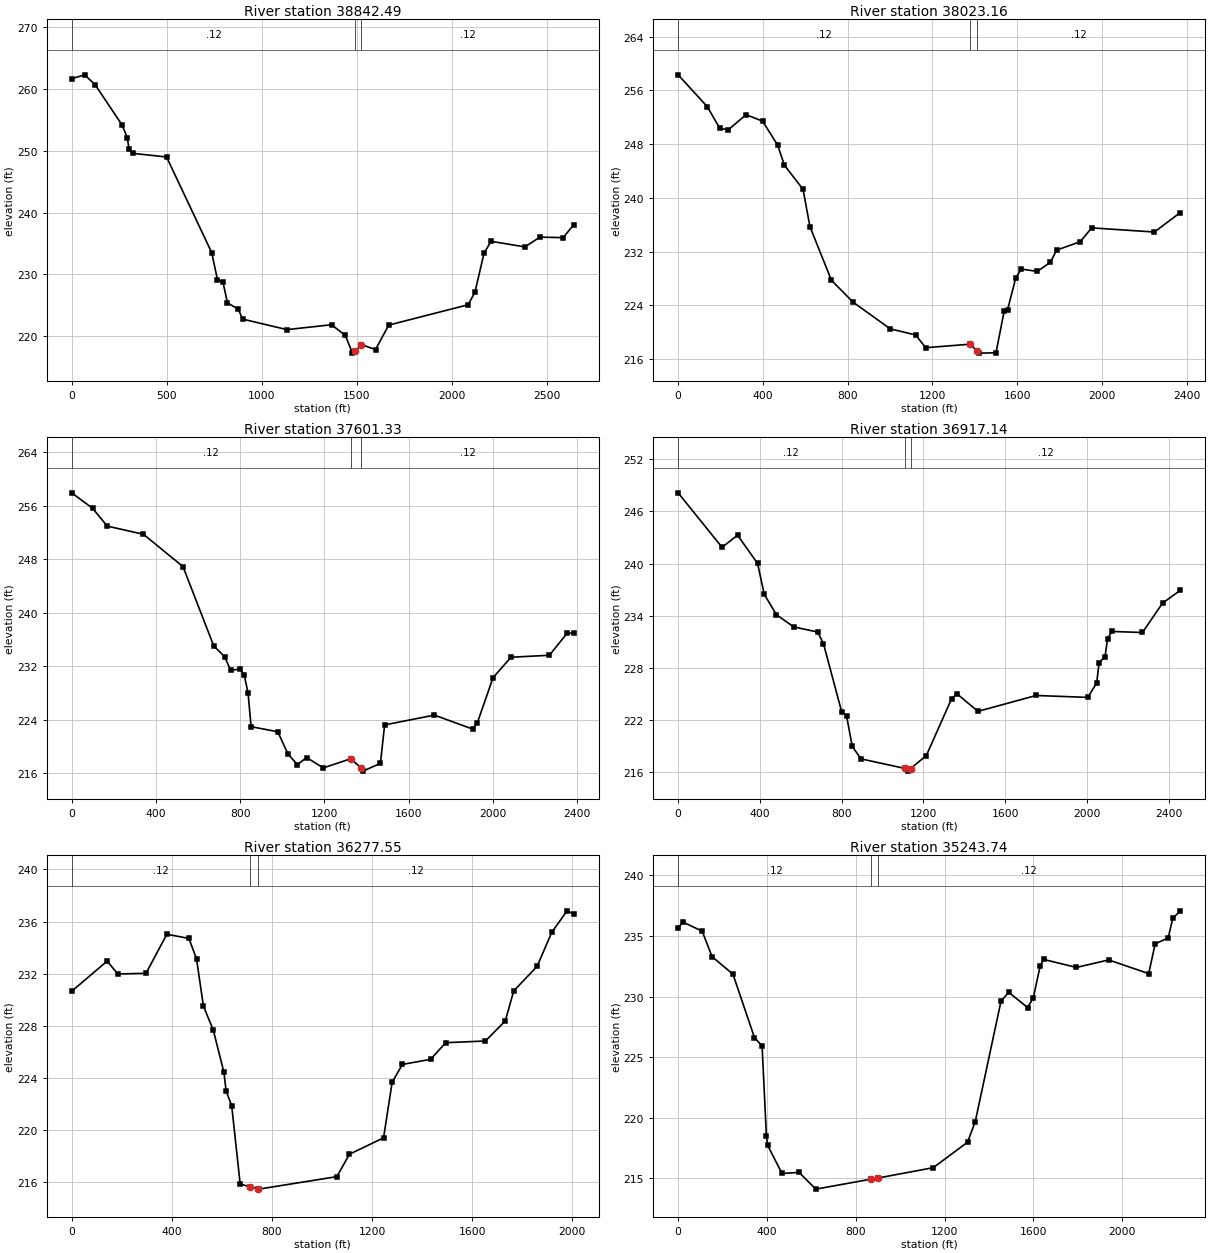
Type RM Length L Ch R = 1 ,38842.49,788.83,819.33,530.65
XS GIS Cut Line= 6
     1843612.003      409490.781     1843450.905      409563.275
     1843112.599      409514.946     1842862.897      409402.177
     1841666.744      408677.236     1841223.724      408681.263
#Sta/Elev= 30
       0  261.64   68.53  262.27  124.59  260.62   265.7  254.14  292.28  252.11
  302.32   250.2  319.99  249.58  499.17  248.99  736.71  233.51  766.51  229.17
  795.59  228.78  819.23  225.42   876.6  224.36  898.96  222.78 1132.33  221.08
  1366.6  221.87 1439.08  220.13 1476.81  217.28 1492.02  217.57 1523.71  218.65
 1597.91  217.86 1667.29  221.81 2084.59   225.1 2120.48   227.1 2168.24   233.4
 2204.97  235.36 2383.48  234.45 2462.11  236.03 2584.48  235.95 2640.74  238.05
#Mann= 3 , 0 , 0
       0     .12       0 1492.02    .055       0 1523.71     .12       0
Bank Sta=1492.02,1523.71
Exp/Cntr=.3,.1

Type RM Length L Ch R = 1 ,38023.16,314.24,421.84,413.07
XS GIS Cut Line= 6
     1843519.372      408604.741     1843217.313      408447.671
      1842999.83      408371.149     1842617.222      408487.945
     1841992.967      408524.192     1841219.697      408532.247
#Sta/Elev= 30
       0   258.3  138.29  253.54  196.17  250.35  236.51  250.12  320.65  252.37
  398.64  251.41  469.47  247.86  501.49  244.86  589.58  241.26  621.87  235.74
  723.09  227.76  825.14   224.5 1001.12  220.52 1120.76  219.61 1168.61  217.72
 1379.14  218.24 1409.95  217.24 1421.05  216.91 1499.91  216.96 1538.55  223.16
 1554.71  223.38 1593.61  228.14 1619.96  229.41 1695.05  229.06 1757.11  230.43
 1785.51  232.22 1897.35  233.48 1951.64  235.54 2247.37  234.92 2369.66  237.82
#Mann= 3 , 0 , 0
       0     .12       0 1379.14    .055       0 1409.95     .12       0
Bank Sta=1379.14,1409.95
Exp/Cntr=.3,.1

Type RM Length L Ch R = 1 ,37601.33,705.91,684.19,582.36
XS GIS Cut Line= 6
     1843539.509      408560.439      1843048.16       408306.71
     1842758.183      408266.436     1842625.277      408254.353
     1842146.011       408101.31     1841288.163      407819.388
#Sta/Elev= 30
       0  257.94   99.49  255.62  168.92  252.96  341.02  251.73     529  246.89
  674.77  235.03  727.01  233.38   755.1  231.38  800.58  231.54  820.04  230.62
  838.07  227.93  852.25  222.93  979.21  222.16 1027.51  218.84 1072.53  217.24
 1116.05  218.31  1195.1  216.75 1326.23  218.13 1373.93  216.75  1383.7  216.27
 1466.58  217.43 1486.65  223.19 1722.78  224.66 1904.17  222.57 1926.82   223.5
 2001.63  230.27 2086.72  233.32 2269.36  233.62 2352.92   236.9  2385.3  236.94
#Mann= 3 , 0 , 0
       0     .12       0 1326.23    .055       0 1373.93     .12       0
Bank Sta=1326.23,1373.93
Exp/Cntr=.3,.1

Type RM Length L Ch R = 1 ,36917.14,578.53,639.59,566.89
XS GIS Cut Line= 5
      1843680.47      407847.581     1843374.383       407706.62
      1843048.16      407585.796      1842194.34      407787.169
     1841300.246      407795.224
#Sta/Elev= 30
       0  248.15  214.92  241.87  290.75  243.27  388.64  240.01  421.17  236.46
  481.01   234.1  564.83   232.7  682.64   232.1  710.75  230.78  800.05   222.9
  823.98  222.44   851.6  218.91  894.98  217.48 1107.52  216.39 1122.02  216.07
 1137.52  216.37 1213.93  217.86 1337.63  224.42 1364.13  224.98 1466.53  222.96
 1750.86  224.79 2003.22  224.57 2047.34  226.22 2059.02  228.58 2088.05  229.27
 2100.15  231.28 2120.56  232.17 2271.17  232.05  2369.3  235.44 2456.24  236.91
#Mann= 3 , 0 , 0
       0     .12       0 1107.52    .055       0 1137.52     .12       0
Bank Sta=1107.52,1137.52
Exp/Cntr=.3,.1

Type RM Length L Ch R = 1 ,36277.55,850.32,1033.81,985.41
XS GIS Cut Line= 4
     1843322.136      407113.824     1842846.343      407045.278
     1842419.877      407154.859     1841364.685      407408.588
#Sta/Elev= 30
       0  230.64  142.06  232.96  184.11  231.97  297.09  232.02  380.22  235.02
  468.51   234.7  498.91  233.13  526.36  229.51  565.74  227.66  608.36  224.41
  617.05  222.99  639.35  221.85  673.37  215.82  714.24  215.62  744.33  215.46
  747.36  215.44 1059.75   216.4 1109.59  218.12 1246.07  219.38  1280.4  223.65
 1321.31  225.02    1434  225.41 1494.44  226.69 1653.01  226.82 1732.29  228.36
 1766.21  230.67  1859.4  232.55 1918.42  235.18 1979.33  236.82 2006.29  236.58
#Mann= 3 , 0 , 0
       0     .12       0  714.24    .055       0  744.33     .12       0
Bank Sta=714.24,744.33
Exp/Cntr=.3,.1

Type RM Length L Ch R = 1 ,35243.74,452.94,613.65,447.78
XS GIS Cut Line= 4
     1843632.256      406609.806     1843039.381      406393.775
     1842637.219      406224.866     1841501.618      405853.992
#Sta/Elev= 30
       0  235.66   21.92  236.15  108.37   235.4  152.88   233.3  247.01  231.85
  343.91  226.62  378.22  225.93   397.6   218.5  403.51  217.72  467.96  215.41
  544.75   215.5   620.3  214.12  868.33  214.94  898.23  215.03 1149.25  215.89
 1303.48  217.99 1338.31  219.69 1454.16  229.62 1488.83  230.36 1574.02   229.1
 1599.63   229.9 1630.89  232.55 1646.38  233.07 1794.01  232.41 1939.09  233.03
 2119.44   231.9 2148.42  234.35 2207.22  234.85 2227.82  236.46 2261.83  237.08
#Mann= 3 , 0 , 0
       0     .12       0  868.33    .055       0  898.23     .12       0
Bank Sta=868.33,898.23
Exp/Cntr=.3,.1

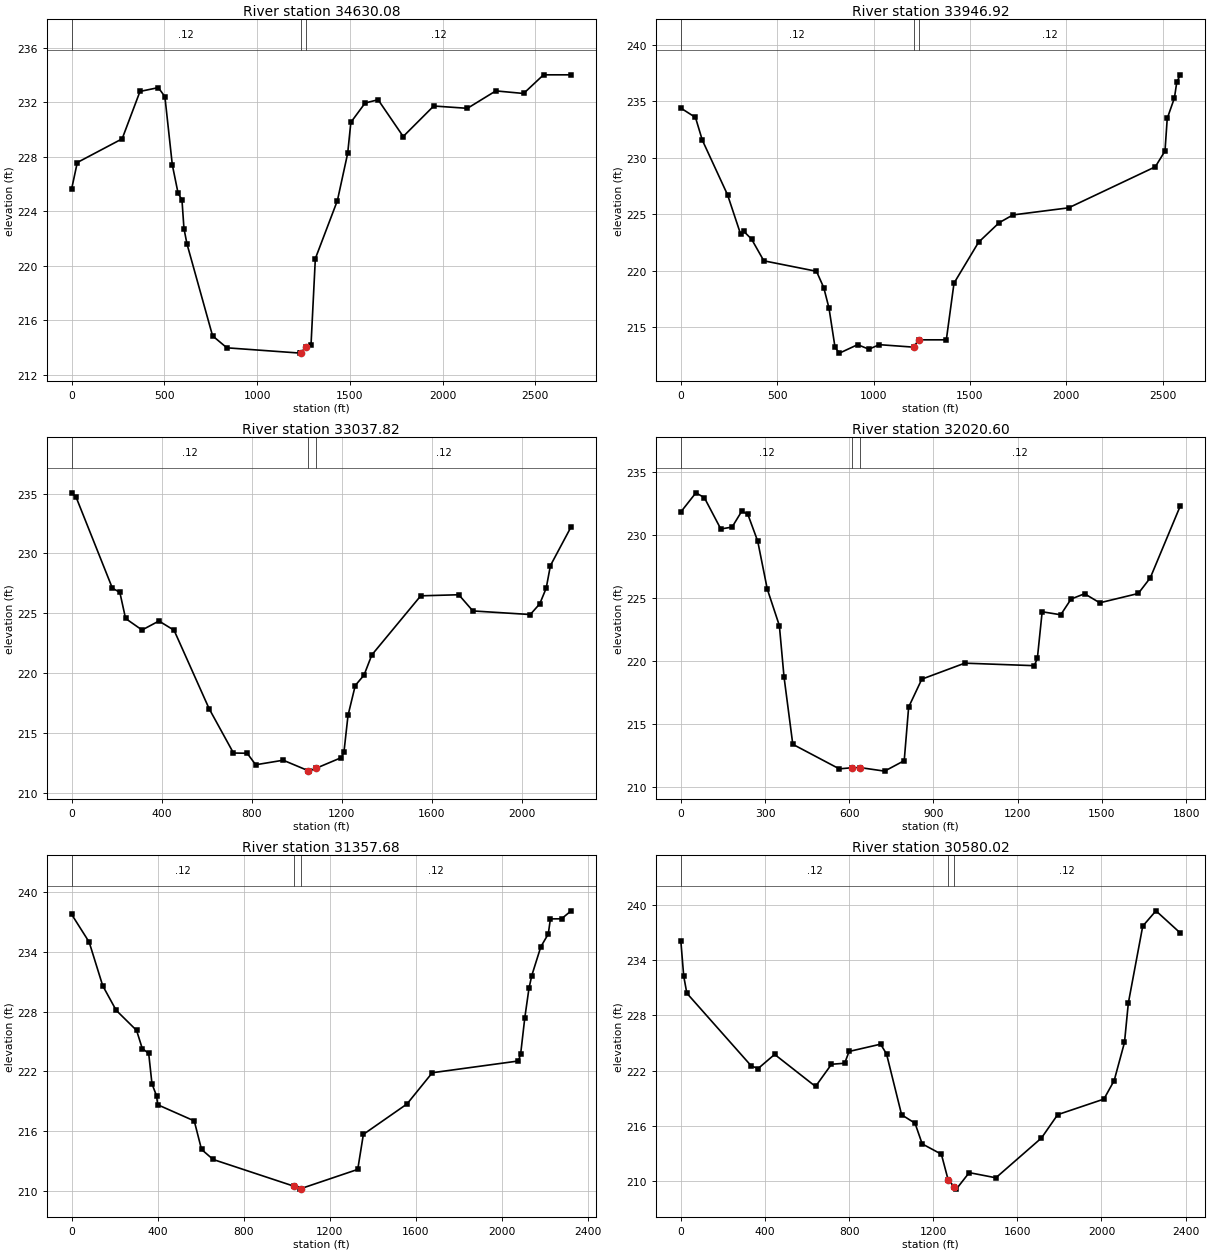
Type RM Length L Ch R = 1 ,34630.08,543.01,683.16,529.06
XS GIS Cut Line= 6
     1844050.995      406421.863     1843626.862      406199.094
     1843471.042      406075.502     1843159.408      405953.573
     1842685.478      405766.401     1841546.842       405492.84
#Sta/Elev= 30
       0  225.61   31.11  227.59  272.89  229.33  369.07  232.81   467.8  233.09
  503.27  232.43  543.28  227.42  574.35  225.34  595.37  224.84  606.12  222.74
  622.21  221.62  760.36  214.86  837.39  213.98 1233.92  213.59 1236.17  213.61
  1263.1  214.05 1291.11  214.22 1314.29  220.53  1433.1  224.79 1488.71  228.27
 1505.74  230.54 1582.65  231.96  1652.6   232.2 1787.95   229.5 1952.49  231.74
 2134.08  231.57 2287.16  232.85 2436.88  232.66 2544.36  234.03 2693.19  234.03
#Mann= 3 , 0 , 0
       0     .12       0 1236.17    .055       0  1263.1     .12       0
Bank Sta=1236.17,1263.1
Exp/Cntr=.3,.1

Type RM Length L Ch R = 1 ,33946.92,675.12,909.1,658.82
XS GIS Cut Line= 2
     1844349.027      405781.498     1841892.281       404955.87
#Sta/Elev= 30
       0  234.41   75.96  233.58  111.38  231.57  242.54  226.71  309.72  223.25
  325.63  223.49  366.77  222.79  430.59  220.86  703.75  219.93  741.49  218.48
  768.59  216.67  800.11  213.17  823.02  212.67  917.09  213.42  975.59  213.02
  1030.1  213.42 1207.76   213.2 1233.68  213.85 1377.32  213.85 1417.18  218.88
 1544.66  222.51 1651.33  224.24 1722.67  224.93 2011.62  225.56 2461.41   229.2
 2511.67   230.6 2523.31  233.49 2560.58  235.31 2573.09  236.74 2591.77  237.36
#Mann= 3 , 0 , 0
       0     .12       0 1207.76    .055       0 1233.68     .12       0
Bank Sta=1207.76,1233.68
Exp/Cntr=.3,.1

Type RM Length L Ch R = 1 ,33037.82,730.74,1017.22,594.42
XS GIS Cut Line= 2
     1844320.834      404996.145     1842170.175      404452.439
#Sta/Elev= 30
       0  235.06   19.67  234.73  181.58   227.1  214.42  226.77  239.99  224.58
  313.14  223.62  388.14  224.37  455.27   223.6  611.14  217.05  718.99  213.36
  779.93  213.34   817.7  212.38  939.93  212.76 1049.27   211.9 1052.88  211.85
 1084.76  212.08 1198.39  212.98 1209.73  213.46 1227.59  216.49 1259.78  218.99
 1298.82  219.86  1333.3  221.54 1550.52  226.47 1719.37  226.56 1782.04  225.21
 2036.89  224.91 2078.92   225.8 2107.59  227.11 2126.31  228.99 2218.32  232.23
#Mann= 3 , 0 , 0
       0     .12       0 1049.27    .055       0 1084.76     .12       0
Bank Sta=1049.27,1084.76
Exp/Cntr=.3,.1

Type RM Length L Ch R = 1 ,32020.60,589.96,662.93,647.75
XS GIS Cut Line= 2
      1843896.67      403947.979     1842171.542      404385.336
#Sta/Elev= 30
       0  231.84   53.66  233.36   83.71  232.98  142.43  230.49  182.59  230.64
  217.25  231.91  238.79  231.65  273.92  229.52  307.97  225.72  351.01  222.82
  367.56  218.76  398.85   213.4  564.46  211.45  610.45  211.54  638.91  211.55
  725.91  211.27  795.77   212.1  811.55  216.35  858.44  218.57  1011.5  219.84
  1259.1  219.64 1270.08  220.23 1287.12  223.92 1353.32  223.68 1390.19  224.93
 1438.31  225.35 1492.25  224.63 1629.46  225.37 1672.24  226.61  1779.7  232.35
#Mann= 3 , 0 , 0
       0     .12       0  610.45    .055       0  638.91     .12       0
Bank Sta=610.45,638.91
Exp/Cntr=.3,.1

Type RM Length L Ch R = 1 ,31357.68,641.56,777.66,595.45
XS GIS Cut Line= 4
      1844042.94       403501.96      1843648.25      403397.247
     1842444.042       403723.47     1841795.622      403574.454
#Sta/Elev= 30
       0  237.78   81.94  234.98  144.89   230.6  207.43  228.13  302.32  226.11
  328.68  224.29  358.59   223.8  373.75  220.75  395.58  219.51  399.86  218.65
  570.26  217.02  603.95  214.16  657.76  213.15 1035.29  210.45 1062.49  210.17
 1065.47  210.22 1329.81  212.15 1355.98  215.67 1558.56  218.72  1676.2  221.86
  2076.5  223.04 2086.68  223.74 2106.05  227.39 2125.36  230.33 2138.39  231.62
  2180.3   234.5 2215.11   235.8 2224.97  237.31 2276.66  237.32 2321.28  238.12
#Mann= 3 , 0 , 0
       0     .12       0 1035.29    .055       0 1065.47     .12       0
Bank Sta=1035.29,1065.47
Exp/Cntr=.3,.1

Type RM Length L Ch R = 1 ,30580.02,543,622.07,561.77
XS GIS Cut Line= 2
     1844056.517      402704.311     1841755.981      403296.873
#Sta/Elev= 30
       0  236.09   13.72  232.26   28.64   230.4  334.49  222.52   367.2  222.22
   446.1  223.76  640.55  220.28   716.4  222.69  779.03   222.8  800.17  224.08
  950.02  224.87  978.25   223.8 1049.82  217.21 1113.69  216.29 1147.63  214.05
 1238.85  212.93 1270.96  210.16 1299.47  209.41  1309.7  209.14 1371.34  210.93
 1498.04  210.37  1714.9  214.69 1791.85  217.22 2011.72  218.91 2060.52  220.92
 2109.61  225.06 2127.82  229.32 2196.39  237.68 2259.18  239.34 2375.62  236.92
#Mann= 3 , 0 , 0
       0     .12       0 1270.96    .055       0 1299.47     .12       0
Bank Sta=1270.96,1299.47
Exp/Cntr=.3,.1

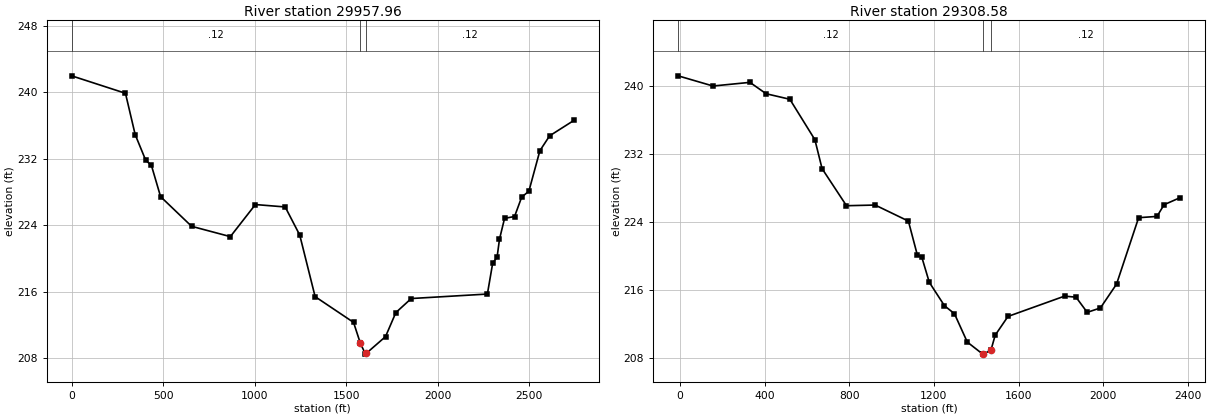
Type RM Length L Ch R = 1 ,29957.96,410.89,649.37,520.47
XS GIS Cut Line= 2
     1844186.792      402175.648      1841503.12      402750.181
#Sta/Elev= 30
       0     242  294.09   239.9  347.16  234.93  404.88  231.83  435.82  231.23
  486.03  227.46  655.69  223.89  867.28  222.65 1004.17  226.51 1167.01  226.22
 1246.48  222.84 1330.54  215.43  1540.6  212.33 1578.08   209.8 1605.82  208.51
 1611.01  208.62 1715.38  210.62 1771.76  213.51 1855.86   215.2 2272.04  215.74
 2301.21  219.49 2324.93  220.16 2338.14  222.34 2365.88  224.85 2420.49  225.07
 2459.52  227.41 2498.66  228.11 2558.92  232.99 2612.18  234.78 2744.48  236.63
#Mann= 3 , 0 , 0
       0     .12       0 1578.08    .055       0 1611.01     .12       0
Bank Sta=1578.08,1611.01
Exp/Cntr=.5,.3

Type RM Length L Ch R = 1 ,29308.58,93.46,101.21,93.64999
XS GIS Cut Line= 6
     1844073.052      401934.807     1843730.719      402023.411
     1843114.519      402095.905     1842377.495      402063.685
     1841849.899      402007.301      1841721.02      401979.109
#Sta/Elev= 30
    -9.5  241.22  155.41  240.02  330.07  240.45  406.59  239.11  518.76  238.46
  637.12   233.7  671.12  230.29  786.59  225.92  922.09     226  1079.3  224.11
 1121.61  220.11 1142.94  219.84 1178.07   216.9 1249.86  214.14 1297.04   213.2
 1357.77  209.86  1430.8  208.44 1434.16  208.44 1469.77  208.92 1489.66  210.67
 1550.18  212.88 1817.48  215.27 1871.74  215.15 1924.84  213.36 1987.18  213.88
 2063.35  216.68 2167.87  224.51 2254.64  224.66 2288.25  226.04 2364.94  226.88
#Mann= 3 , 0 , 0
    -9.5     .12       0 1434.16    .055       0 1469.77     .12       0
Bank Sta=1434.16,1469.77
Exp/Cntr=.5,.3