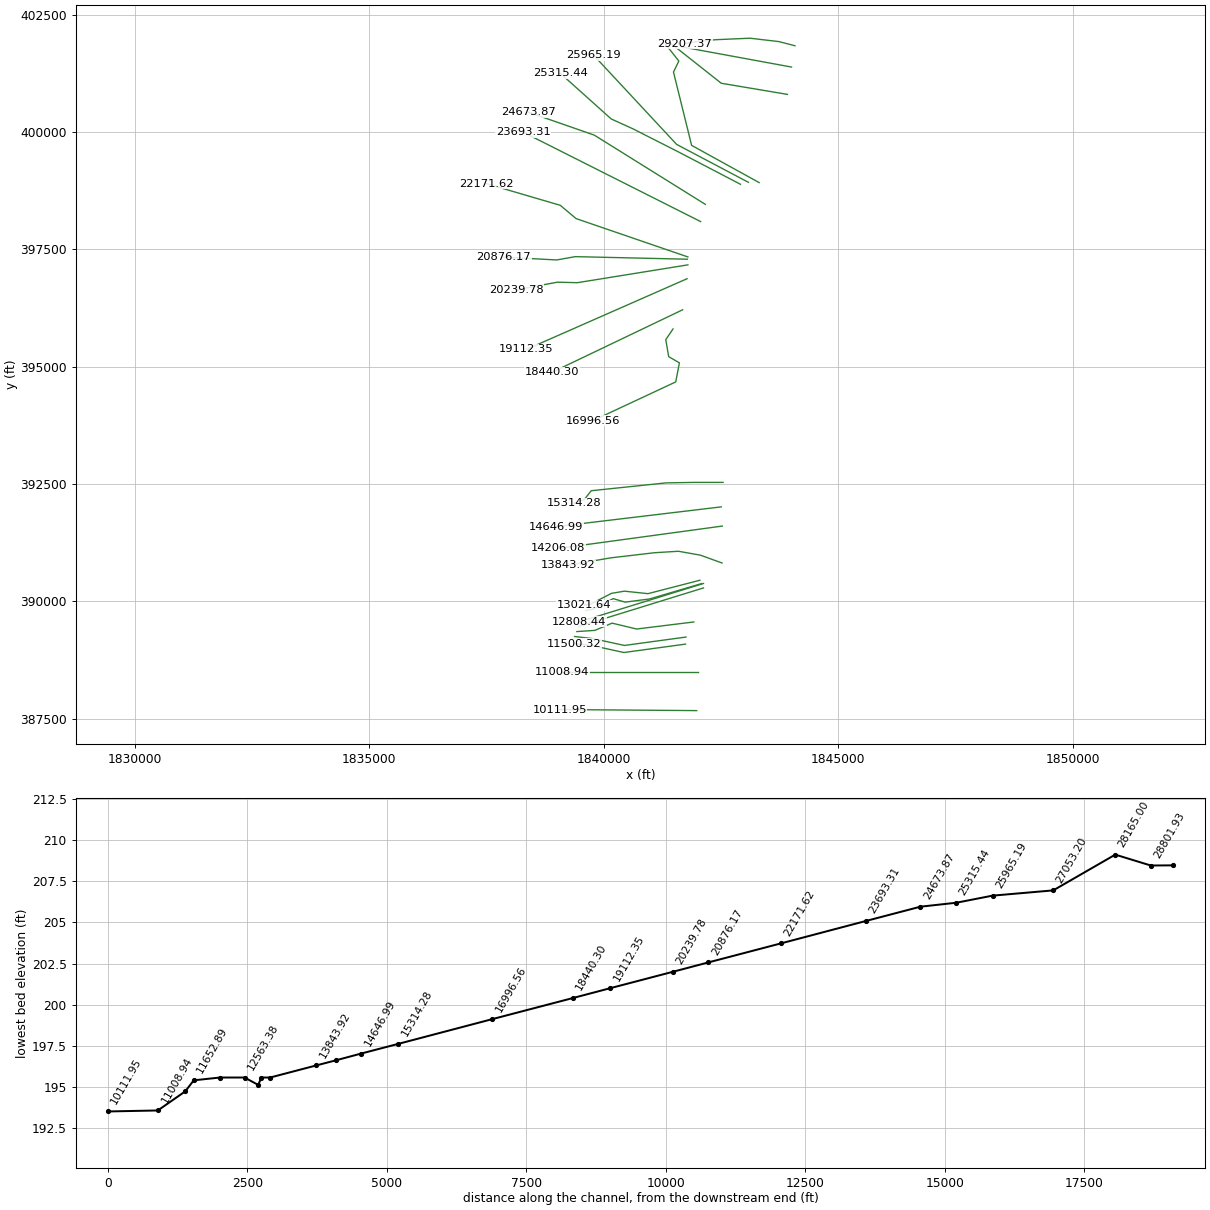
HEC-RAS study gum_limited.prj: Gum Swamp

--- gum_limited.g02 (geometry) --- (continued)

Type RM Length L Ch R = 3 ,29253.65,,,
BEGIN DESCRIPTION:
SR 1323 (NCDOT # 5)
END DESCRIPTION:
Bridge Culvert--1,0,-1,-1, 0
Deck Dist Width WeirC Skew NumUp NumDn MinLoCord MaxHiCord MaxSubmerge Is_Ogee
42.93,24,2.6,0, 60, 60,214.1,,.95,0,0,0,,
       0   42.19   85.42  161.08  219.04  287.28  413.38   436.9  452.31  540.38
  548.66     587  602.34  645.05  666.98   780.4   810.3   875.9  894.71  935.19
     961   974.9  990.44  1016.3 1034.74  1062.2 1104.59 1119.53    1145 1185.87
 1208.88  1255.2 1301.72 1406.56 1408.97 1433.19 1494.97 1498.85 1533.11 1584.14
 1633.55 1731.76 1765.54 1849.55 1863.08 1916.69 1955.04  1992.5 2004.51 2028.68
 2053.85 2079.72 2097.21 2137.95 2190.46 2211.97 2229.86 2263.42 2290.71 2374.44
  240.97  240.58  240.73  239.61  239.62  238.89  238.23  237.68  237.82  236.62
  236.19  235.62  234.42  232.67  231.24  227.33  227.15  225.26  225.45  224.89
  223.62  223.57  222.64  222.16  221.04   220.7   219.4  218.62  218.23  216.95
  216.81  214.98  214.37  214.78   214.8  215.06  214.76  214.82  214.38  214.51
   214.1  214.58  214.44  215.14  215.54  215.78  217.13  217.13  217.71  217.55
  219.21  219.14  219.59  219.73  221.24  221.13  221.58  222.95  222.93  223.98
                                                                                
                                                                                
                                                                                
                                  212.88  212.88  212.88
                                                                                
                                                                                
       0   42.19   85.42  161.08  219.04  413.38  540.38     587  602.34  645.05
  666.98   780.4   810.3   875.9  894.71  935.19     961   974.9  990.44  1016.3
 1034.74  1062.2 1119.53 1185.87 1208.88  1255.2 1301.72 1406.56 1419.48 1443.27
 1513.98 1520.67 1549.55 1584.14 1660.89 1740.41 1792.58 1829.83 1916.26 1916.69
  1945.4 1955.04 1972.32 2002.98 2004.51 2025.48 2043.91 2044.57 2061.35 2072.34
 2145.68 2190.46 2229.86 2242.51  2243.2 2263.42 2263.92 2264.54 2313.97 2374.44
  240.97  240.58  240.73  239.61  239.62  238.23  236.62  235.62  234.42  232.67
  231.24  227.33  227.15  225.26  225.45  224.89  223.62  223.57  222.64  222.16
  221.04   220.7  218.62  216.95  216.81  214.98  214.37  214.78   214.8  215.06
  214.76  214.82  214.38  214.58   214.1  214.58  214.44  215.01  215.34  215.79
  215.82  216.68   217.1  217.13  217.57  217.71  217.55  218.11   218.4  219.21
  219.57  220.94  221.13  221.58  222.11  222.15   222.8  222.95  222.93  223.67
                                                                                
                                                                                
                                                                  212.88  212.88
  212.88
                                                                                
                                                                                
BR Coef=-1 , 1 , 0 ,, 0 ,,,.8,0,1.2,0,
WSPro=,,,, 1 ,,,, 0 ,,,, 0 ,,,,-1 ,-1 ,-1 , 0 , 0 , 0 , 0 , 0
BC Design=,, 0 ,, 0 ,,,,,,

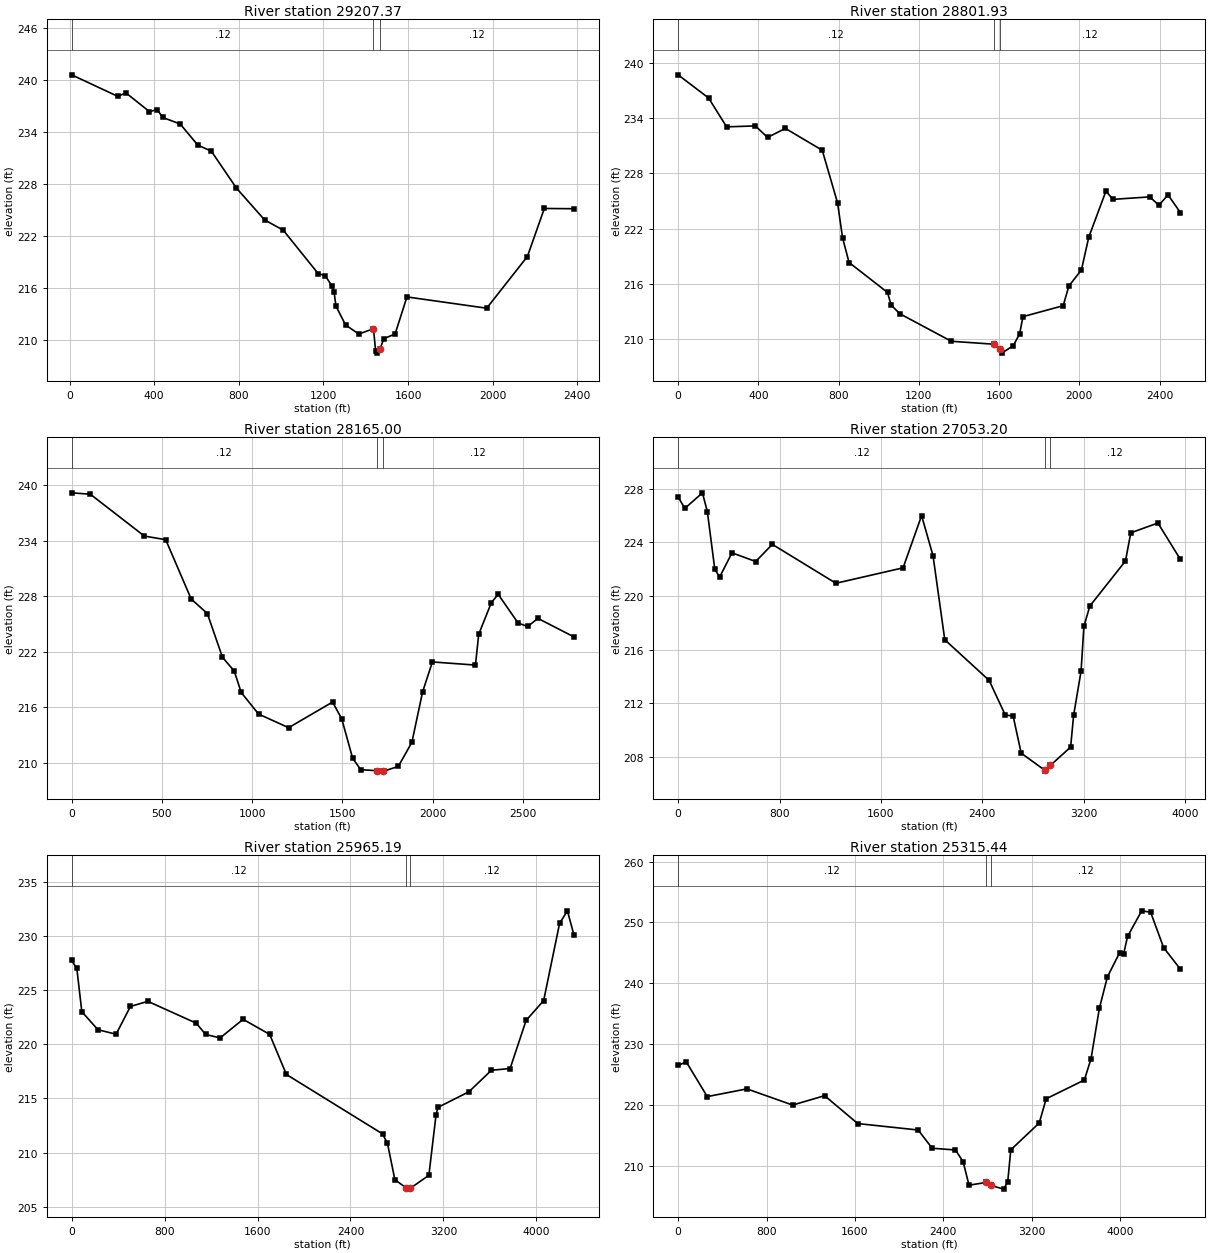
Type RM Length L Ch R = 1 ,29207.37,364.28,405.44,265.64
XS GIS Cut Line= 6
     1844076.733      401841.552       1843734.4      401930.156
       1843118.2       402002.65     1842381.176       401970.43
      1841853.58      401914.046     1841724.702      401885.854
#Sta/Elev= 30
     9.5  240.55   228.2  238.06  265.66  238.48  377.18  236.31  414.76  236.54
  439.31  235.64  522.68  234.88  606.24  232.44  669.85  231.75  788.66  227.49
  921.82  223.82 1009.83  222.64 1175.15  217.63 1208.11   217.4 1239.26  216.24
 1250.24  215.54    1259  213.89  1304.8   211.7 1367.63  210.66 1436.54  211.28
 1446.79   208.7 1451.73  208.46  1467.4  208.97 1485.93  210.13 1538.87  210.67
 1594.77  214.94 1971.89  213.64  2164.3   219.6  2244.4  225.14 2383.94  225.11
#Mann= 3 , 0 , 0
     9.5     .12       0 1436.54    .055       0  1467.4     .12       0
Bank Sta=1436.54,1467.4
Exp/Cntr=.5,.3

Type RM Length L Ch R = 1 ,28801.93,593.01,636.93,458.33
XS GIS Cut Line= 3
     1844002.666      401387.548     1841658.689      401818.486
      1841578.14       401907.09
#Sta/Elev= 30
       0  238.73  151.89  236.21  241.62  233.07  385.14  233.17  445.59  231.92
   534.8   232.9  718.42  230.52  794.51  224.81  819.71  220.99  852.06  218.31
 1043.96  215.05  1061.3  213.69 1104.55  212.74 1361.74  209.74 1574.39  209.42
 1601.92  208.89 1612.93  208.45 1670.74  209.26 1702.01  210.55 1718.96  212.42
 1919.23  213.61 1947.36  215.74 2010.29  217.51 2046.82  221.07 2132.25  226.07
 2167.17  225.18 2350.65  225.45 2396.35  224.54 2441.92  225.67 2503.01  223.75
#Mann= 3 , 0 , 0
       0     .12       0 1574.39    .055       0 1601.92     .12       0
Bank Sta=1574.39,1601.92
Exp/Cntr=.3,.1

Type RM Length L Ch R = 1 ,28165.00,926.43,1111.8,715.68
XS GIS Cut Line= 3
     1843915.158      400805.174     1842505.348      401042.259
     1841443.307      401881.555
#Sta/Elev= 30
       0  239.16  103.48  239.01  403.04  234.49  521.29   234.1  662.29   227.7
  752.11  226.12  835.72  221.41  900.88  219.92  939.87   217.6    1036  215.27
 1202.64   213.8  1446.1  216.57 1496.73  214.76 1557.17  210.51 1602.37  209.26
 1692.22  209.16 1722.83  209.12 1730.13  209.11 1810.38  209.62 1885.71  212.22
 1944.93  217.66 1999.29   220.9 2237.95  220.56    2256  223.88 2326.02   227.3
 2364.05   228.2 2474.33   225.1 2527.17  224.73 2584.44   225.6 2783.25  223.61
#Mann= 3 , 0 , 0
       0     .12       0 1692.22    .055       0 1722.83     .12       0
Bank Sta=1692.22,1722.83
Exp/Cntr=.3,.1

Type RM Length L Ch R = 1 ,27053.20,759.93,1088.01,1062.92
XS GIS Cut Line= 5
      1843312.52      398924.947     1841873.093      399718.369
      1841486.53      401281.258     1841601.031      401516.286
     1841323.818      401865.816
#Sta/Elev= 30
       0  227.37   52.96  226.52  191.89  227.68   230.7  226.27  289.41  221.98
  327.33   221.4  424.96  223.21  611.91  222.56     743  223.84 1244.75  220.94
 1774.52  222.09 1920.53  225.98 2010.76  222.99 2103.36  216.73 2453.44   213.7
 2581.47   211.1 2641.98  211.07 2706.01  208.28 2891.64  207.01 2892.43  206.94
 2935.21  207.36 3095.95  208.73 3119.95  211.12 3178.47   214.4 3200.98  217.75
 3248.04  219.25 3528.67   222.6 3570.53   224.7 3784.42  225.43 3961.15  222.73
#Mann= 3 , 0 , 0
       0     .12       0 2891.64    .055       0 2935.21     .12       0
Bank Sta=2891.64,2935.21
Exp/Cntr=.3,.1

Type RM Length L Ch R = 1 ,25965.19,451.4,649.75,642.39
XS GIS Cut Line= 3
     1843083.518      398930.973     1841553.379      399739.027
     1839787.094      401636.813
#Sta/Elev= 30
       0  227.76   44.59  227.02   87.52  223.03  225.76  221.36  382.66  220.94
  505.84  223.51  656.32  223.98 1072.88  221.96  1153.4  220.92 1278.24   220.6
 1475.87  222.32 1704.36  220.93 1848.69  217.22 2675.86  211.73 2718.76  210.85
 2782.38  207.49 2881.81  206.72 2898.27  206.62 2914.26  206.69 3075.06   207.9
 3136.29  213.45 3153.46  214.18 3419.74  215.62 3613.57  217.61  3774.4  217.77
 3912.04  222.22 4063.02  224.05 4200.35  231.19  4267.7  232.35 4322.96  230.15
#Mann= 3 , 0 , 0
       0     .12       0 2881.81    .055       0 2914.26     .12       0
Bank Sta=2881.81,2914.26
Exp/Cntr=.3,.1

Type RM Length L Ch R = 1 ,25315.44,569.93,641.56,511.53
XS GIS Cut Line= 5
      1842914.78      398888.788     1841589.511      399580.049
     1840624.759      400069.957     1840159.897      400280.902
     1839074.058      401254.136
#Sta/Elev= 30
       0  226.52   73.83  227.09  263.91  221.39  622.51  222.66 1036.41     220
 1326.06  221.54 1625.87  216.96 2172.92   215.9  2299.1  212.91 2510.51  212.62
 2579.93  210.68 2632.84  206.84 2790.86  207.29 2831.77  206.81 2945.33  206.19
  2983.2  207.37 3011.07  212.65 3268.33  217.05 3331.28  221.03 3677.12  224.12
 3737.56  227.63 3812.84   235.9 3885.74  241.07 3996.55  245.04  4032.1  244.79
 4067.96   247.7 4195.85  251.91 4276.93  251.68 4394.05  245.88 4545.38  242.34
#Mann= 3 , 0 , 0
       0     .12       0 2790.86    .055       0 2831.77     .12       0
Bank Sta=2790.86,2831.77
Exp/Cntr=.3,.1

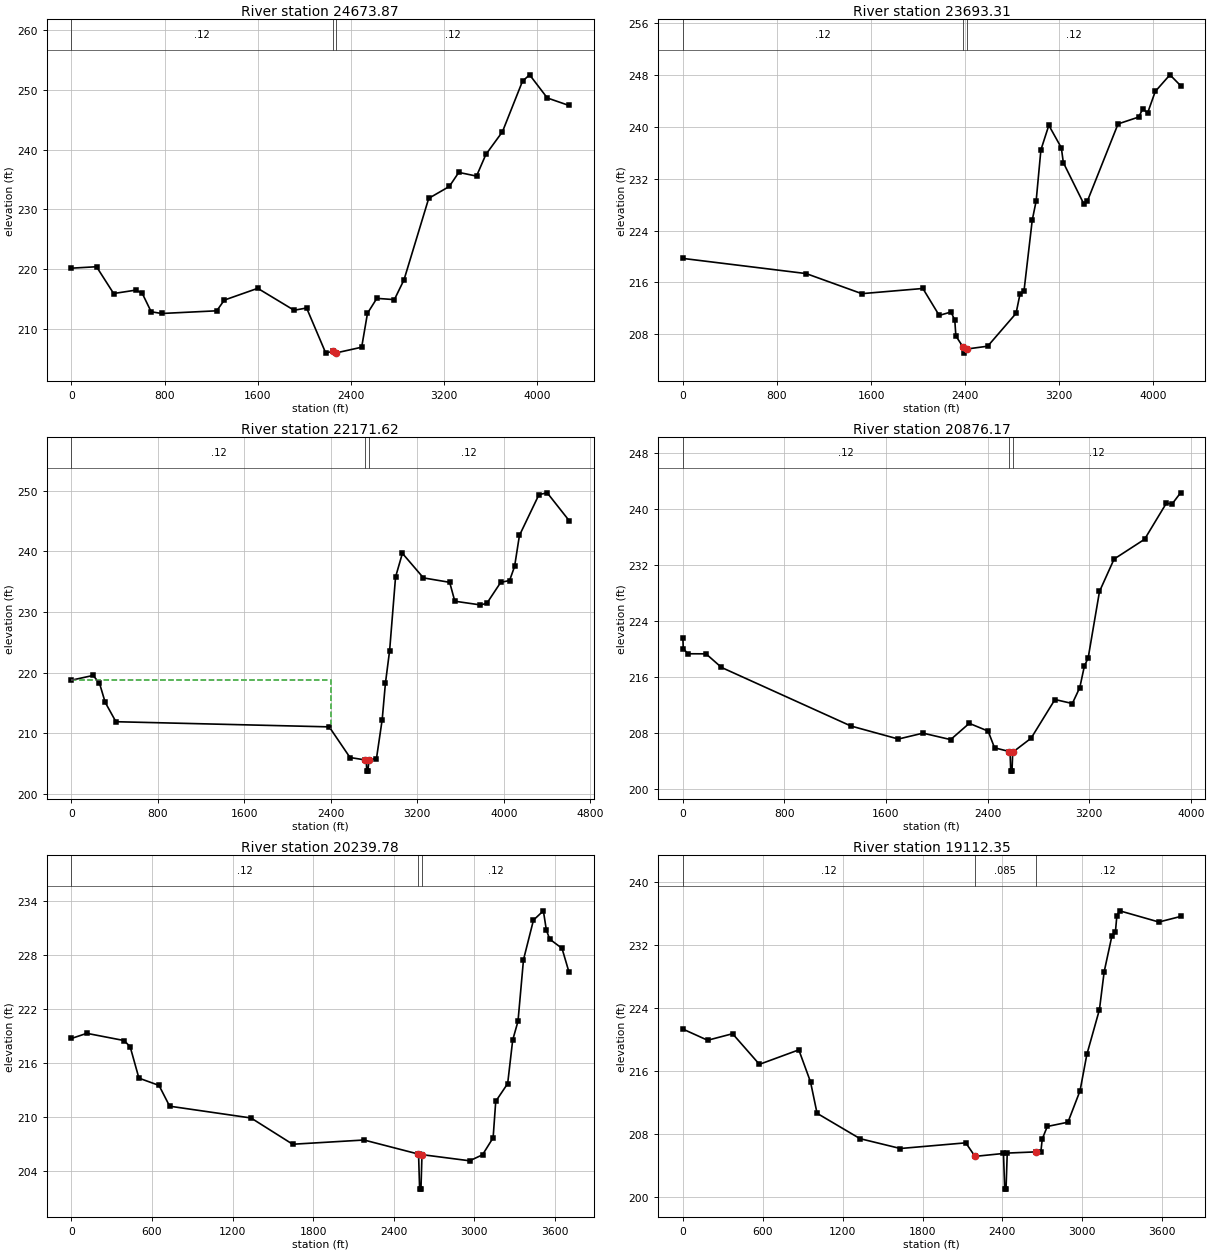
Type RM Length L Ch R = 1 ,24673.87,564.78,980.56,614.15
XS GIS Cut Line= 3
     1842165.215      398461.102     1839798.715      399936.684
     1838395.002      400425.513
#Sta/Elev= 30
       0  220.16  215.71   220.4  362.68  215.92  553.33  216.49  607.62  215.98
  685.04  212.87  774.97  212.58 1248.43  213.03 1313.35  214.82 1600.68  216.79
 1912.85  213.12 2020.29   213.5 2185.09  205.95  2244.5  206.27 2274.43  205.99
 2493.47  206.94 2543.35  212.62 2623.73  215.11 2774.31   214.9 2856.86   218.2
 3069.45  231.84  3246.5  233.83  3327.6  236.18 3480.06  235.56 3560.42  239.18
 3702.78  242.98 3875.19  251.44 3936.21   252.5 4088.11  248.63 4275.24  247.37
#Mann= 3 , 0 , 0
       0     .12       0  2244.5    .055       0 2274.43     .12       0
Bank Sta=2244.5,2274.43
Exp/Cntr=.3,.1

Type RM Length L Ch R = 1 ,23693.31,1099.67,1521.69,1076.24
XS GIS Cut Line= 4
     1842065.812      398093.556     1840128.448      399069.467
     1839706.069      399282.232     1838286.891      399997.117
#Sta/Elev= 30
       0   219.7 1048.15  217.36 1521.15  214.26 2040.46  215.06 2179.54   210.9
 2279.88  211.43 2312.05  210.15 2321.12  207.73 2382.21  206.02 2392.21  205.08
 2412.21  205.71 2591.77  206.15 2832.84  211.22 2866.02  214.17 2900.42  214.68
 2970.42   225.6 3003.74  228.57    3044  236.44 3111.45  240.25 3217.81  236.78
 3234.78  234.49 3408.78  228.12 3439.12  228.54 3700.03  240.46 3875.37  241.52
 3911.11  242.81 3951.08  242.13  4016.3  245.47 4141.29  248.04 4231.29  246.38
#Mann= 3 , 0 , 0
       0     .12       0 2382.21    .055       0 2412.21     .12       0
Bank Sta=2382.21,2412.21
Exp/Cntr=.3,.1

Type RM Length L Ch R = 1 ,22171.62,714.83,1295.45,1218.69
XS GIS Cut Line= 4
     1841793.875      397340.011     1839410.755      398157.579
     1839073.277      398440.625     1837494.753      398903.296
#Sta/Elev= 30
       0  218.74  200.77  219.52  259.63  218.24  312.33  215.08  411.67  211.88
 2385.41  211.03 2577.69  205.97 2720.68  205.56 2728.67  205.48 2732.19  203.72
 2742.19  203.72  2753.7  205.53 2822.61   205.8 2875.65  212.24 2905.27  218.21
 2944.35  223.64 2999.12  235.77 3062.38  239.69  3257.3  235.63 3499.97   234.9
 3547.55  231.78 3783.93  231.17 3843.81  231.43 3972.06  234.89 4054.35   235.2
 4100.52  237.52 4145.41  242.64 4326.38  249.39 4402.49  249.68 4604.86   245.1
#Mann= 3 , 0 , 0
       0     .12       0 2720.68    .055       0  2753.7     .12       0
#XS Ineff= 2 , 0
       0    2400   218.7               0
Bank Sta=2720.68,2753.7
Exp/Cntr=.3,.1

Type RM Length L Ch R = 1 ,20876.17,486.66,636.39,524.82
XS GIS Cut Line= 4
     1841781.822        397291.8     1839394.425      397346.544
     1838997.073      397275.783     1837870.333      397335.658
#Sta/Elev= 30
       0  221.63    3.06  220.07   39.59  219.32  182.23  219.31  304.03  217.37
 1323.59  209.01 1697.07  207.15 1891.34  207.99 2109.23  207.07 2255.78  209.39
 2404.53  208.28 2454.82   205.9 2570.99  205.37 2577.04  205.34 2582.58  202.57
 2592.58  202.57 2598.08  205.32 2604.17  205.35 2742.96  207.27 2930.74  212.79
 3067.71  212.22 3126.47   214.5 3162.96  217.59 3192.35  218.72  3281.6  228.21
  3396.7  232.84 3636.84  235.66 3807.88   240.8 3854.25  240.71 3919.96  242.29
#Mann= 3 , 0 , 0
       0     .12       0 2570.99    .055       0 2604.17     .12       0
Bank Sta=2570.99,2604.17
Exp/Cntr=.3,.1

Type RM Length L Ch R = 1 ,20239.78,723.46,1127.43,1097.5
XS GIS Cut Line= 4
     1841793.875      397171.273     1839437.971      396791.339
     1839013.402      396802.225     1838132.373      396639.318
#Sta/Elev= 30
       0  218.75  114.59  219.32  391.99  218.52   437.5  217.83  502.73  214.34
  652.58  213.53  731.53  211.22 1337.84  209.91 1648.05  206.99 2179.64  207.46
 2583.79   205.9 2585.83   205.9 2593.62     202 2603.62     202 2611.29  205.84
 2613.45  205.83 2966.42  205.15 3062.29  205.82  3141.2  207.71 3160.69  211.76
  3249.5  213.73    3287  218.57 3326.56  220.67 3367.45  227.51 3441.76  231.91
 3515.44  232.94  3537.8   230.8 3562.76  229.79 3654.32  228.77 3707.02  226.09
#Mann= 3 , 0 , 0
       0     .12       0 2583.79    .055       0 2613.45     .12       0
Bank Sta=2583.79,2613.45
Exp/Cntr=.3,.1

Type RM Length L Ch R = 1 ,19112.35,609.04,672.05,671.65
XS GIS Cut Line= 2
     1841775.921      396875.912     1838354.776      395370.667
#Sta/Elev= 30
       0  221.33  185.87  219.91  373.21  220.74  574.81  216.85  870.75  218.69
  958.72  214.62 1007.92  210.63 1330.55  207.41 1633.44  206.16 2124.65  206.88
    2194  205.16 2407.93  205.53    2417     201    2427     201 2436.17  205.58
 2649.99  205.73 2688.73  205.75 2699.08  207.37 2737.01  208.96 2892.12   209.5
 2982.81  213.49 3034.24  218.12 3128.57   223.8  3164.2  228.62 3221.58  233.11
 3248.22   233.6 3259.35  235.71 3281.05  236.35 3575.06  234.93 3737.65  235.63
#Mann= 3 , 0 , 0
       0     .12       0    2194    .085       0 2649.99     .12       0
Bank Sta=2194,2649.99
Exp/Cntr=.3,.1

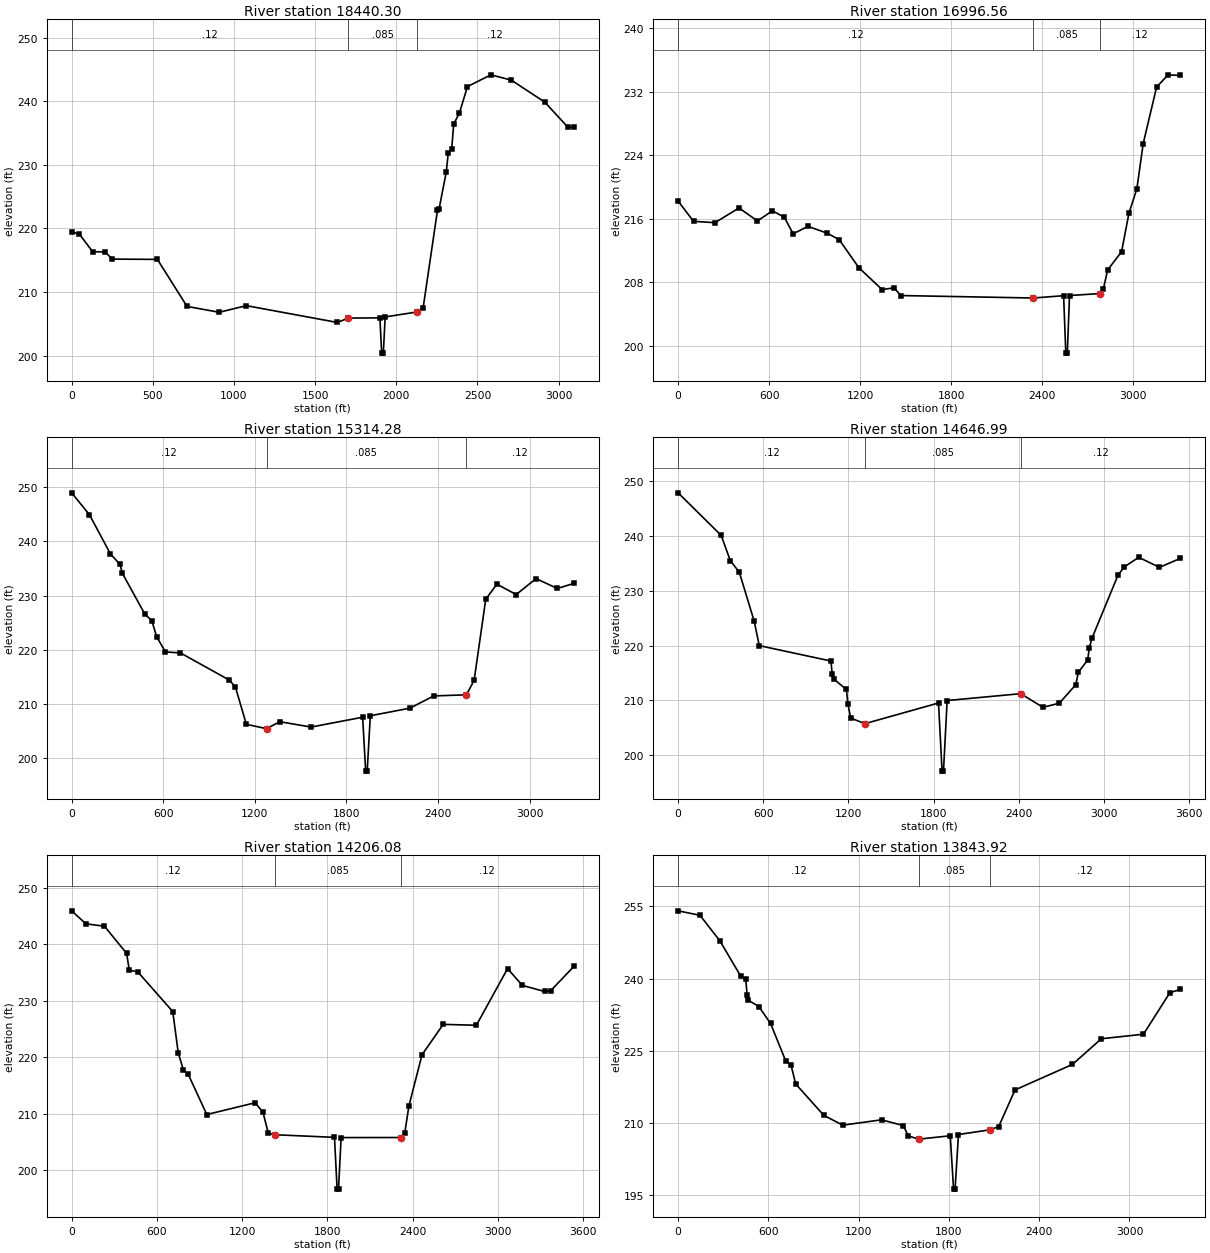
Type RM Length L Ch R = 1 ,18440.30,1378.27,1443.74,20921.76
XS GIS Cut Line= 2
     1841681.283      396213.449     1838890.946      394877.531
#Sta/Elev= 30
       0  219.45   47.34  219.11  129.88  216.33   206.5  216.31  249.96  215.18
  528.24  215.13  710.74  207.74  908.96  206.82 1076.17  207.86 1636.99  205.22
  1704.6  205.91 1898.89  205.94 1909.97   200.4 1919.97   200.4 1931.34  206.09
 2125.34  206.86 2165.62  207.57 2253.58  222.85 2263.37  223.05 2308.04  228.91
 2320.13  231.91 2341.19  232.43 2353.41  236.39 2389.06  238.16 2438.14  242.29
 2582.66  244.14 2708.07  243.31 2914.57  239.85 3057.17   235.9 3093.65  235.88
#Mann= 3 , 0 , 0
       0     .12       0  1704.6    .085       0 2125.34     .12       0
Bank Sta=1704.6,2125.34
Exp/Cntr=.3,.1

Type RM Length L Ch R = 1 ,16996.56,1886.59,1682.28,35351.56
XS GIS Cut Line= 6
     1841476.625      395805.234     1841321.812      395577.002
     1841384.999      395214.049     1841612.781      395082.831
     1841534.741      394676.355     1839769.015      393850.743
#Sta/Elev= 30
       0  218.23  101.93  215.69  243.28  215.52  401.46  217.37  523.15  215.74
  621.91  217.02  700.63   216.2  758.56  214.12  856.38  215.06  982.96   214.2
 1062.12  213.38 1192.74  209.84 1345.23  207.11 1423.63  207.33 1468.84  206.36
 2341.22  206.05 2542.01  206.34 2556.44  199.12 2566.44  199.12 2580.92  206.36
 2781.65  206.61 2804.23  207.21 2832.46  209.58 2924.18  211.87 2973.02  216.73
 3025.14  219.79 3066.83  225.47 3155.19  232.57 3230.56  234.11 3311.49  234.03
#Mann= 3 , 0 , 0
       0     .12       0 2341.22    .085       0 2781.65     .12       0
Bank Sta=2341.22,2781.65
Exp/Cntr=.3,.1

Type RM Length L Ch R = 1 ,15314.28,654.18,667.29,665.24
XS GIS Cut Line= 6
     1842543.113      392534.437      1841931.93      392534.437
      1841325.97       392523.99     1839732.714      392356.828
     1839586.448      392168.772     1839367.049      392090.415
#Sta/Elev= 30
       0  248.98   116.7  244.94  254.46  237.69  317.02  235.77  331.83  234.15
  480.07  226.57  525.26  225.39  557.44  222.39   614.7  219.62  713.05  219.43
 1034.04  214.41 1073.48   213.1 1144.57  206.26 1276.69  205.46 1364.32  206.74
 1568.26  205.75 1906.59  207.57 1926.49  197.62 1936.49  197.62 1956.94  207.84
 2216.18  209.24 2372.99   211.5 2586.29   211.7 2637.13  214.37 2713.17  229.34
 2786.04  232.12 2912.98  230.21 3042.97  233.15 3182.17  231.33 3290.45  232.26
#Mann= 3 , 0 , 0
       0     .12       0 1276.69    .085       0 2586.29     .12       0
Bank Sta=1276.69,2586.29
Exp/Cntr=.3,.1

Type RM Length L Ch R = 1 ,14646.99,433.77,440.9,455.4
XS GIS Cut Line= 2
     1842504.327      392012.834      1838991.37      391592.188
#Sta/Elev= 30
       0  247.92  303.07  240.15  367.62  235.53  431.24  233.39  535.97  224.44
  571.84  219.98 1077.03  217.16 1085.61  214.71  1097.2  213.85 1185.89  211.96
 1196.47  209.25 1215.99  206.73 1316.16  205.71 1834.64  209.49 1859.55  197.03
 1869.55  197.03 1895.36  209.94 2412.95  211.19 2570.73   208.7 2685.51  209.45
 2802.17  212.84  2819.7  215.12 2885.55  217.34 2896.79  219.63 2916.07  221.35
 3099.37  232.88 3142.82  234.35 3244.94  236.13  3391.2  234.29 3538.05  235.93
#Mann= 3 , 0 , 0
       0     .12       0 1316.16    .085       0 2412.95     .12       0
Bank Sta=1316.16,2412.95
Exp/Cntr=.3,.1

Type RM Length L Ch R = 1 ,14206.08,380.12,362.17,364.26
XS GIS Cut Line= 2
     1842527.065      391603.557     1839025.476      391126.068
#Sta/Elev= 30
       0  245.92   99.87  243.62   230.9  243.19   386.9  238.38  405.76  235.38
  463.92  235.15  711.57  228.08   750.1  220.76  786.76   217.7  818.08  217.09
     951  209.84 1291.57  211.93 1346.61  210.23 1383.82  206.53 1431.27  206.26
 1849.68   205.8 1868.02  196.63 1878.02  196.63 1896.27  205.76 2314.77  205.77
 2343.93  206.56 2373.33  211.35 2465.47  220.42 2614.78  225.81 2848.17  225.65
 3067.59  235.68 3171.85  232.71 3327.71  231.64 3371.68  231.79    3534  236.06
#Mann= 3 , 0 , 0
       0     .12       0 1431.27    .085       0 2314.77     .12       0
Bank Sta=1431.27,2314.77
Exp/Cntr=.3,.1

Type RM Length L Ch R = 1 ,13843.92,887.58,822.28,773.49
XS GIS Cut Line= 6
     1842522.218       390815.81     1842062.524      390982.971
     1841592.383      391066.552     1841080.452      391035.209
     1840145.393       390925.51     1839241.678      390768.796
#Sta/Elev= 30
       0  254.05  145.37  253.12  277.83  247.82  417.09  240.44  449.49  239.88
  458.54  236.64  466.56  235.51  536.33   234.2  614.36  230.69  714.78  222.94
  749.66  222.16   781.4  218.14  968.62  211.61 1094.09  209.58 1352.43  210.69
 1497.52  209.49 1529.57  207.36 1599.01  206.68 1808.88  207.38 1831.02  196.31
 1841.02  196.31 1863.67  207.64 2073.03  208.62 2131.11  209.29 2239.44  216.89
 2621.16  222.18 2813.24  227.51 3093.26  228.45 3269.12  237.07 3338.22  237.74
#Mann= 3 , 0 , 0
       0     .12       0 1599.01    .085       0 2073.03     .12       0
Bank Sta=1599.01,2073.03
Exp/Cntr=.5,.3

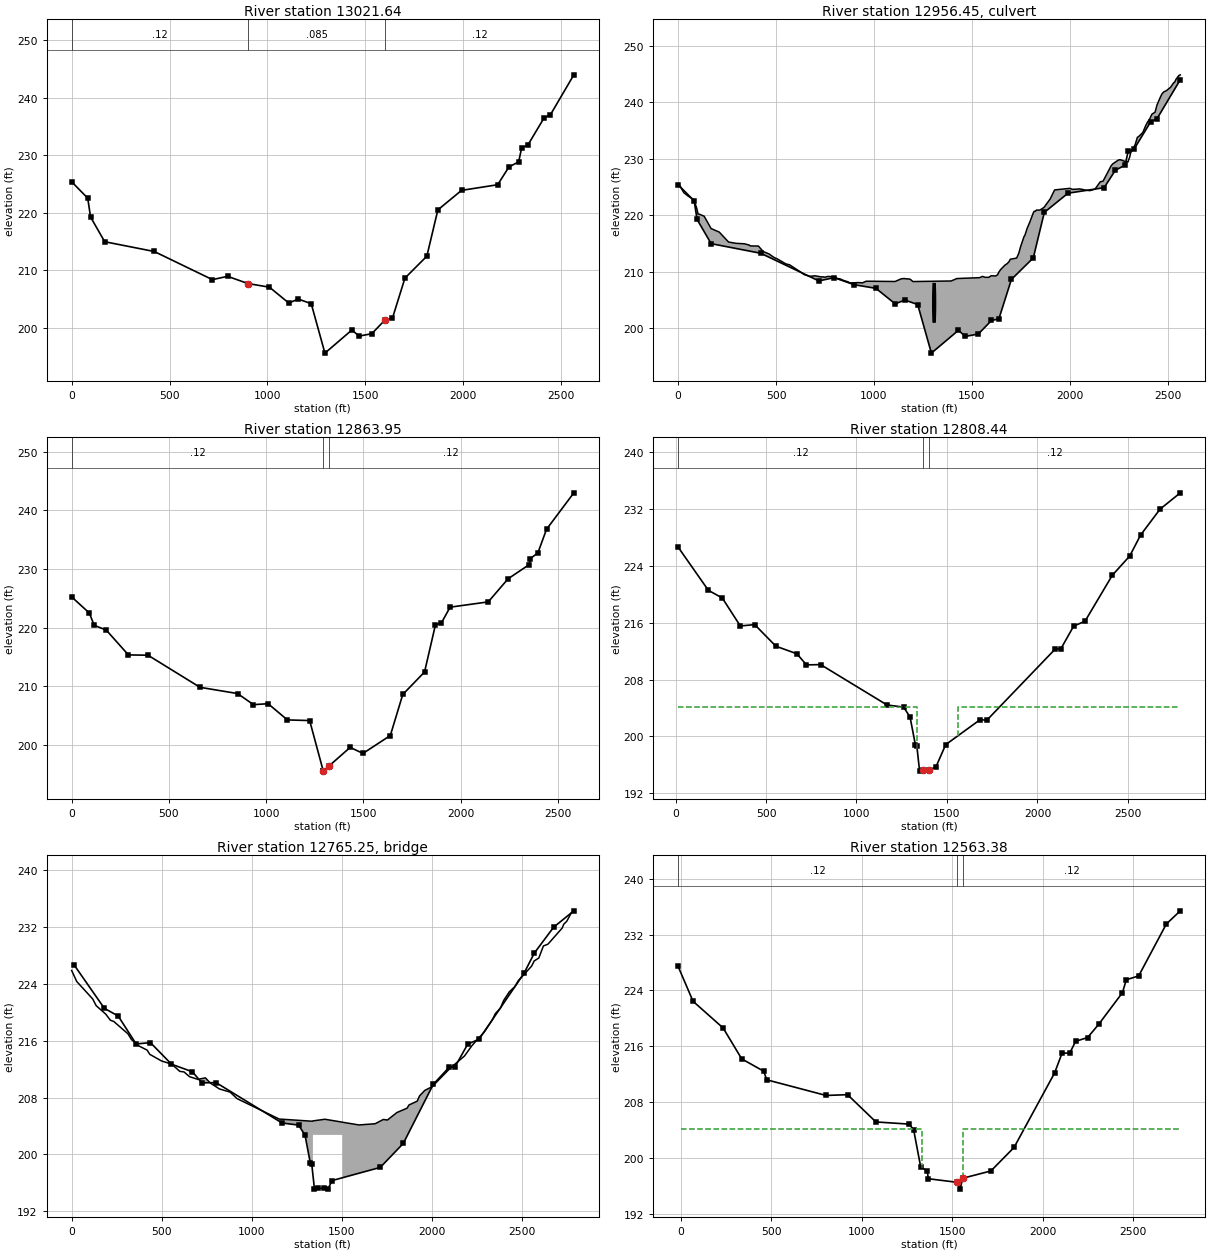
Type RM Length L Ch R = 1 ,13021.64,190.54,157.69,202.48
XS GIS Cut Line= 6
     1842048.978      390448.586     1840941.601      390162.718
      1840440.61      390216.137     1840166.022      390169.688
     1839713.067       389937.09     1839584.526      389918.727
#Sta/Elev= 30
       0  225.41   82.12  222.55   96.61  219.27  168.74  214.97  421.84  213.27
  718.98  208.37  796.65  208.95  900.33  207.69 1010.16  207.06 1109.12   204.3
 1157.44  204.99 1223.66  204.19 1293.65  195.58 1431.83  199.62 1467.34  198.54
 1533.16  198.96 1600.58  201.36  1638.3  201.64 1702.26  208.63 1814.25  212.46
 1870.44  220.51 1991.51  223.91 2175.94  224.89 2233.46  227.98 2283.22  228.88
 2298.54  231.31 2329.78  231.78  2413.2  236.53 2445.39  237.07 2565.03  244.02
#Mann= 3 , 0 , 0
       0     .12       0  900.33    .085       0 1600.58     .12       0
Bank Sta=900.33,1600.58
Exp/Cntr=.5,.3

Type RM Length L Ch R = 2 ,12956.45,,,
BEGIN DESCRIPTION:
Laurel Mill Dam (SCOTL-008)
END DESCRIPTION:
Bridge Culvert--1,0,-1,-1, 0
Deck Dist Width WeirC Skew NumUp NumDn MinLoCord MaxHiCord MaxSubmerge Is_Ogee
50.19,30,2.6,0,169,169,208,,.95,0,0,0,,
       0    8.51   10.66   20.74   29.04   50.31   50.73   51.05   55.51   70.98
   72.17   82.32   84.73   95.11     102   107.4  132.89  168.48  210.26  257.67
  296.32   338.6  363.34  368.98   410.1  434.07  464.34  489.25  507.98  550.19
  569.59  622.79   647.2  650.76  668.87  671.63  681.45  698.75  733.66  741.05
  745.13  752.57  764.19  775.72  776.44  801.31  806.09  815.16  826.62  846.32
  868.53  873.63  881.22  920.79  941.81  959.99  967.63 1098.27 1098.47  1108.3
 1128.42 1129.08 1135.02  1139.2 1140.41 1141.84 1143.68 1150.53 1158.34 1161.59
 1179.38 1183.11 1187.85 1199.19 1394.63 1401.71 1412.66 1421.93 1422.96 1495.11
 1518.71 1540.29 1554.93 1568.65 1572.27 1586.99 1598.91 1621.99 1631.23 1639.02
 1647.51  1669.9 1679.48 1689.66 1696.73 1729.15 1740.65 1748.12 1758.28 1766.26
 1771.57 1782.72 1791.53 1796.28 1814.41 1818.58 1824.42 1830.35 1847.34 1862.81
 1869.99 1900.38 1923.04 2000.45 2005.62 2013.45 2036.36 2047.26 2062.72  2077.8
 2094.58 2100.64 2102.62 2129.36  2156.3 2168.51 2171.09 2212.44 2214.61 2215.87
  2220.6 2243.25 2249.26  2255.7  2263.8 2284.85 2292.09 2296.82 2306.37 2311.56
 2319.82 2334.66 2345.97  2350.3 2355.47  2373.7 2387.61 2397.13 2407.61 2417.56
 2419.41    2421 2435.19 2436.31 2445.79 2464.81 2472.04 2481.45 2493.43 2512.35
 2514.54 2516.68 2530.62 2536.23  2544.1 2547.58 2549.96 2558.14 2565.03
  225.65  225.26  225.12   224.5     224  223.41   223.4   223.4   223.3  222.97
  222.92   222.7  222.31  221.23   220.2  220.21  219.84  217.65  217.02  215.26
  215.03  214.95  214.72  214.57  214.55  213.59  213.15  212.54  212.24  211.39
  211.22  210.01  209.43  209.44  209.21   209.2  209.21  209.28  209.07   209.1
  209.04  209.05  209.17  209.15  209.15  208.99  208.93  208.78  208.74  208.44
   208.2  208.06     208  208.08  208.03  208.31  208.32  208.29  208.29  208.27
  208.59  208.58  208.69  208.74  208.74  208.75  208.77  208.78  208.79  208.75
  208.71   208.7   208.6  208.26  208.36  208.46  208.63  208.77  208.79  208.88
   208.9  208.95  209.17     209  209.01  209.01  209.29  209.25  209.45  209.97
  210.39  211.19   211.4  211.75  212.21  212.42  213.33  214.31  215.39  216.18
  216.49  217.68  218.37  218.79  220.45  220.71   220.7  220.93  220.91  221.25
  221.45  222.89  224.49  224.77   224.7   224.6  224.62  224.68   224.6  224.47
  224.41  224.37  224.36  224.63  225.94  226.02  226.08  228.81   228.9  228.96
  229.12  229.65   229.8  229.84  229.79  229.51  229.52   229.4  230.29  231.09
  231.48  232.54  233.83  233.89  234.05  234.68  235.83  236.47  236.99  237.75
  237.87  237.93  238.24  238.27  239.53  241.05  241.54  241.88  242.06   242.6
  242.65  242.75  243.45  243.58  244.15  244.27  244.42  244.77  244.88
                                                                                
                                                                                
                                                                                
                                                                                
                                                                                
                                                                                
                                                                                
                                                                                
                                                                                
                                                                                
                                                                                
                                                                                
                                                                                
                                                                                
                                                                                
                                                                                
                                                                        
       0    8.51   10.66   20.74   29.04   50.31   50.73   51.05   55.51   70.98
   72.17   82.32   84.73   95.11     102   107.4  132.89  168.48  210.26  257.67
  296.32   338.6  363.34  368.98   410.1  434.07  464.34  489.25  507.98  550.19
  569.59  622.79   647.2  650.76  668.87  671.63  681.45  698.75  733.66  741.05
  745.13  752.57  764.19  775.72  776.44  801.31  806.09  815.16  826.62  846.32
  868.53  873.63  881.22  920.79  941.81  959.99  967.63 1098.27 1098.47  1108.3
 1128.42 1129.08 1135.02  1139.2 1140.41 1141.84 1143.68 1150.53 1158.34 1161.59
 1179.38 1183.11 1187.85 1199.19 1394.63 1401.71 1412.66 1421.93 1422.96 1495.11
 1518.71 1540.29 1554.93 1568.65 1572.27 1586.99 1598.91 1621.99 1631.23 1639.02
 1647.51  1669.9 1679.48 1689.66 1696.73 1729.15 1740.65 1748.12 1758.28 1766.26
 1771.57 1782.72 1791.53 1796.28 1814.41 1818.58 1824.42 1830.35 1847.34 1862.81
 1869.99 1900.38 1923.04 2000.45 2005.62 2013.45 2036.36 2047.26 2062.72  2077.8
 2094.58 2100.64 2102.62 2129.36  2156.3 2168.51 2171.09 2212.44 2214.61 2215.87
  2220.6 2243.25 2249.26  2255.7  2263.8 2284.85 2292.09 2296.82 2306.37 2311.56
 2319.82 2334.66 2345.97  2350.3 2355.47  2373.7 2387.61 2397.13 2407.61 2417.56
 2419.41    2421 2435.19 2436.31 2445.79 2464.81 2472.04 2481.45 2493.43 2512.35
 2514.54 2516.68 2530.62 2536.23  2544.1 2547.58 2549.96 2558.14 2565.03
  225.65  225.26  225.12   224.5     224  223.41   223.4   223.4   223.3  222.97
  222.92   222.7  222.31  221.23   220.2  220.21  219.84  217.65  217.02  215.26
  215.03  214.95  214.72  214.57  214.55  213.59  213.15  212.54  212.24  211.39
  211.22  210.01  209.43  209.44  209.21   209.2  209.21  209.28  209.07   209.1
  209.04  209.05  209.17  209.15  209.15  208.99  208.93  208.78  208.74  208.44
   208.2  208.06     208  208.08  208.03  208.31  208.32  208.29  208.29  208.27
  208.59  208.58  208.69  208.74  208.74  208.75  208.77  208.78  208.79  208.75
  208.71   208.7   208.6  208.26  208.36  208.46  208.63  208.77  208.79  208.88
   208.9  208.95  209.17     209  209.01  209.01  209.29  209.25  209.45  209.97
  210.39  211.19   211.4  211.75  212.21  212.42  213.33  214.31  215.39  216.18
  216.49  217.68  218.37  218.79  220.45  220.71   220.7  220.93  220.91  221.25
  221.45  222.89  224.49  224.77   224.7   224.6  224.62  224.68   224.6  224.47
  224.41  224.37  224.36  224.63  225.94  226.02  226.08  228.81   228.9  228.96
  229.12  229.65   229.8  229.84  229.79  229.51  229.52   229.4  230.29  231.09
  231.48  232.54  233.83  233.89  234.05  234.68  235.83  236.47  236.99  237.75
  237.87  237.93  238.24  238.27  239.53  241.05  241.54  241.88  242.06   242.6
  242.65  242.75  243.45  243.58  244.15  244.27  244.42  244.77  244.88
                                                                                
                                                                                
                                                                                
                                                                                
                                                                                
                                                                                
                                                                                
                                                                                
                                                                                
                                                                                
                                                                                
                                                                                
                                                                                
                                                                                
                                                                                
                                                                                
                                                                        
Multiple Barrel Culv=1,7,,30,.027,.7,1,2,2,201,201, 2,Culvert #1  , 0 ,50.19
 1303.69 1303.69 1311.69 1311.69
BC Design=,, 0 ,, 0 ,,,,,,

Type RM Length L Ch R = 1 ,12863.95,45.36,55.51,102.44
XS GIS Cut Line= 6
     1842082.497      390376.576     1840977.751       390049.94
     1840455.157      389982.192     1840202.172      390056.911
     1839749.218      389824.312     1839620.676      389805.949
#Sta/Elev= 30
       0  225.25   90.67  222.51  116.23   220.4  177.86   219.6   291.7  215.37
  392.29  215.32  660.13  209.85  852.94  208.79   934.9   206.9 1010.16  207.06
 1109.12   204.3 1223.66  204.19 1293.49   195.6 1293.65  195.58 1321.89  196.42
 1431.83  199.62 1497.67   198.6  1638.3  201.64 1702.26  208.63 1814.25  212.46
 1870.44  220.51 1901.12  220.83 1945.72   223.5 2141.72   224.4 2243.74  228.33
 2352.92  230.76 2358.21  231.77 2397.04  232.75 2441.38  236.76 2581.81  242.97
#Mann= 3 , 0 , 0
       0     .12       0 1293.49    .055       0 1321.89     .12       0
Bank Sta=1293.49,1321.89
Exp/Cntr=.5,.3

Type RM Length L Ch R = 1 ,12808.44,134.06,245.06,104.18
XS GIS Cut Line= 2
     1842125.825       390379.55     1839474.689      389560.417
#Sta/Elev= 30
    14.4  226.61  181.54  220.54  258.46  219.46  358.11  215.53  437.56  215.72
  554.36  212.69  670.69  211.62  723.51  210.06  801.92   210.1    1169  204.42
  1260.4  204.13 1296.05  202.72 1325.72  198.78 1333.34  198.68 1348.67  195.13
 1365.73  195.22 1399.02  195.27 1438.92  195.72 1492.82  198.85 1683.58  202.37
 1719.98  202.28 2096.58  212.25 2129.78  212.34 2199.89  215.51 2262.79   216.2
 2413.33  222.65 2509.73  225.36 2569.61   228.3 2677.08  231.94  2789.2  234.24
#Mann= 3 , 0 , 0
    14.4     .12       0 1365.73    .055       0 1399.02     .12       0
#XS Ineff= 2 , 0
       0    1335  204.15 1558.73       0  204.15
Bank Sta=1365.73,1399.02
Exp/Cntr=.5,.3

Type RM Length L Ch R = 3 ,12765.25,,,
BEGIN DESCRIPTION:
NC 144 / SR 1319 (NCDOT # 3)
END DESCRIPTION:
Bridge Culvert--1,0,-1,-1, 0
Deck Dist Width WeirC Skew NumUp NumDn MinLoCord MaxHiCord MaxSubmerge Is_Ogee
23.69,39,2.6,0, 60, 60,204.15,,.95,0,0,0,,
       0   28.17  116.71  136.19  189.52  214.86  234.03  312.99  332.21  374.46
  419.43   434.1  499.15  556.27  600.41  624.13  654.23  701.51  742.78  769.49
  820.72  880.35   918.6 1152.66  1337.2    1340 1406.61    1504  1506.7 1595.72
 1685.67 1731.06 1753.69 1806.16 1862.95 1873.64 1919.15 1932.42 1961.07 2001.71
 2102.27 2181.83  2223.6 2292.21 2336.24 2353.63 2381.62 2399.26 2430.91 2461.35
 2481.25 2554.74 2568.88 2594.71 2620.12 2645.63  2724.5 2733.44 2749.52  2774.8
  225.86  224.31  221.86  220.91  219.72  218.87  218.69  216.95  216.15  215.24
  214.66  214.07  213.14  212.69  211.68   211.6  210.94  210.55  210.77  210.05
  209.21  208.76  207.85  204.98  204.67  204.72  204.95  204.54  204.52  204.15
  204.32  204.92  204.84  205.89  206.51  206.96  207.49  208.24     209  209.52
  212.12  213.84  215.31  217.23   218.9  219.81  220.56  221.64  222.86  223.58
  224.44  226.47  227.19  227.61   229.3  229.56  231.82  232.37  232.76  233.93
                                                                                
                                                                                
                                          202.75  202.75  202.75
                                                                                
                                                                                
                                                                                
       0   28.17  116.71  136.19  189.52  214.86  234.03  312.99  332.21  374.46
  419.43   434.1  499.15  556.27  600.41  624.13  654.23  701.51  742.78  769.49
  820.72  880.35   918.6 1152.66  1337.2    1340 1406.61    1504  1506.7 1595.72
 1685.67 1731.06 1753.69 1806.16 1862.95 1873.64 1919.15 1932.42 1961.07 2001.71
 2102.27 2181.83  2223.6 2292.21 2336.24 2353.63 2381.62 2399.26 2430.91 2461.35
 2481.25 2554.74 2568.88 2594.71 2620.12 2645.63  2724.5 2733.44 2749.52  2774.8
  225.86  224.31  221.86  220.91  219.72  218.87  218.69  216.95  216.15  215.24
  214.66  214.07  213.14  212.69  211.68   211.6  210.94  210.55  210.77  210.05
  209.21  208.76  207.85  204.98  204.67  204.72  204.95  204.54  204.52  204.15
  204.32  204.92  204.84  205.89  206.51  206.96  207.49  208.24     209  209.52
  212.12  213.84  215.31  217.23   218.9  219.81  220.56  221.64  222.86  223.58
  224.44  226.47  227.19  227.61   229.3  229.56  231.82  232.37  232.76  233.93
                                                                                
                                                                                
                                          202.75  202.75  202.75
                                                                                
                                                                                
                                                                                
BR Coef=-1 , 1 , 0 ,, 0 ,,,.8,0,1.2,0,
WSPro=,,,, 1 ,,,, 0 ,,,, 0 ,,,,-1 ,-1 ,-1 , 0 , 0 , 0 , 0 , 0
BR U #Sta/Elev= 30
    14.4  226.61  181.54  220.54  258.46  219.46  358.11  215.53  437.56  215.72
  554.36  212.69  670.69  211.62  723.51  210.06  801.92   210.1    1169  204.42
  1260.4  204.13 1296.05  202.72 1325.72  198.78 1333.34  198.68 1348.67  195.13
 1365.73  195.22 1399.02  195.27 1423.96  195.19 1447.46  196.34 1713.96  198.18
 1841.93  201.55  2008.6  209.86 2096.58  212.25 2129.78  212.34 2199.89  215.51
 2262.79   216.2 2511.92  225.44 2569.61   228.3 2677.08  231.94  2789.2  234.24
BR U #Mann= 3
    14.4     .12 1365.73    .055 1399.02     .12
BR D #Sta/Elev= 30
    14.4  226.61  181.54  220.54  258.46  219.46  358.11  215.53  437.56  215.72
  554.36  212.69  670.69  211.62  723.51  210.06  801.92   210.1    1169  204.42
  1260.4  204.13 1296.05  202.72 1325.72  198.78 1333.34  198.68 1348.67  195.13
 1365.73  195.22 1399.02  195.27 1423.96  195.19 1447.46  196.34 1713.96  198.18
 1841.93  201.55  2008.6  209.86 2096.58  212.25 2129.78  212.34 2199.89  215.51
 2262.79   216.2 2511.92  225.44 2569.61   228.3 2677.08  231.94  2789.2  234.24
BR D #Mann= 3
    14.4     .12 1365.73    .055 1399.02     .12
BR D Banks=1365.73,1399.02
BC Design=,, 0 ,, 0 ,,,,,,

Type RM Length L Ch R = 1 ,12563.38,521.75,440.42,347.36
XS GIS Cut Line= 2
      1842125.78      390284.821     1839474.644      389465.689
#Sta/Elev= 30
   -14.4  227.44    68.1  222.45  234.33  218.63  337.04  214.21  458.96  212.44
  474.96  211.22  803.18  208.98  921.81  209.09 1078.61  205.19 1262.35  204.88
 1287.09  204.06 1325.72  198.78 1363.17  198.14 1367.45  197.07 1528.73  196.55
 1542.92  195.58 1558.73  197.14 1713.96  198.18 1841.93  201.55 2066.07  212.21
 2107.08  215.04 2149.19  215.04 2182.43  216.73 2248.06  217.26 2308.93  219.14
 2440.65  223.68 2461.94  225.53 2530.31  226.08 2683.35  233.51  2760.4  235.39
#Mann= 3 , 0 , 0
   -14.4     .12       0 1528.73    .055       0 1558.73     .12       0
#XS Ineff= 2 , 0
       0    1335  204.15 1558.73       0  204.15
Bank Sta=1528.73,1558.73
Exp/Cntr=.5,.3

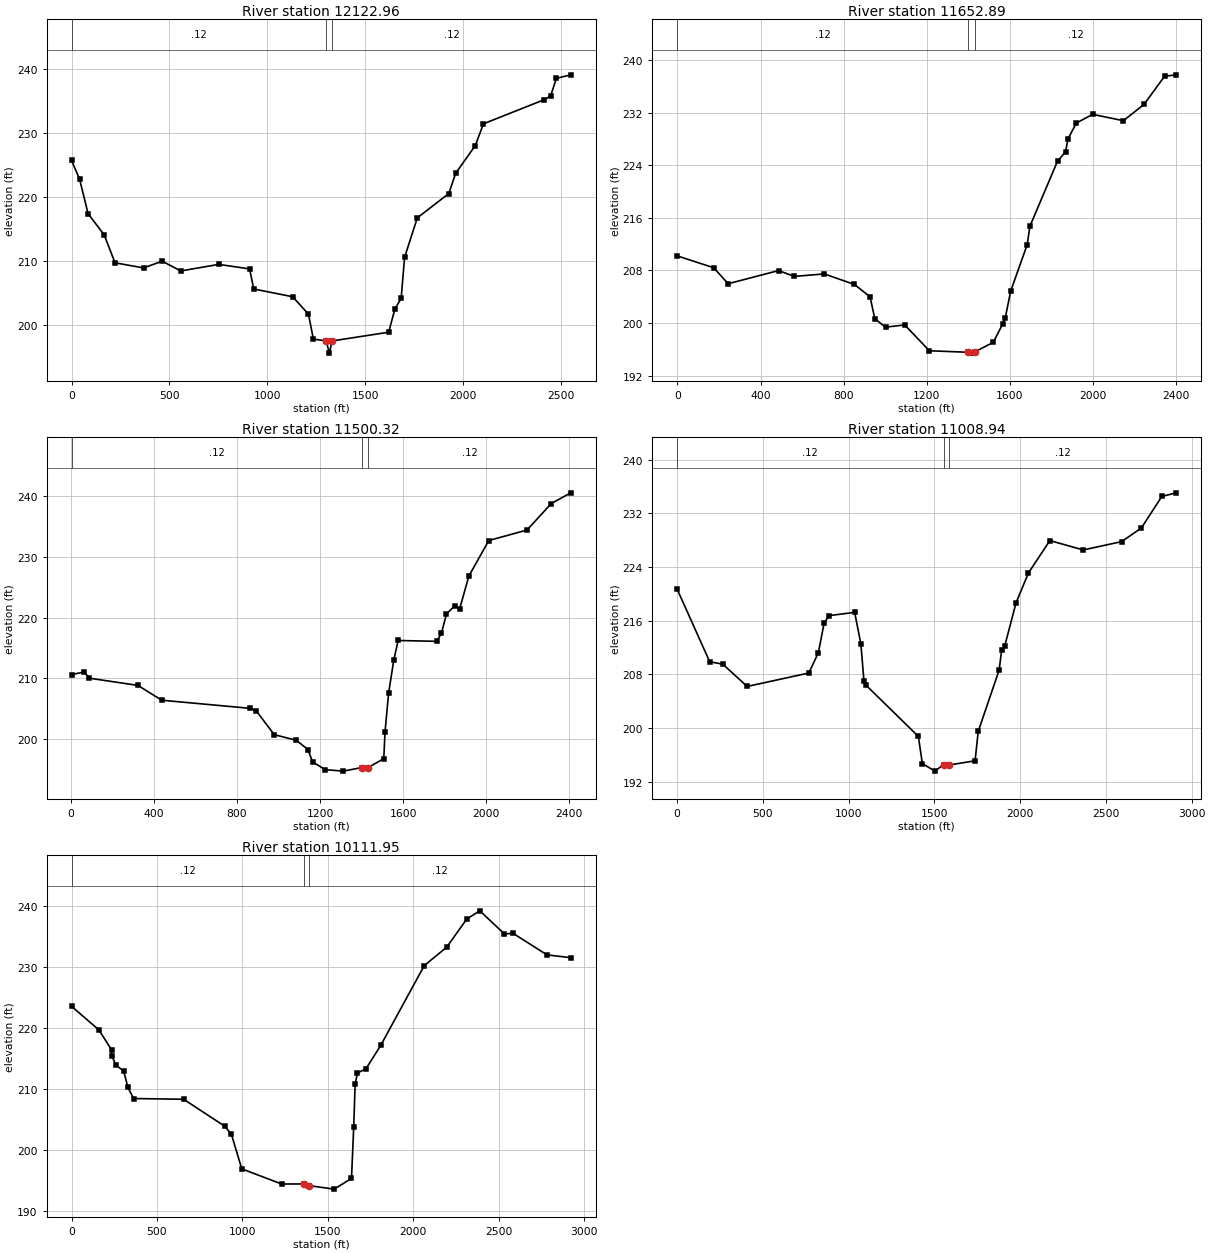
Type RM Length L Ch R = 1 ,12122.96,363.73,470.07,427.76
XS GIS Cut Line= 5
     1841920.437      389559.489      1840700.16      389409.043
     1840177.781      389534.414     1839810.026       389379.79
     1839425.555      389354.716
#Sta/Elev= 30
       0  225.74   41.58  222.77   84.73  217.39   166.8  214.09  222.39  209.71
  368.01  208.91  463.16  209.96  558.11  208.44  752.37  209.46  909.75  208.76
   931.2  205.62 1129.83   204.4  1210.7  201.68 1235.75  197.77 1300.99   197.5
  1317.4  195.58  1331.6  197.49 1620.38  198.85 1652.25  202.48  1684.2  204.15
 1701.81  210.57 1766.73  216.74 1927.58  220.55 1962.68  223.71 2062.83  228.05
 2104.76  231.46 2416.14  235.24 2448.21  235.83 2477.11  238.57 2550.96  239.12
#Mann= 3 , 0 , 0
       0     .12       0 1300.99    .055       0  1331.6     .12       0
Bank Sta=1300.99,1331.6
Exp/Cntr=.3,.1

Type RM Length L Ch R = 1 ,11652.89,148.43,152.57,153.89
XS GIS Cut Line= 4
     1841753.926      389237.763     1840439.788      389058.881
     1839789.081      389201.037     1839378.973      389250.005
#Sta/Elev= 30
   -2.55  210.22   174.2   208.4   244.2  205.97  486.82  207.97  562.98  207.08
  707.16  207.46  852.38  205.86  927.83  203.97  950.58  200.63  1002.6  199.36
 1094.52   199.7 1213.42  195.77 1399.76  195.54 1415.31  195.41 1431.03  195.58
 1521.34  197.05 1566.29  199.83 1579.43  200.82 1605.02  204.83 1684.58  211.91
 1697.85  214.72 1830.69  224.61 1869.39  226.03 1881.26     228 1921.58  230.42
 2000.15  231.74 2148.03  230.77  2247.5  233.25 2346.41  237.53 2402.78  237.75
#Mann= 3 , 0 , 0
   -2.55     .12       0 1399.76    .055       0 1431.03     .12       0
Bank Sta=1399.76,1431.03
Exp/Cntr=.3,.1

Type RM Length L Ch R = 1 ,11500.32,434.57,491.38,449.44
XS GIS Cut Line= 4
     1841743.547      389087.259     1840429.409      388908.378
     1839778.702      389050.533     1839368.594      389099.501
#Sta/Elev= 30
    2.55  210.64   63.03  211.04   89.16  210.03  322.41  208.85  437.27  206.41
  864.24  205.07  892.64  204.66  979.17  200.74 1085.36  199.82 1141.65  198.29
 1163.78  196.27  1224.7  194.98 1312.12  194.74 1399.67  195.32 1431.12  195.33
 1506.93  196.79 1512.82  201.12 1530.05  207.55 1555.08  213.02 1576.07  216.24
 1761.88   216.1 1784.75  217.43 1809.04  220.62 1848.95  221.94 1872.11   221.4
 1917.02  226.86 2012.82  232.69 2197.09  234.42  2313.9  238.78 2407.88  240.54
#Mann= 3 , 0 , 0
    2.55     .12       0 1399.67    .055       0 1431.12     .12       0
Bank Sta=1399.67,1431.12
Exp/Cntr=.3,.1

Type RM Length L Ch R = 1 ,11008.94,869.85,896.99,869.46
XS GIS Cut Line= 2
     1842015.469      388499.877     1839105.058      388499.877
#Sta/Elev= 30
       0  220.75  190.88  209.88  267.63  209.51  408.99   206.2  768.76   208.2
  824.27  211.24  857.63  215.62  886.17  216.75 1035.85  217.24 1072.08  212.51
 1089.84  207.05    1100  206.43  1407.2  198.75 1430.35   194.7 1504.23  193.58
 1554.16  194.56 1583.26  194.48 1737.74  195.12 1755.98  199.49 1878.07  208.65
 1892.35  211.57 1909.89  212.16 1976.66  218.67 2048.99  223.12 2173.54  227.93
 2368.81  226.54 2592.04  227.78 2707.06  229.81 2826.37  234.51 2910.41  235.05
#Mann= 3 , 0 , 0
       0     .12       0 1554.16    .055       0 1583.26     .12       0
Bank Sta=1554.16,1583.26
Exp/Cntr=.3,.1

Type RM Length L Ch R = 1 ,10111.95,823.64,992.9,906.6
XS GIS Cut Line= 2
     1841981.363      387669.955     1839059.583      387692.692
#Sta/Elev= 30
       0  223.57  160.31  219.69   234.4  216.41  236.26  215.38  259.58  213.93
  305.39   212.9  330.09  210.25  363.12  208.41  655.93  208.29  896.81  203.86
  936.08  202.51  996.36  196.85 1230.13  194.36 1361.19  194.37 1391.32  194.09
 1537.19  193.52  1638.5  195.28 1651.46  203.67 1659.73  210.74 1673.44   212.6
  1723.8  213.32 1809.26  217.13 2064.26  230.25  2196.2   233.3 2312.92  237.91
 2389.45  239.26 2533.55  235.46 2583.25  235.57 2782.49  232.02 2921.87  231.56
#Mann= 3 , 0 , 0
       0     .12       0 1361.19    .055       0 1391.32     .12       0
Bank Sta=1361.19,1391.32
Exp/Cntr=.3,.1