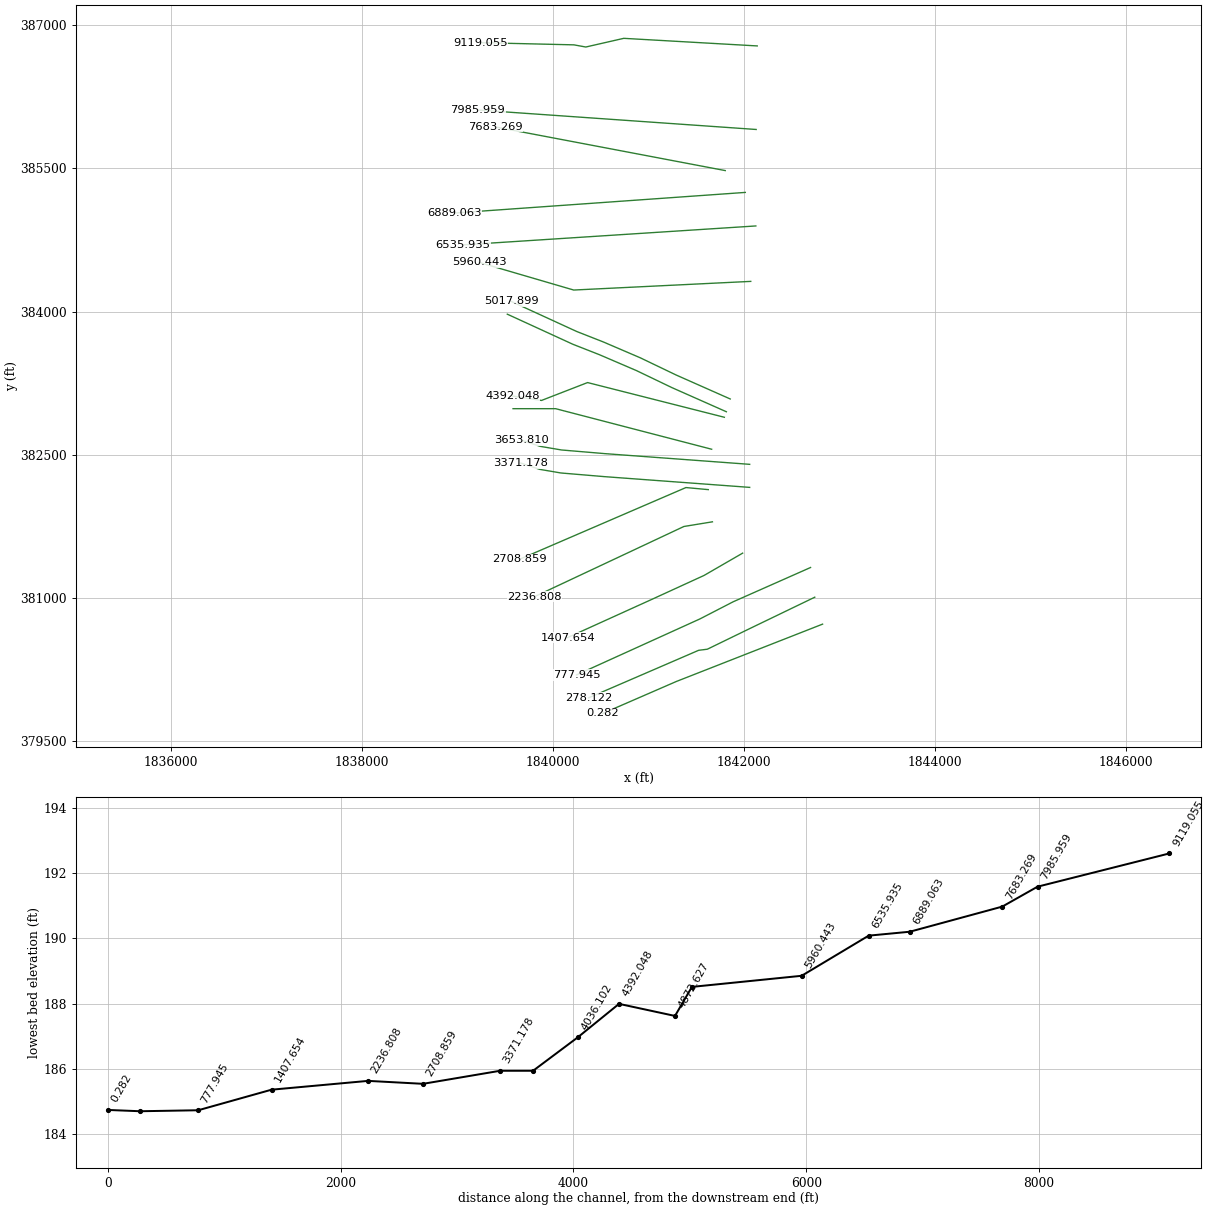
HEC-RAS study gum_limited.prj: Gum Swamp

--- gum_limited.g02 (geometry) --- (continued)

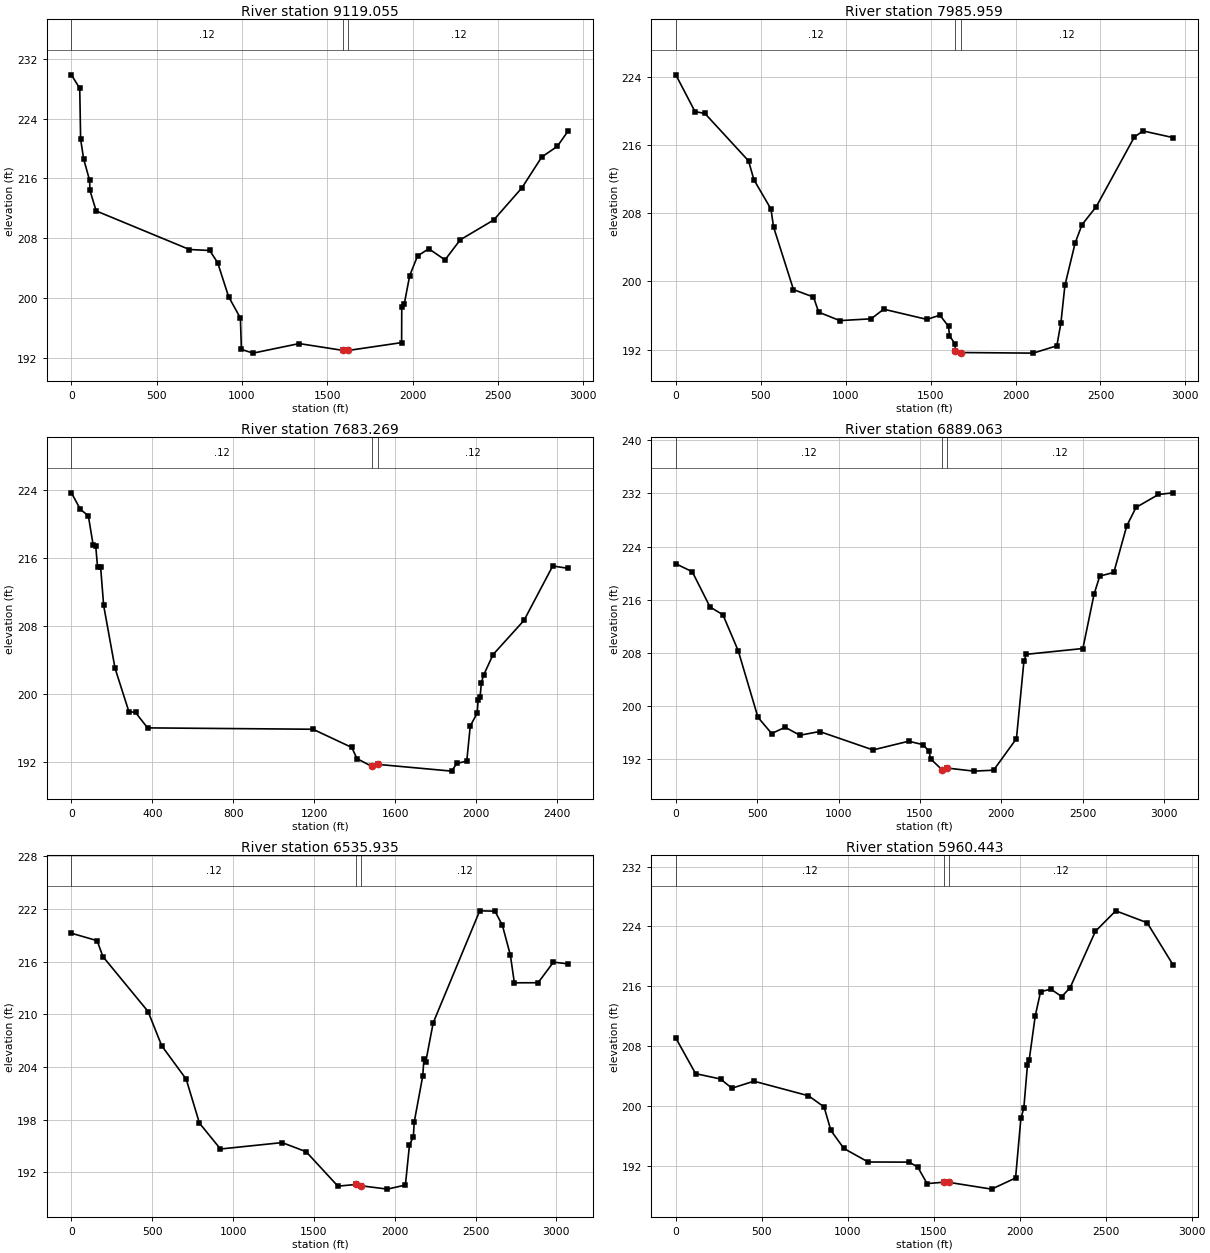
Type RM Length L Ch R = 1 ,9119.055,860.68,1133.1,779.41
XS GIS Cut Line= 5
     1842140.526      386783.189     1840742.164       386862.77
     1840344.256       386771.82       1840219.2      386794.558
     1839241.483      386817.295
#Sta/Elev= 30
       0  229.88   48.91  228.07   54.14  221.25   71.65  218.63  106.86  215.73
  108.67   214.4  145.15  211.65  692.03  206.48  810.82  206.35  857.36  204.72
  921.79  200.15  990.79   197.3  996.65   193.1 1064.85   192.6 1335.46  193.88
 1590.71  192.97 1623.59  192.96  1935.9  194.01 1936.72  198.74 1951.71  199.23
 1983.34  202.99  2029.4  205.62 2095.27  206.58 2190.36  205.09 2279.84  207.78
 2475.97  210.44 2641.41  214.75 2757.38  218.87 2848.74   220.3 2913.88  222.42
#Mann= 3 , 0 , 0
       0     .12       0 1590.71    .055       0 1623.59     .12       0
Bank Sta=1590.71,1623.59
Exp/Cntr=.3,.1

Type RM Length L Ch R = 1 ,7985.959,339.1,302.69,253.05
XS GIS Cut Line= 2
     1842129.157      385907.792     1839210.079      386112.116
#Sta/Elev= 30
       0  224.27  112.95  219.95  171.31  219.73  428.19  214.16  459.79  211.94
  560.27   208.5  575.32   206.4  692.71  199.04  810.37  198.17   841.2  196.39
   965.6   195.4 1149.85  195.61 1223.98  196.74 1478.44  195.54 1554.67  196.04
 1605.68  194.71 1611.18  193.62 1644.54  192.64 1644.92  191.81 1677.15  191.65
 2103.81  191.58 2243.14  192.44 2266.88   195.1 2290.77  199.55    2351  204.52
 2391.38  206.67  2475.8   208.8 2699.28  216.96 2750.24  217.68 2926.22   216.9
#Mann= 3 , 0 , 0
       0     .12       0 1644.92    .055       0 1677.15     .12       0
Bank Sta=1644.92,1677.15
Exp/Cntr=.3,.1

Type RM Length L Ch R = 1 ,7683.269,501.34,794.21,684.96
XS GIS Cut Line= 2
     1841805.166      385477.162     1839393.147      385935.141
#Sta/Elev= 30
       0  223.66   44.35  221.72   83.71  220.96   107.7   217.5  120.21  217.38
   129.5   214.9  144.27  214.95  159.36  210.43  215.62  203.05  283.86  197.97
  316.73  197.86  376.26  196.05 1193.22  195.89 1385.02  193.75 1410.46  192.44
 1482.89  191.54  1514.8  191.76 1878.23  190.97 1903.41  191.87 1952.92  192.15
  1970.1  196.27    2004  197.77 2009.29  199.35 2018.57  199.69 2025.38  201.37
 2035.93  202.24  2082.8  204.66 2235.71  208.68  2377.6  215.07 2455.11  214.78
#Mann= 3 , 0 , 0
       0     .12       0 1482.89    .055       0  1514.8     .12       0
Bank Sta=1482.89,1514.8
Exp/Cntr=.3,.1

Type RM Length L Ch R = 1 ,6889.063,354.2,353.13,346.76
XS GIS Cut Line= 2
     1842015.469      385248.402     1838968.632      385032.395
#Sta/Elev= 30
       0   221.4  100.89  220.21  210.22   214.9  289.44  213.73  383.66   208.3
  504.64   198.3  588.95  195.86  671.92   196.8  762.63   195.6  883.64  196.16
 1211.54  193.39 1430.91   194.7 1519.66  194.18  1556.5  193.16 1565.35  192.05
  1637.2  190.38 1667.75  190.66 1832.02   190.2 1952.75  190.34 2093.22  195.09
 2139.31  206.78 2153.74  207.78 2501.45  208.65 2570.37  216.84  2605.1  219.54
 2691.78  220.11 2771.27  227.12 2828.14  229.88 2966.03  231.83 3054.48  232.08
#Mann= 3 , 0 , 0
       0     .12       0  1637.2    .055       0 1667.75     .12       0
Bank Sta=1637.2,1667.75
Exp/Cntr=.3,.1

Type RM Length L Ch R = 1 ,6535.935,560.23,575.49,549.27
XS GIS Cut Line= 2
     1842125.751      384897.057     1839057.296      384698.599
#Sta/Elev= 30
       0  219.23  159.18  218.38  194.84  216.57  474.41  210.31  558.43  206.42
  710.28   202.6  792.07   197.6  922.19  194.65 1303.73  195.38 1452.19  194.34
 1648.48  190.42  1761.9  190.61 1792.65  190.46 1955.11  190.08 2066.34  190.55
 2091.55  195.12 2115.48  196.04 2120.89  197.73 2173.81  202.99 2180.56  204.88
 2192.14  204.58 2238.28  209.03 2526.14  221.78 2620.46  221.74 2666.28  220.13
 2715.88  216.71 2740.29  213.58 2887.06  213.59 2982.23  215.94 3074.87  215.73
#Mann= 3 , 0 , 0
       0     .12       0  1761.9    .055       0 1792.65     .12       0
Bank Sta=1761.9,1792.65
Exp/Cntr=.3,.1

Type RM Length L Ch R = 1 ,5960.443,850.85,942.54,512.8
XS GIS Cut Line= 3
     1842072.313      384316.161       1840217.5      384225.512
     1839225.222      384515.408
#Sta/Elev= 30
       0  209.06  114.98   204.3  259.91  203.58  326.15  202.35  454.34  203.29
  771.49  201.34  862.19  199.85  901.78   196.7  977.36  194.29 1118.56  192.48
 1356.56  192.46 1406.46  191.82 1461.36  189.59 1561.02  189.78 1589.93  189.75
 1836.55  188.85 1975.91  190.34 2006.86  198.32 2023.92  199.69 2044.96  205.42
  2055.3  206.14 2090.24     212 2121.39  215.26 2180.77   215.6 2244.68  214.61
 2293.04  215.79 2440.29  223.34 2558.65  226.08  2741.1  224.49 2890.79  218.89
#Mann= 3 , 0 , 0
       0     .12       0 1561.02    .055       0 1589.93     .12       0
Bank Sta=1561.02,1589.93
Exp/Cntr=.5,.3

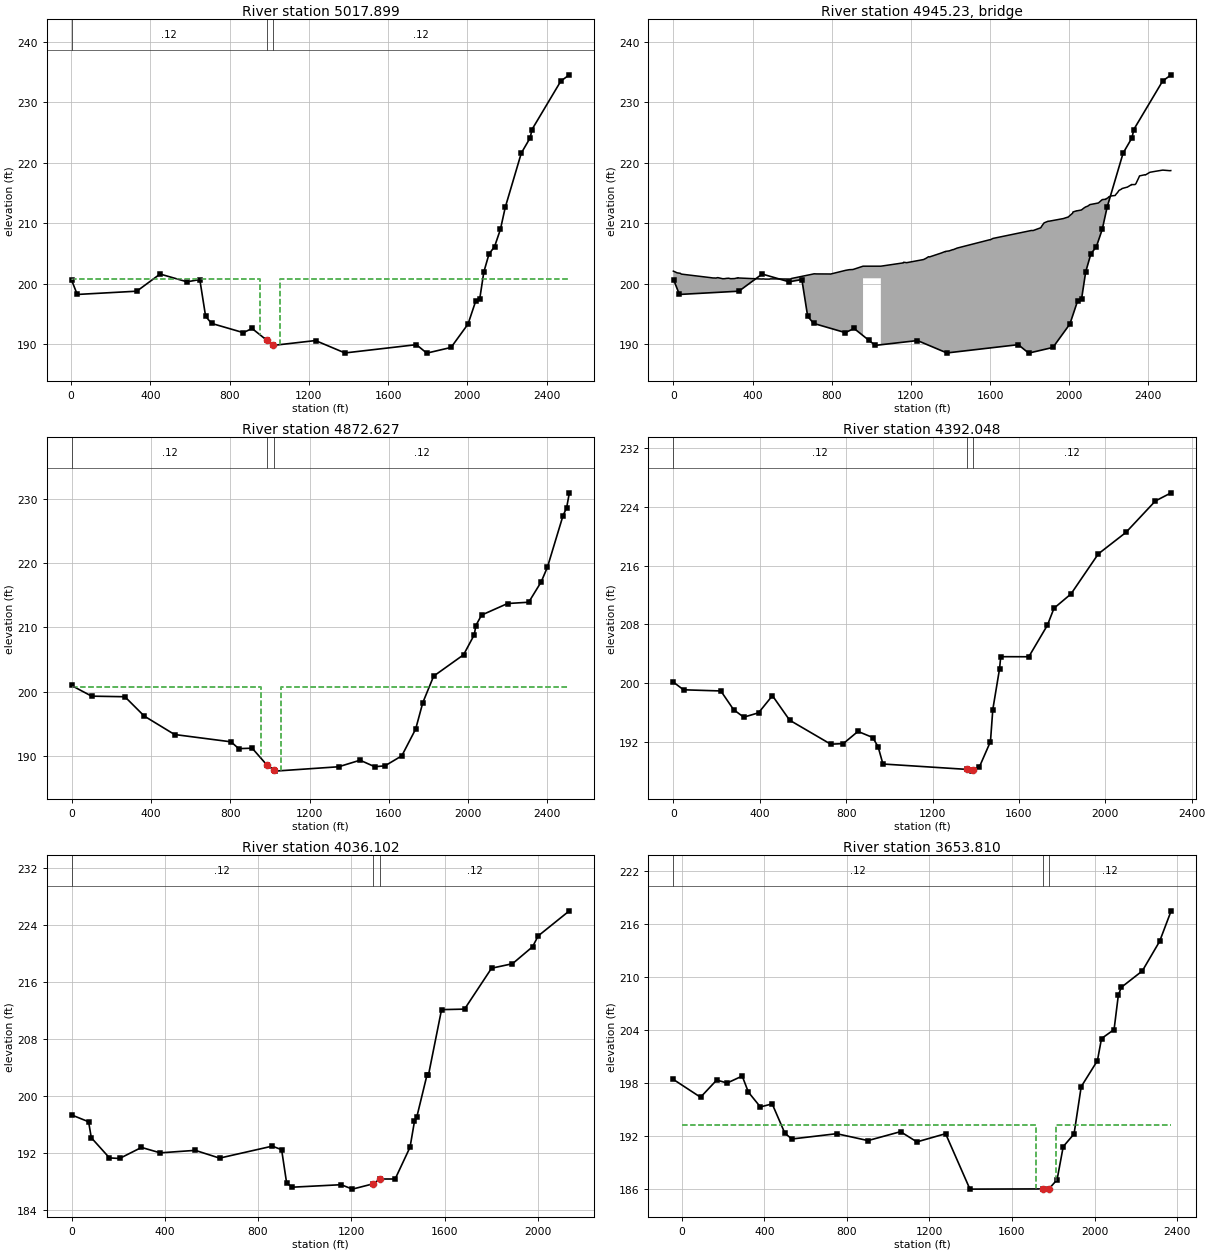
Type RM Length L Ch R = 1 ,5017.899,155.01,145.27,168.41
XS GIS Cut Line= 6
     1841857.444      383084.087     1841289.649      383335.674
     1840915.138      383515.418     1840524.971       383682.76
     1840249.348      383791.041     1839562.345      384106.268
#Sta/Elev= 30
    1.88  200.61   30.54  198.22  331.16  198.76  448.89   201.6  584.79  200.31
  649.35  200.69  678.62  194.61   708.6  193.43  869.08   191.9  913.09  192.59
  987.06  190.66 1019.73  189.79 1233.43  190.59 1382.01  188.54 1742.82  189.91
 1795.12  188.51 1917.74  189.45 2003.41  193.32 2043.25  197.22 2062.29  197.43
  2083.3  201.95 2109.67  204.95 2137.14  206.11 2167.11  209.01 2191.49  212.65
 2272.42  221.62 2317.28  224.15  2326.1  225.51 2472.27  233.55 2515.09  234.57
#Mann= 3 , 0 , 0
    1.88     .12       0  987.06    .055       0 1019.73     .12       0
#XS Ineff= 2 , 0
       0   953.4  200.76 1055.77       0  200.76
Bank Sta=987.06,1019.73
Exp/Cntr=.5,.3

Type RM Length L Ch R = 3 ,4945.23 ,,,
BEGIN DESCRIPTION:
Railroad
END DESCRIPTION:
Bridge Culvert--1,0,-1,-1, 0
Deck Dist Width WeirC Skew NumUp NumDn MinLoCord MaxHiCord MaxSubmerge Is_Ogee
60.67,24,2.6,0,120,120,200.76,,.95,0,0,0,,
       0   13.38   18.81   35.34   40.16  189.33  200.59  208.63  214.84  224.48
  249.92  260.94  266.81  279.27   289.4  309.53  325.78  326.36  327.89  449.25
  452.37  464.04  486.97  488.57  593.15  596.05  701.66  711.28  723.93  790.63
  793.42  869.99  889.02  907.57   958.4  1048.4 1162.18 1163.61 1178.77  1264.1
 1269.08 1277.45 1289.35 1294.26 1355.58 1356.86 1371.11 1374.55 1374.87 1390.68
 1391.85 1410.86 1414.54 1434.02 1597.51 1600.79 1614.36 1808.84 1817.85 1856.26
 1861.78 1871.95 1872.82 1873.35 1893.74 1895.76 1970.29 1996.69 1999.47 2017.48
 2018.76 2035.89 2036.37  2036.9 2061.77 2061.94 2062.15 2073.62 2080.63 2084.54
 2093.23 2104.86 2112.24 2142.53 2147.92 2161.55 2164.43 2166.69 2182.49 2184.16
 2186.75 2196.42  2199.7 2210.67 2211.17 2212.43 2232.25 2238.18  2243.7 2251.52
 2264.31 2266.78 2289.25 2293.65 2313.26 2315.05 2315.21 2316.26 2332.44 2336.95
  2352.1 2355.19 2383.33 2384.71 2407.59 2438.72 2472.64 2510.21 2513.05 2513.21
  202.08  201.89   201.8  201.72  201.59     201  200.95  200.95  200.93  201.01
  200.82  200.84  200.88  200.91  200.83  200.85  200.98  200.94  200.95  200.77
   200.8  200.76  200.76   200.8  200.77  200.86  201.57  201.64  201.62  201.61
  201.59  202.21  202.32  202.35   202.9   202.9  203.45  203.55  203.48     204
  204.08  204.22  204.47  204.43   205.1  205.12   205.3  205.29  205.34  205.42
  205.41  205.63  205.64   205.9  207.27  207.26  207.49  208.81   208.8  209.26
  209.55  210.02  210.05  210.07  210.35  210.33  210.78  211.06  211.17  211.68
  211.87  212.05  212.04  212.05   212.2   212.2  212.21  212.51  212.66  212.73
  212.83   213.1  213.14  213.33  213.37  213.77  213.84  213.92  213.97  213.95
  214.05  214.23  214.37   214.5  214.51  214.53   214.6  214.88  215.06  215.44
  215.66  215.75  215.95  215.98  216.37  216.41  216.43   216.4  216.41  216.55
  217.59  217.84  218.04  217.99  218.44  218.62   218.8   218.7  218.73  218.73
                                                                                
                                                                                
                                                                                
                                   200.9   200.9
                                                                                
                                                                                
                                                                                
                                                                                
                                                                                
                                                                                
                                                                                
                                                                                
       0   13.38   18.81   35.34   40.16  189.33  200.59  208.63  214.84  224.48
  249.92  260.94  266.81  279.27   289.4  309.53  325.78  326.36  327.89  449.25
  452.37  464.04  486.97  488.57  593.15  596.05  701.66  711.28  723.93  790.63
  793.42  869.99  889.02  907.57   958.4  1048.4 1162.18 1163.61 1178.77  1264.1
 1269.08 1277.45 1289.35 1294.26 1355.58 1356.86 1371.11 1374.55 1374.87 1390.68
 1391.85 1410.86 1414.54 1434.02 1597.51 1600.79 1614.36 1808.84 1817.85 1856.26
 1861.78 1871.95 1872.82 1873.35 1893.74 1895.76 1970.29 1996.69 1999.47 2017.48
 2018.76 2035.89 2036.37  2036.9 2061.77 2061.94 2062.15 2073.62 2080.63 2084.54
 2093.23 2104.86 2112.24 2142.53 2147.92 2161.55 2164.43 2166.69 2182.49 2184.16
 2186.75 2196.42  2199.7 2210.67 2211.17 2212.43 2232.25 2238.18  2243.7 2251.52
 2264.31 2266.78 2289.25 2293.65 2313.26 2315.05 2315.21 2316.26 2332.44 2336.95
  2352.1 2355.19 2383.33 2384.71 2407.59 2438.72 2472.64 2510.21 2513.05 2513.21
  202.08  201.89   201.8  201.72  201.59     201  200.95  200.95  200.93  201.01
  200.82  200.84  200.88  200.91  200.83  200.85  200.98  200.94  200.95  200.77
   200.8  200.76  200.76   200.8  200.77  200.86  201.57  201.64  201.62  201.61
  201.59  202.21  202.32  202.35   202.9   202.9  203.45  203.55  203.48     204
  204.08  204.22  204.47  204.43   205.1  205.12   205.3  205.29  205.34  205.42
  205.41  205.63  205.64   205.9  207.27  207.26  207.49  208.81   208.8  209.26
  209.55  210.02  210.05  210.07  210.35  210.33  210.78  211.06  211.17  211.68
  211.87  212.05  212.04  212.05   212.2   212.2  212.21  212.51  212.66  212.73
  212.83   213.1  213.14  213.33  213.37  213.77  213.84  213.92  213.97  213.95
  214.05  214.23  214.37   214.5  214.51  214.53   214.6  214.88  215.06  215.44
  215.66  215.75  215.95  215.98  216.37  216.41  216.43   216.4  216.41  216.55
  217.59  217.84  218.04  217.99  218.44  218.62   218.8   218.7  218.73  218.73
                                                                                
                                                                                
                                                                                
                                   200.9   200.9
                                                                                
                                                                                
                                                                                
                                                                                
                                                                                
                                                                                
                                                                                
                                                                                
BR Coef=-1 , 1 , 0 ,, 0 ,,,.8,0,1.2,0,
WSPro=,,,, 1 ,,,, 0 ,,,, 0 ,,,,-1 ,-1 ,-1 , 0 , 0 , 0 , 0 , 0
BC Design=,, 0 ,, 0 ,,,,,,

Type RM Length L Ch R = 1 ,4872.627,209.01,480.58,327.38
XS GIS Cut Line= 6
     1841816.855      382950.325      1841249.06      383201.912
     1840874.548      383381.657     1840484.381      383548.999
     1840208.759      383657.279     1839521.755      383972.506
#Sta/Elev= 30
   -1.88  200.95   99.33  199.29  267.29   199.2  365.08  196.19  518.04  193.32
  803.17  192.18  842.07  191.12  909.95  191.19  985.81  188.52 1020.99  187.79
 1023.86  187.62 1346.77   188.3 1454.62  189.32 1528.28  188.31 1580.19  188.44
 1665.28     190 1735.38  194.17 1771.36  198.28  1826.2  202.41 1977.19  205.73
 2031.23  208.85 2039.16  210.28 2068.09  211.91 2199.37  213.71 2306.07  213.91
 2368.85  217.07 2400.67  219.38 2479.37   227.4 2497.31   228.6 2511.33  230.94
#Mann= 3 , 0 , 0
   -1.88     .12       0  985.81    .055       0 1020.99     .12       0
#XS Ineff= 2 , 0
       0   953.4  200.76 1055.77       0  200.76
Bank Sta=985.81,1020.99
Exp/Cntr=.5,.3

Type RM Length L Ch R = 1 ,4392.048,356.38,355.95,352.7
XS GIS Cut Line= 4
      1841796.01      382892.371     1840362.973      383256.031
     1839879.902      383068.548     1839575.343      383115.291
#Sta/Elev= 30
       0  200.12    47.1  199.07  219.96  198.91   278.8  196.37  325.84  195.34
  394.32  195.93  458.73  198.27  538.44  194.93  728.65  191.66  787.03  191.74
  854.68   193.4  923.29  192.57  948.05   191.3  970.45  188.96  1357.5  188.23
 1380.92  187.99 1387.47  188.08  1417.4  188.59 1468.22  192.02 1479.02  196.38
 1510.32  201.94 1515.78  203.58 1645.77  203.57 1731.91  207.87 1762.36  210.18
 1841.18  212.13 1967.44  217.58 2095.13   220.5 2231.72  224.79 2304.76   225.9
#Mann= 3 , 0 , 0
       0     .12       0  1357.5    .055       0 1387.47     .12       0
Bank Sta=1357.5,1387.47
Exp/Cntr=.3,.1

Type RM Length L Ch R = 1 ,4036.102,277.88,382.29,385.9
XS GIS Cut Line= 3
     1841662.788      382557.516     1840028.117      382982.386
     1839581.643      382982.386
#Sta/Elev= 30
       0  197.37    73.1  196.41   84.71  194.17  162.63  191.34  205.99  191.26
  299.99  192.81  380.05  192.05  530.65   192.4  634.98  191.31  861.14  192.99
   901.1  192.49  922.53  187.84  945.61  187.23 1156.42  187.58 1204.72  186.96
 1291.95  187.69 1323.98  188.38 1388.05  188.38 1451.98  192.84 1470.89  196.45
 1480.98  197.08 1525.18  203.03 1530.76  202.92 1587.12  212.14 1685.75  212.21
  1801.7  217.95 1891.39  218.58 1977.61  220.96 2001.63  222.48 2135.46     226
#Mann= 3 , 0 , 0
       0     .12       0 1291.95    .055       0 1323.98     .12       0
Bank Sta=1291.95,1323.98
Exp/Cntr=.5,.3

Type RM Length L Ch R = 1 ,3653.810,243.77,282.63,250.97
XS GIS Cut Line= 5
     1842061.406      382399.215     1840539.773      382511.729
     1840088.266      382549.808     1839865.233      382587.887
     1839669.399      382653.165
#Sta/Elev= 30
  -40.54  198.37   91.26  196.35  169.58   198.3  219.88  197.96  293.13  198.75
  322.98  196.93  381.15  195.25  438.32   195.6  499.97  192.26  533.88  191.62
   750.6  192.22  902.47  191.44  1060.1  192.45 1139.28  191.29 1278.37  192.22
 1396.26  185.94 1748.67185.9646 1780.33186.0028 1818.41  187.01 1848.26  190.76
 1900.61  192.19 1935.32  197.55 2013.77  200.49 2033.73     203 2094.56  204.02
 2115.03  207.88  2128.9  208.79 2231.35  210.66 2315.16  214.01 2371.05  217.47
#Mann= 3 , 0 , 0
  -40.54     .12       0 1748.67    .055       0 1780.33     .12       0
#XS Ineff= 2 , 0
       0  1714.5  193.22  1814.5       0  193.22
Bank Sta=1748.67,1780.33
Exp/Cntr=.5,.3

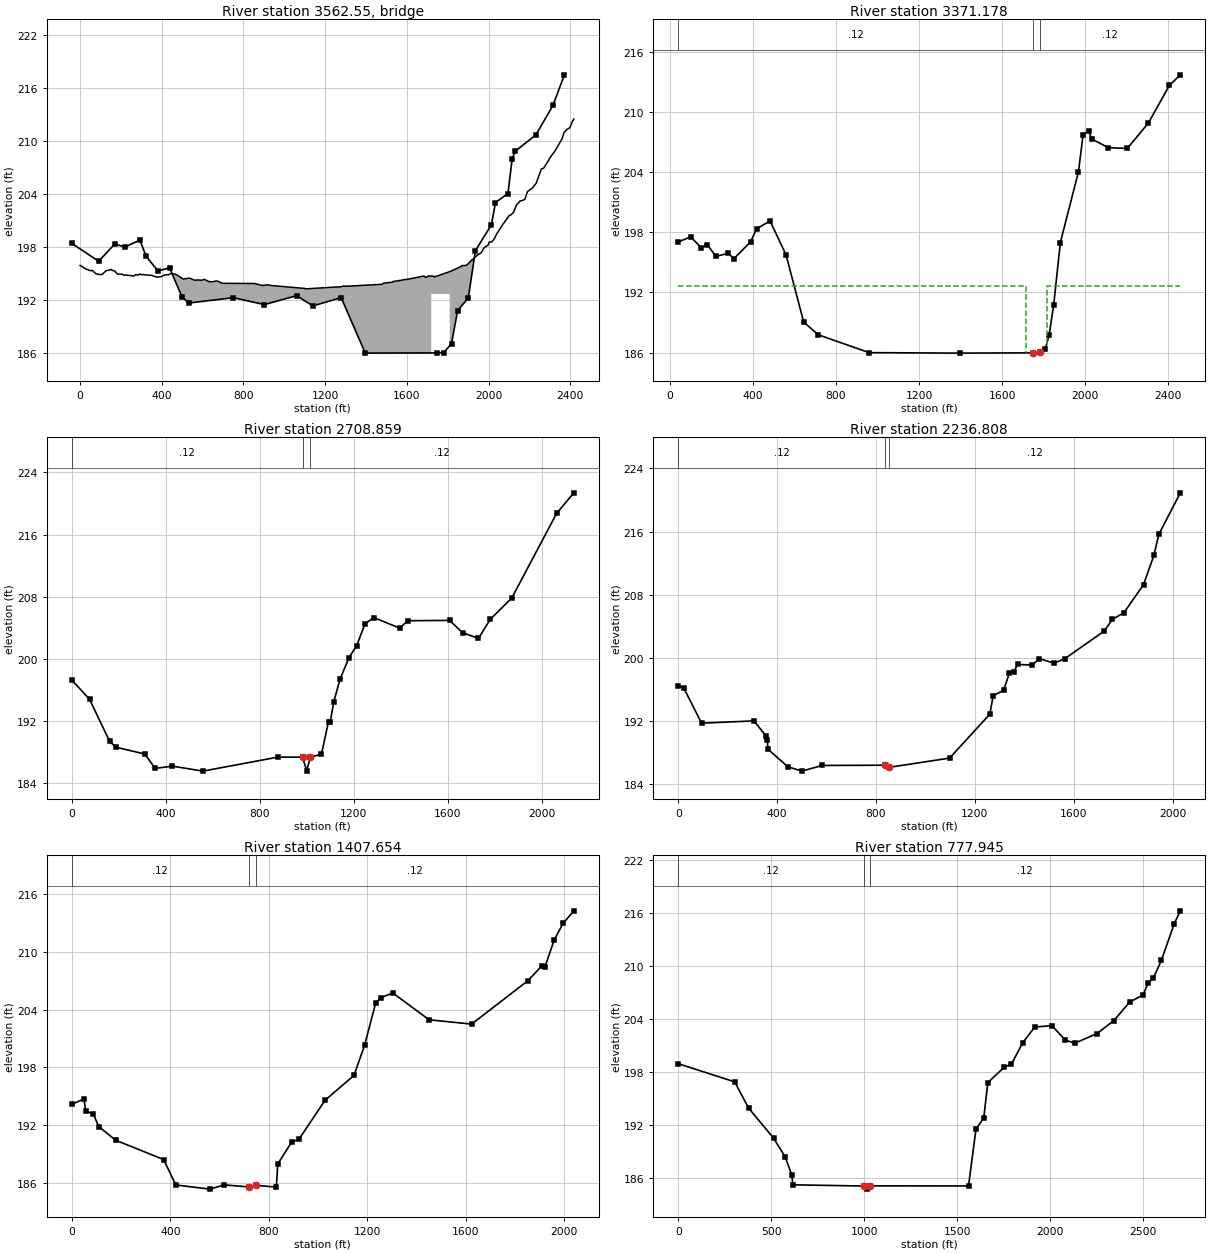
Type RM Length L Ch R = 3 ,3562.55 ,,,
BEGIN DESCRIPTION:
US 74 (NCDOT # 22&23)
END DESCRIPTION:
Bridge Culvert--1,0,-1,-1, 0
Deck Dist Width WeirC Skew NumUp NumDn MinLoCord MaxHiCord MaxSubmerge Is_Ogee
30.76,121,2.6,0,179,179,193.22,,.95,0,0,0,,
       0     .59   26.39   31.64   51.08   59.96   77.73   83.62   94.52  107.96
  111.05  127.55  143.88  150.89  158.08  169.03  182.17  185.17  188.02  205.71
  212.35  215.62  220.39  252.07  253.55  262.18   272.8   283.7   288.7   291.2
  295.16  352.59  375.52  376.24  378.12  396.19  401.44  407.65  417.45  430.52
  434.45  444.38  447.69  467.86  475.19  482.07  502.26  506.72  508.22  511.58
  529.04  536.53  548.42  561.72  569.07  588.01  592.17  595.27   607.9  629.87
  631.59  634.39  648.78  665.36  673.68  695.14  695.53  695.69  696.21  854.37
  893.97  895.01  923.05  927.35  1100.1 1103.47 1281.26 1285.61 1290.95 1315.95
 1479.07 1485.84 1530.57 1531.49 1532.73 1559.57 1560.93 1561.68  1562.3 1593.79
 1594.74 1597.66 1683.58  1686.2 1694.47 1702.05 1705.83  1719.5 1723.73 1723.98
 1729.26 1732.21 1732.54  1809.5 1866.76 1868.32 1883.87  1884.3 1884.33 1896.52
 1899.57  1915.3 1917.28 1920.27 1945.76  1961.8 1963.01  1964.6 1977.55  1984.6
 1987.14 1998.02    2002 2003.42 2013.01 2018.09 2029.72 2034.58 2042.06 2048.86
  2062.2  2070.5 2075.38 2089.86 2094.45 2099.77 2106.38 2115.97 2122.77 2126.68
 2132.96 2139.77 2147.14 2153.79 2160.18 2164.86 2177.74 2188.45 2189.83 2191.41
 2210.87 2215.84 2231.82 2232.69 2233.61 2257.74 2257.95 2258.33 2268.73  2289.1
 2289.29 2302.68 2304.27 2322.11 2323.88 2326.88 2343.25 2343.99 2355.55 2360.15
 2369.11 2369.43 2383.68  2385.9 2397.36 2407.81 2408.87  2410.5 2417.29
  195.88  195.89   195.5  195.45  195.28  195.31  194.93   194.9  194.85  194.84
  194.92  195.28  195.35  195.43  195.31  195.26  194.93  194.89  194.88  194.89
   194.8  194.76  194.79  194.72  194.71  194.67  194.83  194.78  194.84   194.9
  194.86  194.74  194.55  194.56  194.56   194.6  194.65  194.72  194.82  194.81
  194.83  194.96  194.96  194.88  194.78  194.67  194.38  194.32  194.33  194.36
  194.42  194.44  194.32  194.19  194.23  194.22  194.19  194.19  194.31  194.05
  194.04  194.03  194.03  194.11   194.1  193.86  193.86  193.86  193.85  193.83
  193.59  193.62  193.69  193.62  193.27  193.22  193.47  193.54  193.53  193.53
  193.74  193.87  193.98  194.01  194.06  194.15  194.18  194.18  194.15   194.3
  194.29  194.28  194.68  194.62  194.53  194.63  194.69  194.68  194.67  194.66
  194.65  194.65  194.56  195.17  195.77  195.86  195.86  195.86  195.86  195.96
  196.07  196.44  196.48  196.52  197.06  197.27   197.3  197.35  197.86  197.97
  198.01  198.19  198.48  198.52  198.52  198.61  198.96  199.21  199.54  199.77
  200.26  200.57  200.69  201.18  201.26  201.54  201.55  201.75  201.91  202.16
  202.53   202.8     203  203.17   203.2  203.22  203.37  204.15  204.21  204.26
  204.59  204.68  205.15  205.18  205.23  206.79   206.8  206.81  206.88  207.62
  207.62  208.14  208.21  208.74  208.79  208.93  209.57  209.58  210.05  210.24
  210.92  210.94  211.27  211.33  211.47  212.06  212.12  212.19  212.46
                                                                                
                                                                                
                                                                                
                                                                                
                                                                                
                                                                                
                                                                                
                                                                                
                                                                                
                                                          192.65  192.65  192.65
  192.65  192.65  192.65  192.65
                                                                                
                                                                                
                                                                                
                                                                                
                                                                                
                                                                                
                                                                        
       0     .59   26.39   31.64   51.08   59.96   77.73   83.62   94.52  107.96
  111.05  127.55  143.88  150.89  158.08  169.03  182.17  185.17  188.02  205.71
  212.35  215.62  220.39  252.07  253.55  262.18   272.8   283.7   288.7   291.2
  295.16  352.59  375.52  376.24  378.12  396.19  401.44  407.65  417.45  430.52
  434.45  444.38  447.69  467.86  475.19  482.07  502.26  506.72  508.22  511.58
  529.04  536.53  548.42  561.72  569.07  588.01  592.17  595.27   607.9  629.87
  631.59  634.39  648.78  665.36  673.68  695.14  695.53  695.69  696.21  854.37
  893.97  895.01  923.05  927.35  1100.1 1103.47 1281.26 1285.61 1290.95 1315.95
 1479.07 1485.84 1530.57 1531.49 1532.73 1559.57 1560.93 1561.68  1562.3 1593.79
 1594.74 1597.66 1683.58  1686.2 1694.47 1702.05 1705.83  1719.5 1723.73 1723.98
 1729.26 1732.21 1732.54  1809.5 1866.76 1868.32 1883.87  1884.3 1884.33 1896.52
 1899.57  1915.3 1917.28 1920.27 1945.76  1961.8 1963.01  1964.6 1977.55  1984.6
 1987.14 1998.02    2002 2003.42 2013.01 2018.09 2029.72 2034.58 2042.06 2048.86
  2062.2  2070.5 2075.38 2089.86 2094.45 2099.77 2106.38 2115.97 2122.77 2126.68
 2132.96 2139.77 2147.14 2153.79 2160.18 2164.86 2177.74 2188.45 2189.83 2191.41
 2210.87 2215.84 2231.82 2232.69 2233.61 2257.74 2257.95 2258.33 2268.73  2289.1
 2289.29 2302.68 2304.27 2322.11 2323.88 2326.88 2343.25 2343.99 2355.55 2360.15
 2369.11 2369.43 2383.68  2385.9 2397.36 2407.81 2408.87  2410.5 2417.29
  195.88  195.89   195.5  195.45  195.28  195.31  194.93   194.9  194.85  194.84
  194.92  195.28  195.35  195.43  195.31  195.26  194.93  194.89  194.88  194.89
   194.8  194.76  194.79  194.72  194.71  194.67  194.83  194.78  194.84   194.9
  194.86  194.74  194.55  194.56  194.56   194.6  194.65  194.72  194.82  194.81
  194.83  194.96  194.96  194.88  194.78  194.67  194.38  194.32  194.33  194.36
  194.42  194.44  194.32  194.19  194.23  194.22  194.19  194.19  194.31  194.05
  194.04  194.03  194.03  194.11   194.1  193.86  193.86  193.86  193.85  193.83
  193.59  193.62  193.69  193.62  193.27  193.22  193.47  193.54  193.53  193.53
  193.74  193.87  193.98  194.01  194.06  194.15  194.18  194.18  194.15   194.3
  194.29  194.28  194.68  194.62  194.53  194.63  194.69  194.68  194.67  194.66
  194.65  194.65  194.56  195.17  195.77  195.86  195.86  195.86  195.86  195.96
  196.07  196.44  196.48  196.52  197.06  197.27   197.3  197.35  197.86  197.97
  198.01  198.19  198.48  198.52  198.52  198.61  198.96  199.21  199.54  199.77
  200.26  200.57  200.69  201.18  201.26  201.54  201.55  201.75  201.91  202.16
  202.53   202.8     203  203.17   203.2  203.22  203.37  204.15  204.21  204.26
  204.59  204.68  205.15  205.18  205.23  206.79   206.8  206.81  206.88  207.62
  207.62  208.14  208.21  208.74  208.79  208.93  209.57  209.58  210.05  210.24
  210.92  210.94  211.27  211.33  211.47  212.06  212.12  212.19  212.46
                                                                                
                                                                                
                                                                                
                                                                                
                                                                                
                                                                                
                                                                                
                                                                                
                                                                                
                                                          192.65  192.65  192.65
  192.65  192.65  192.65  192.65
                                                                                
                                                                                
                                                                                
                                                                                
                                                                                
                                                                                
                                                                        
BR Coef=-1 , 1 , 0 ,, 0 ,,,.8,0,1.2,0,
WSPro=,,,, 1 ,,,, 0 ,,,, 0 ,,,,-1 ,-1 ,-1 , 0 , 0 , 0 , 0 , 0
BC Design=,, 0 ,, 0 ,,,,,,

Type RM Length L Ch R = 1 ,3371.178,296.18,662.32,619.58
XS GIS Cut Line= 5
     1842061.406      382157.803     1840534.081      382270.738
     1840082.574      382308.817      1839859.54      382346.895
     1839663.706      382412.174
#Sta/Elev= 30
   40.54  197.03  100.78  197.54  150.37  196.46  179.66  196.77  222.32  195.59
  281.95   195.9  308.29  195.35  388.53  197.04  418.07  198.35  482.72  199.12
   559.8  195.73  644.35  189.05  714.67  187.77   959.5  185.99 1396.26  185.94
 1746.27  185.97  1782.7  186.01 1808.46  186.38 1825.87  187.72 1848.26  190.76
 1880.27  196.97 1967.43  204.02 1989.75  207.73 2016.61  208.14  2030.6  207.32
 2111.47  206.43  2202.6  206.36 2304.02  208.89 2405.34  212.65 2457.83   213.7
#Mann= 3 , 0 , 0
   40.54     .12       0 1746.27    .055       0  1782.7     .12       0
#XS Ineff= 2 , 0
       0  1714.5  192.65  1814.5       0  192.65
Bank Sta=1746.27,1782.7
Exp/Cntr=.5,.3

Type RM Length L Ch R = 1 ,2708.859,378.78,472.05,394.36
XS GIS Cut Line= 4
     1841627.489      382134.232     1841393.576      382155.991
     1840906.499      381946.038     1839646.574      381402.664
#Sta/Elev= 30
       0  197.28   76.11  194.77  160.89  189.38  187.97  188.62  311.49  187.74
   354.8  185.89  428.78  186.18  558.14  185.54   876.6  187.34  982.34  187.34
 1000.17  185.59 1015.94  187.36 1062.74   187.7 1092.96  191.91 1100.45  191.91
 1115.62   194.5 1142.31   197.4 1180.23  200.16 1213.24  201.71 1248.24  204.52
 1286.63  205.31 1395.73  203.96 1430.97  204.91 1608.12  204.95 1663.88  203.37
 1731.49  202.63 1781.98   205.1 1873.06  207.83  2064.2  218.74 2137.43  221.38
#Mann= 3 , 0 , 0
       0     .12       0  982.34    .055       0 1015.94     .12       0
Bank Sta=982.34,1015.94
Exp/Cntr=.3,.1

Type RM Length L Ch R = 1 ,2236.808,588.49,829.15,587.99
XS GIS Cut Line= 3
     1841671.007      381796.961     1841371.816      381748.003
     1839808.116      381013.416
#Sta/Elev= 30
       0  196.45   21.59  196.22    94.3  191.71  306.51     192  355.17  190.07
  360.32  189.63   362.9  188.41  442.99  186.19  500.26  185.63  582.05  186.35
   836.7  186.38  850.91   186.1 1097.46  187.28 1260.75  192.86 1273.61  195.19
 1316.02  195.87 1339.14  198.03 1357.78  198.23 1372.27  199.15 1431.59  199.08
 1461.02  199.89 1519.72  199.32 1562.98  199.87 1723.73   203.4 1755.92  204.86
  1803.2  205.73 1881.98  209.27  1923.8  212.97 1943.86  215.64 2030.82  220.91
#Mann= 3 , 0 , 0
       0     .12       0   836.7    .055       0  850.91     .12       0
Bank Sta=836.7,850.91
Exp/Cntr=.3,.1

Type RM Length L Ch R = 1 ,1407.654,442.54,629.71,412.68
XS GIS Cut Line= 4
     1841987.557      381468.773     1841583.455      381235.218
     1841037.753      380985.104     1840153.292      380583.877
#Sta/Elev= 30
       0  194.16   49.62  194.72   56.68  193.48   87.86  193.14  109.55  191.85
  178.54  190.43  373.02  188.43  422.43  185.79  561.19  185.36  618.42   185.8
  717.46  185.59  748.03  185.75   830.5  185.57   836.4  187.98  892.45  190.24
  921.88  190.52 1028.42  194.59 1145.85  197.17 1189.39  200.35 1233.86   204.7
 1255.86  205.25 1303.38  205.72 1450.61  202.94 1623.19  202.49 1851.34  206.99
 1907.88  208.53  1920.3  208.38 1958.46  211.23 1994.46  212.95 2038.24  214.25
#Mann= 3 , 0 , 0
       0     .12       0  717.46    .055       0  748.03     .12       0
Bank Sta=717.46,748.03
Exp/Cntr=.3,.1

Type RM Length L Ch R = 1 ,777.945 ,329.17,499.82,329.92
XS GIS Cut Line= 4
     1842699.137      381318.255     1841888.601      380959.226
     1841540.451      380779.711     1840245.769      380192.208
#Sta/Elev= 30
       0  198.95  303.71  196.89  378.33  193.92  512.85   190.5   575.1  188.39
  610.67  186.33   616.6  185.22   997.8  185.08 1014.73  184.73 1033.07   185.1
 1560.98  185.09 1601.07  191.51 1643.07  192.84 1664.96  196.81  1753.9  198.57
 1791.47  198.88 1852.11  201.32 1917.57  203.11 2009.52  203.26 2081.74  201.63
 2131.91  201.27 2252.47  202.37 2342.51  203.84 2427.89  205.94 2500.16  206.75
 2525.85  208.08 2554.75  208.64 2597.98  210.65 2667.42  214.83 2699.95  216.28
#Mann= 3 , 0 , 0
       0     .12       0   997.8    .055       0 1033.07     .12       0
Bank Sta=997.8,1033.07
Exp/Cntr=.3,.1

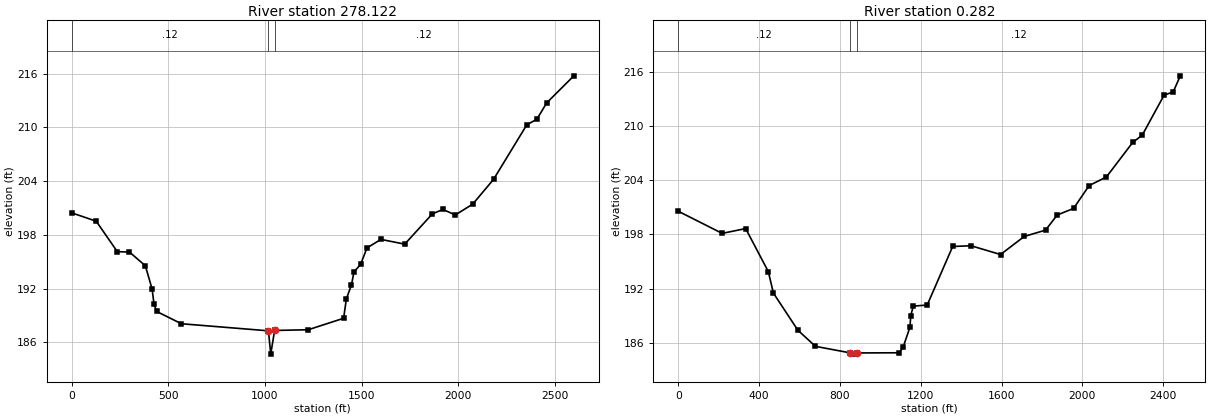
Type RM Length L Ch R = 1 ,278.122 ,238.2,277.84,233.66
XS GIS Cut Line= 5
     1842743.396      381007.045     1842038.207      380666.778
     1841617.561       380462.14     1841526.611      380450.771
      1840373.36      379952.567
#Sta/Elev= 30
       0  200.46  126.56  199.53  235.81  196.13  298.52  196.09  380.86  194.56
  415.95  191.95  425.64  190.27  439.31  189.46  567.41  188.09 1017.91   187.3
 1029.85   184.7 1049.87  187.34  1223.9  187.42 1407.02   188.7 1421.26  190.86
 1447.51  192.42 1460.62  193.87 1495.04  194.71 1527.89  196.55 1600.21   197.5
 1723.28  196.97 1866.49  200.35 1921.04  200.84 1985.26  200.23 2075.04  201.43
 2183.17   204.2 2355.34  210.29 2407.47  210.91  2458.1  212.73 2598.69  215.75
#Mann= 3 , 0 , 0
       0     .12       0 1017.91    .055       0 1049.87     .12       0
Bank Sta=1017.91,1049.87
Exp/Cntr=.3,.1

Type RM Length L Ch R = 1 ,0.282   ,.58,.28,.58
XS GIS Cut Line= 3
     1842825.153      380724.961     1841292.869      380124.066
     1840523.934      379789.861
#Sta/Elev= 30
       0  200.55  217.33   198.1  333.67  198.63  445.73  193.87  470.98  191.49
  592.04  187.38   679.1   185.6  848.36  184.89  866.78  184.74  882.43  184.87
 1093.14  184.89  1112.7   185.5 1146.61  187.73 1150.59  189.01 1163.02  190.05
 1231.85  190.17    1358  196.65 1449.08  196.73 1594.82  195.76 1712.11  197.76
 1817.55  198.46  1875.1  200.13 1956.21  200.86 2033.17  203.39 2118.66  204.34
 2249.05  208.17 2295.81  208.96 2403.68  213.38 2449.27  213.76 2484.32  215.53
#Mann= 3 , 0 , 0
       0     .12       0  848.36    .055       0  882.43     .12       0
Bank Sta=848.36,882.43
Exp/Cntr=.3,.1

Chan Stop Cuts=-1

--- gum_limited.g01 (geometry) ---

Geom Title=Base Geometry
Version=September 1998 Version 2.2

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
River Reach=Gum Swamp       ,Reach 01

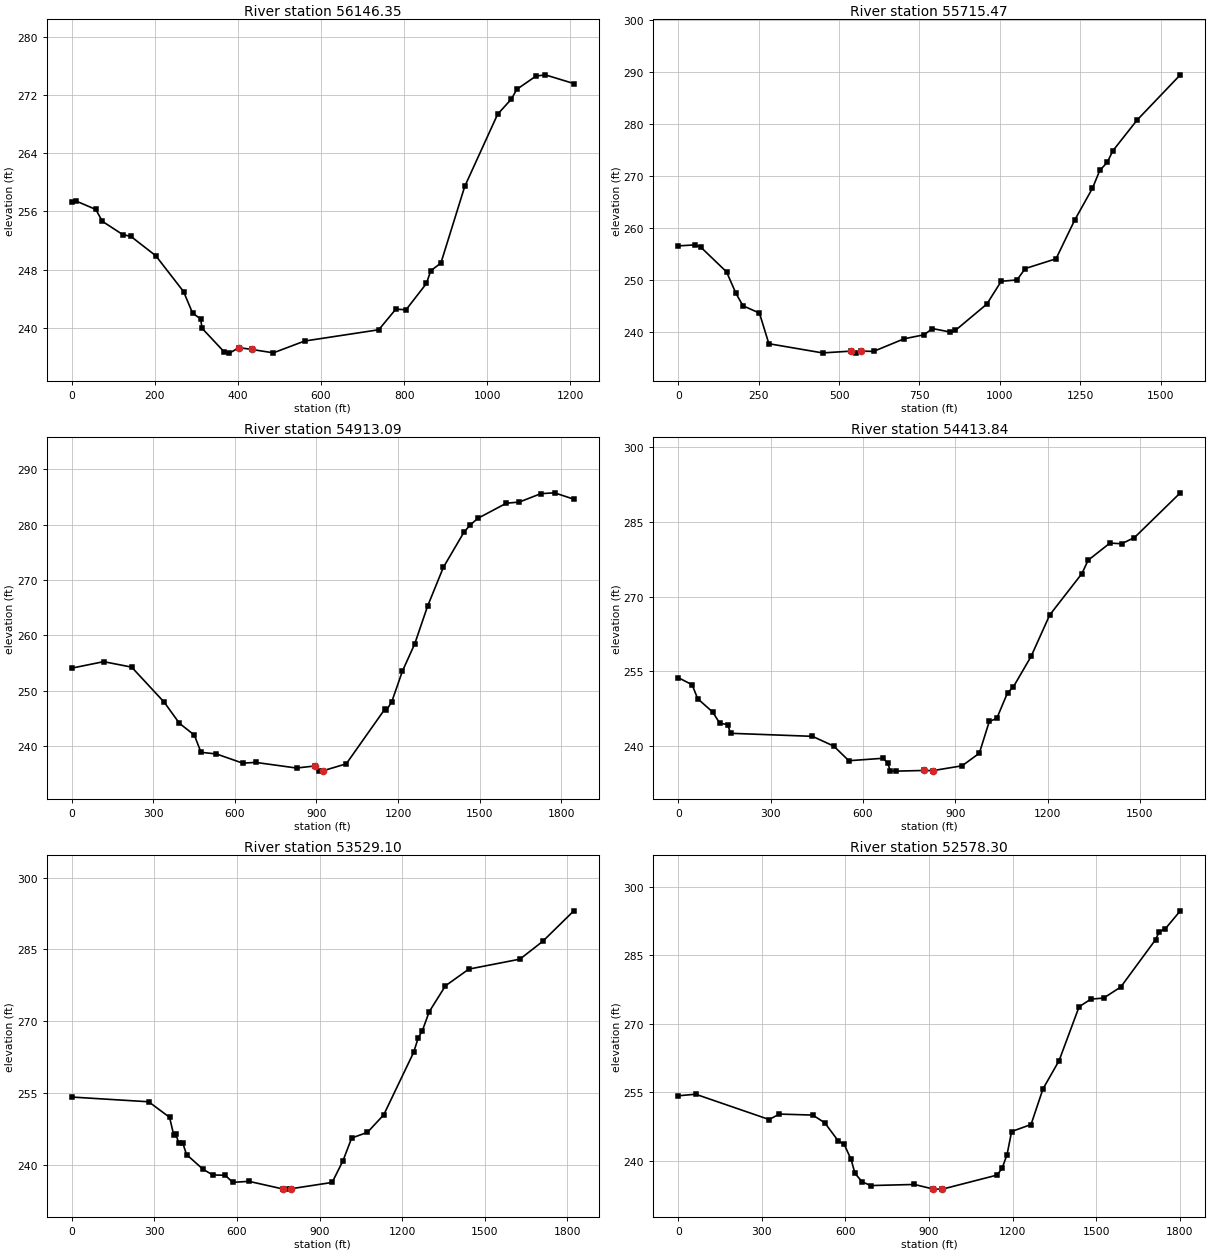
Type RM Length L Ch R = 1 ,56146.35,381.51,430.88,359.51
XS GIS Cut Line= 2
     1832251.916      417047.607     1831124.716      416612.098
#Sta/Elev= 30
       0  257.23   11.06  257.39   57.93  256.25   73.39  254.63  122.84  252.79
  142.26  252.55  202.24  249.89  269.11  244.96  290.91  241.99  310.17  241.22
  313.49  239.93  366.81  236.68  379.56  236.51   402.4  237.27  432.61  237.02
  485.24  236.55  560.33  238.17  738.83  239.72  779.88  242.55  804.62  242.47
  853.73  246.09  863.79  247.81  888.45  248.89  945.84  259.42 1025.02  269.34
 1057.95  271.41 1071.22  272.76 1117.07  274.57 1139.43  274.75 1208.41  273.55
#Mann= 0 , 0 , 0
Bank Sta=402.4,432.61
Exp/Cntr=.3,.1

Type RM Length L Ch R = 1 ,55715.47,602.68,802.38,587.97
XS GIS Cut Line= 2
     1832568.731      416844.907      1831147.04      416200.515
#Sta/Elev= 30
       0  256.61   51.15   256.8   70.11  256.37  150.23  251.61  179.43  247.48
  201.04   245.1  252.41  243.68  281.79  237.79  448.83  236.02   538.2  236.37
  552.51  235.98  568.17  236.37   607.1  236.31  702.24  238.74   764.6  239.51
  789.93  240.71   843.8  240.06  861.91  240.37  959.48  245.42 1004.04   249.8
 1053.17  250.06 1078.79  252.25 1174.56  254.13 1232.49  261.57  1287.8   267.7
 1310.48  271.13 1333.87  272.68 1350.85  274.88 1426.44  280.81 1560.91  289.52
#Mann= 0 , 0 , 0
Bank Sta=538.2,568.17
Exp/Cntr=.3,.1

Type RM Length L Ch R = 1 ,54913.09,403.79,499.25,384.19
XS GIS Cut Line= 2
     1833229.233      416514.656      1831545.62      415756.051
#Sta/Elev= 30
       0  254.06  117.33  255.23  220.28  254.24  340.27  247.88  395.88  244.08
  450.86  241.95   475.2  238.83  531.82  238.54  628.86  236.87  676.39  237.01
  826.62  235.99  893.64  236.36  909.01  235.43  925.16  235.51  1009.6  236.75
  1151.6  246.65 1157.48  246.48 1176.73  247.95 1215.82  253.48 1261.63  258.48
 1308.54  265.25  1366.8   272.3 1442.43  278.64  1464.3   279.9 1493.07  281.14
 1598.18  283.89 1645.94   284.1 1725.28  285.62 1775.51  285.77 1846.63  284.62
#Mann= 0 , 0 , 0
Bank Sta=893.64,925.16
Exp/Cntr=.3,.1

Type RM Length L Ch R = 1 ,54413.84,649.56,884.73,623.49
XS GIS Cut Line= 2
     1833266.829      416110.024     1831778.827      415442.434
#Sta/Elev= 30
       0  253.74   45.15  252.31   63.09  249.52  112.56  246.79  134.72  244.59
  160.17  244.33  170.27  242.57  435.97  241.96  505.33     240  554.15  237.07
  665.77  237.56  680.68  236.54  688.72  235.05  707.33  234.98  797.51  235.11
  826.86  235.08  922.11  236.05  978.04  238.57 1010.36  244.95 1034.78  245.56
 1069.71  250.71 1088.29  251.85  1146.2     258 1206.66  266.31 1311.19  274.61
 1331.38  277.29 1402.43  280.74 1439.93   280.6 1481.77  281.83  1630.9  290.82
#Mann= 0 , 0 , 0
Bank Sta=797.51,826.86
Exp/Cntr=.3,.1

Type RM Length L Ch R = 1 ,53529.10,701.43,950.8,678.49
XS GIS Cut Line= 3
     1833664.198      415648.754     1832367.358      415056.719
     1832194.178      414698.276
#Sta/Elev= 30
       0  254.12  279.39  253.13  355.22  249.88  369.91  246.28  378.23  246.37
  387.84  244.59  403.72  244.41  416.79   242.1  476.16  239.04  511.98  237.82
  557.24  237.76  584.87  236.27  643.49  236.49  767.77  234.88  788.59  234.86
  795.12  234.93  945.76  236.26   985.1  240.79 1016.64  245.55 1073.78  246.73
 1133.13   250.4 1241.68  263.45 1258.57  266.53 1272.91  267.91 1298.14  271.94
 1357.35  277.39 1442.37  280.88 1627.63  282.96 1710.11  286.66 1823.67  293.07
#Mann= 0 , 0 , 0
Bank Sta=767.77,795.12
Exp/Cntr=.3,.1

Type RM Length L Ch R = 1 ,52578.30,757.77,773.92,737.85
XS GIS Cut Line= 2
     1834063.065      415008.227     1832365.938      414404.983
#Sta/Elev= 30
       0  254.28   62.47  254.62  326.03  249.09  363.03  250.28  482.56  250.06
  525.55  248.38  573.28  244.47  595.46  243.64  620.09  240.36  634.03  237.31
  659.58  235.48  690.31  234.65  847.15  234.89  915.21  233.88  947.68  233.87
 1143.66  236.94 1161.92  238.44 1179.52  241.41 1195.95  246.46 1265.68     248
 1308.59   255.8 1366.27  261.97 1438.04  273.74 1480.55  275.42 1525.86  275.64
 1587.61  278.07 1712.32  288.41 1725.73  290.19 1747.09  290.78 1801.15  294.72
#Mann= 0 , 0 , 0
Bank Sta=915.21,947.68
Exp/Cntr=.5,.3