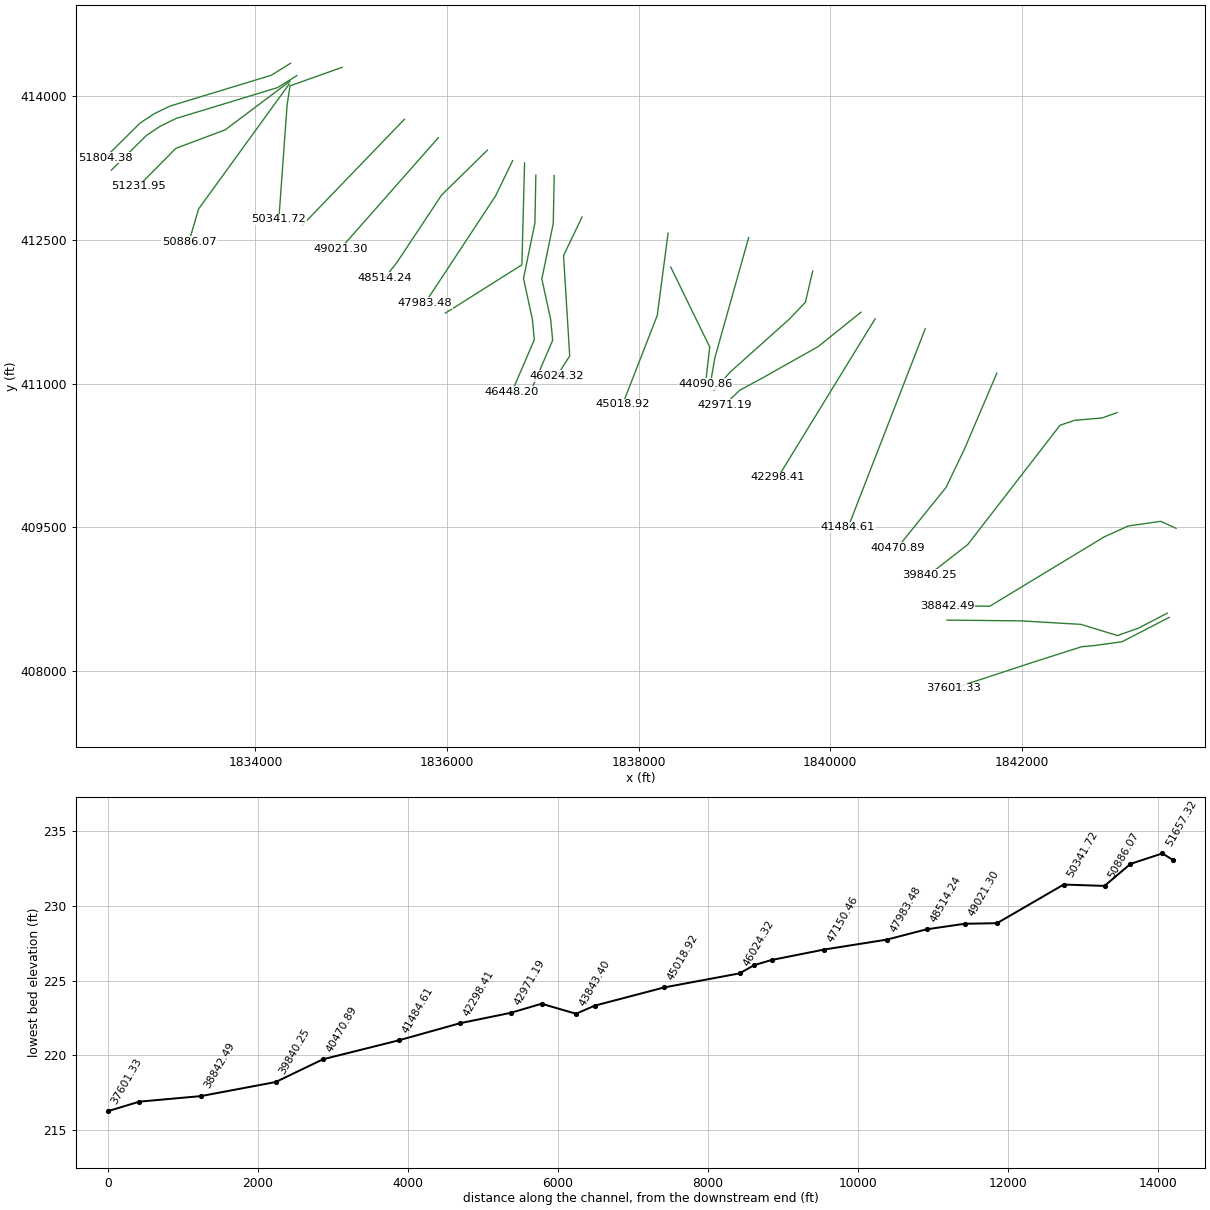
HEC-RAS study gum_limited.prj: Gum Swamp

--- gum_limited.g01 (geometry) --- (continued)

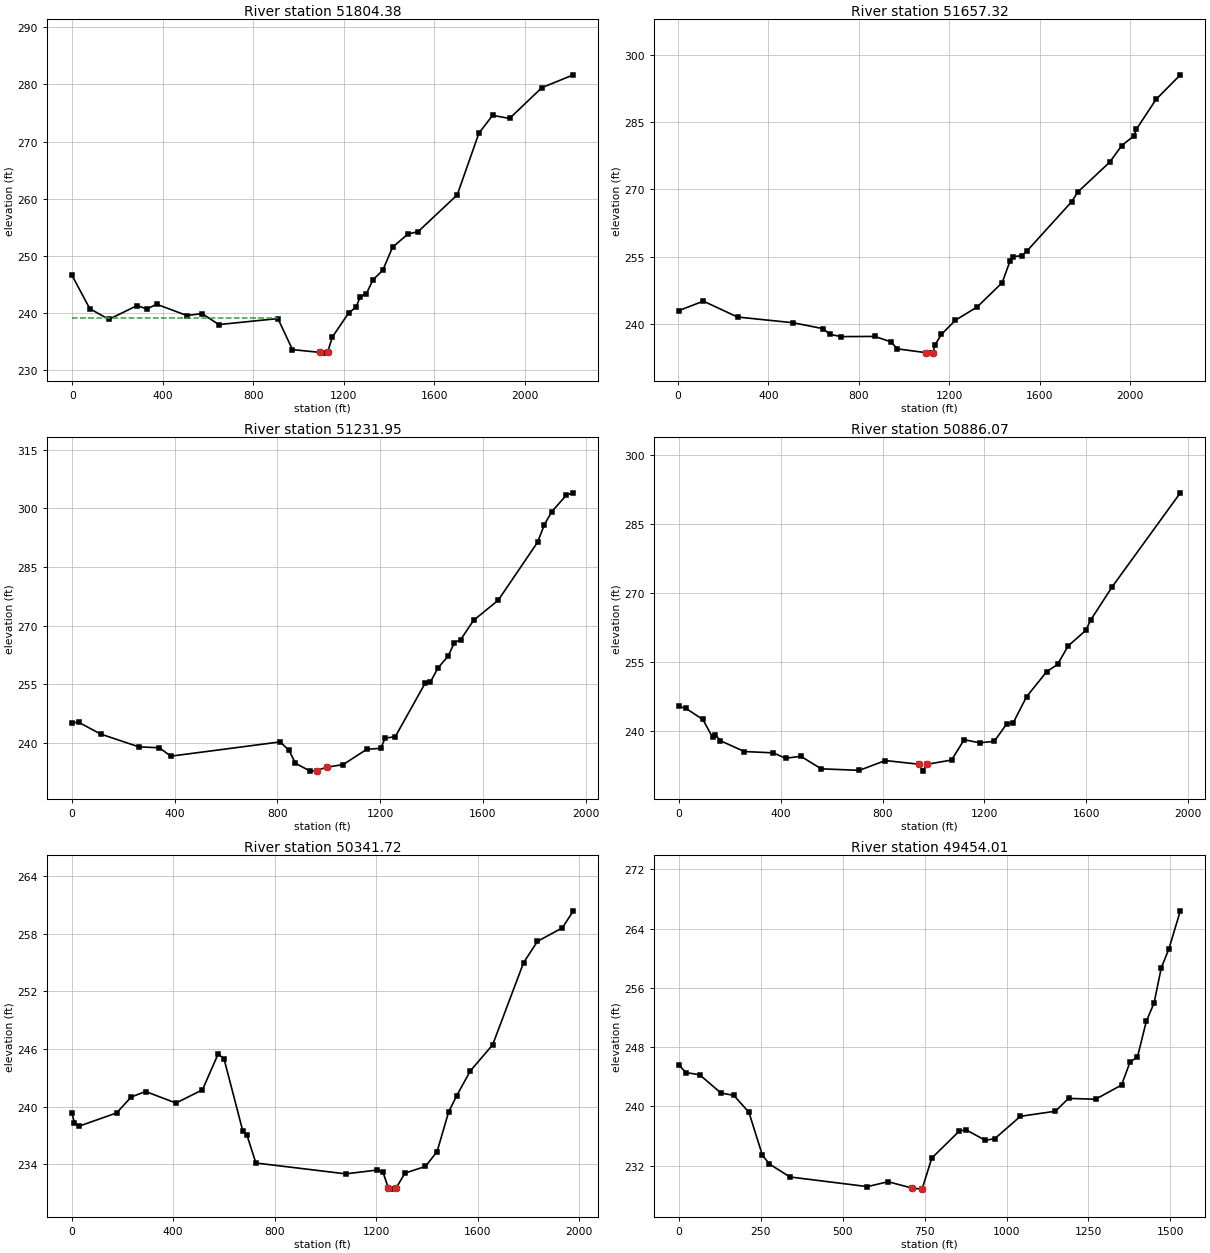
Type RM Length L Ch R = 1 ,51804.38,144.8,147.06,148.22
XS GIS Cut Line= 6
     1834365.974      414345.483     1834164.601      414220.632
     1833105.381      413898.436     1832940.256      413817.887
     1832795.268      413721.228     1832428.769      413358.757
#Sta/Elev= 30
   -3.31  246.71   76.41   240.8  160.85  238.93  286.03  241.35   328.2  240.74
  371.99  241.57  506.16   239.6  572.53  239.95  646.99  238.02  908.23  239.07
  972.61  233.64 1096.34  233.15 1112.28  233.03 1127.88   233.2 1148.69  235.83
 1220.92  240.05 1254.57  241.12 1272.13  242.92 1298.92  243.39 1328.67  245.86
 1371.96  247.52 1414.96  251.53 1482.28  253.84 1528.11  254.27 1700.93  260.69
 1796.82  271.48  1857.5   274.6 1932.27  274.05 2074.94  279.43  2214.3  281.68
#Mann= 3 , 0 , 0
   -3.31               0 1096.34               0 1127.88               0
#XS Ineff= 2 , 0
          904.65  239.11
Bank Sta=1096.34,1127.88
Exp/Cntr=.5,.3

Type RM Length L Ch R = 1 ,51657.32,276.96,425.37,285.74
XS GIS Cut Line= 6
     1834432.738      414217.089     1834231.366      414092.238
     1833172.146      413770.042      1833007.02      413689.493
     1832862.032      413592.834     1832495.534      413230.364
#Sta/Elev= 30
    3.31  242.96  112.28  245.07  263.15  241.53  508.31  240.26  640.14  238.95
  672.64  237.65  722.02  237.17  869.84  237.21  942.26  235.99  968.93  234.45
 1096.37  233.59 1112.93  233.49 1127.79   233.6 1135.94  235.31 1164.87  237.66
 1226.24  240.81 1322.77  243.78 1432.95  249.16 1468.58  254.09 1481.39  255.01
 1520.07  255.17 1544.05  256.31 1741.16  267.26 1767.21  269.36 1908.81  276.03
 1961.99  279.73 2015.64  281.88 2025.99  283.32 2113.59  290.01 2220.91  295.48
#Mann= 3 , 0 , 0
    3.31               0 1096.37               0 1127.79               0
Bank Sta=1096.37,1127.79
Exp/Cntr=.5,.3

Type RM Length L Ch R = 1 ,51231.95,328.89,345.87,386.51
XS GIS Cut Line= 4
     1834360.947      414158.597     1833684.335      413651.138
     1833168.821      413457.821     1832778.158       413063.13
#Sta/Elev= 30
       0  245.19   27.12  245.28  112.37  242.28  261.46     239  340.26  238.77
  385.67  236.62  811.02  240.27  845.76  238.07  870.41   234.8   927.7  232.79
  952.41  232.93  991.45  233.79  1056.2  234.47 1147.47  238.36 1202.36  238.63
 1219.44  241.21 1259.04  241.63  1374.9  255.27 1395.59  255.61 1425.51  259.24
 1464.54  262.23 1489.11   265.7 1513.16  266.42 1563.45  271.38 1659.45  276.53
 1812.34  291.35 1838.81  295.83 1867.26  299.14 1924.88  303.45 1951.67  304.01
#Mann= 0 , 0 , 0
Bank Sta=952.41,991.45
Exp/Cntr=.3,.1

Type RM Length L Ch R = 1 ,50886.07,408.69,544.35,585.92
XS GIS Cut Line= 3
     1834352.892      414130.405     1833406.441      412825.511
     1833305.754      412483.177
#Sta/Elev= 30
       0  245.39   28.23  244.95    94.7  242.54  132.51  238.69  144.19  239.18
  163.43  237.93  257.51  235.58  370.98  235.29  419.28  234.12  479.11  234.54
  559.46  231.82  708.81  231.49     811  233.62  943.07  232.82  958.07  231.32
  972.92  232.79 1070.76  233.73 1120.35  238.15 1180.77  237.48 1238.23  237.78
 1287.61   241.6 1312.86  241.82 1365.58  247.52 1444.37  252.94 1486.95  254.51
 1528.34  258.52  1598.7  261.95 1616.64  264.14  1701.4  271.38 1968.83   291.8
#Mann= 0 , 0 , 0
Bank Sta=943.07,972.92
Exp/Cntr=.3,.1

Type RM Length L Ch R = 1 ,50341.72,960.52,887.71,761.47
XS GIS Cut Line= 4
     1834904.653      414303.585     1834360.947      414110.268
     1834330.256      413910.691     1834244.084      412715.771
#Sta/Elev= 30
       0  239.35   10.82  238.32   30.54  237.98  176.68  239.34  234.91  241.01
   291.3  241.57  410.93  240.37   515.2  241.75  577.05  245.48  600.24  244.97
  673.94  237.48  690.61  237.03  725.81  234.13 1079.94     233 1201.28  233.39
 1226.86  233.15 1247.48  231.56 1259.43  231.41 1279.31  231.55 1313.17  233.08
 1394.05  233.77 1439.97  235.32 1485.79  239.47 1517.33  241.14  1570.8  243.71
 1658.95  246.43 1780.98  254.99 1835.55   257.2 1933.84  258.61    1977  260.38
#Mann= 0 , 0 , 0
Bank Sta=1247.48,1279.31
Exp/Cntr=.3,.1

Type RM Length L Ch R = 1 ,49454.01,417.49,432.71,448.53
XS GIS Cut Line= 2
     1835555.135      413761.394     1834493.425      412659.469
#Sta/Elev= 30
       0   245.6   22.21  244.56   63.79  244.27  128.53  241.81  167.97  241.49
  214.09   239.2     255  233.43  276.16  232.23  339.36  230.47  575.55  229.17
  638.62  229.83  711.54  228.97  742.25  228.83  771.96  233.02  855.47  236.65
  875.84  236.85  935.34  235.42     964  235.64 1042.28  238.66  1149.2  239.35
 1189.09  241.08 1271.44  240.96 1350.72  242.88 1376.89  245.99 1399.45  246.68
 1426.53  251.51 1450.03  253.95 1472.04  258.71 1495.21  261.25 1530.19   266.4
#Mann= 0 , 0 , 0
Bank Sta=711.54,742.25
Exp/Cntr=.3,.1

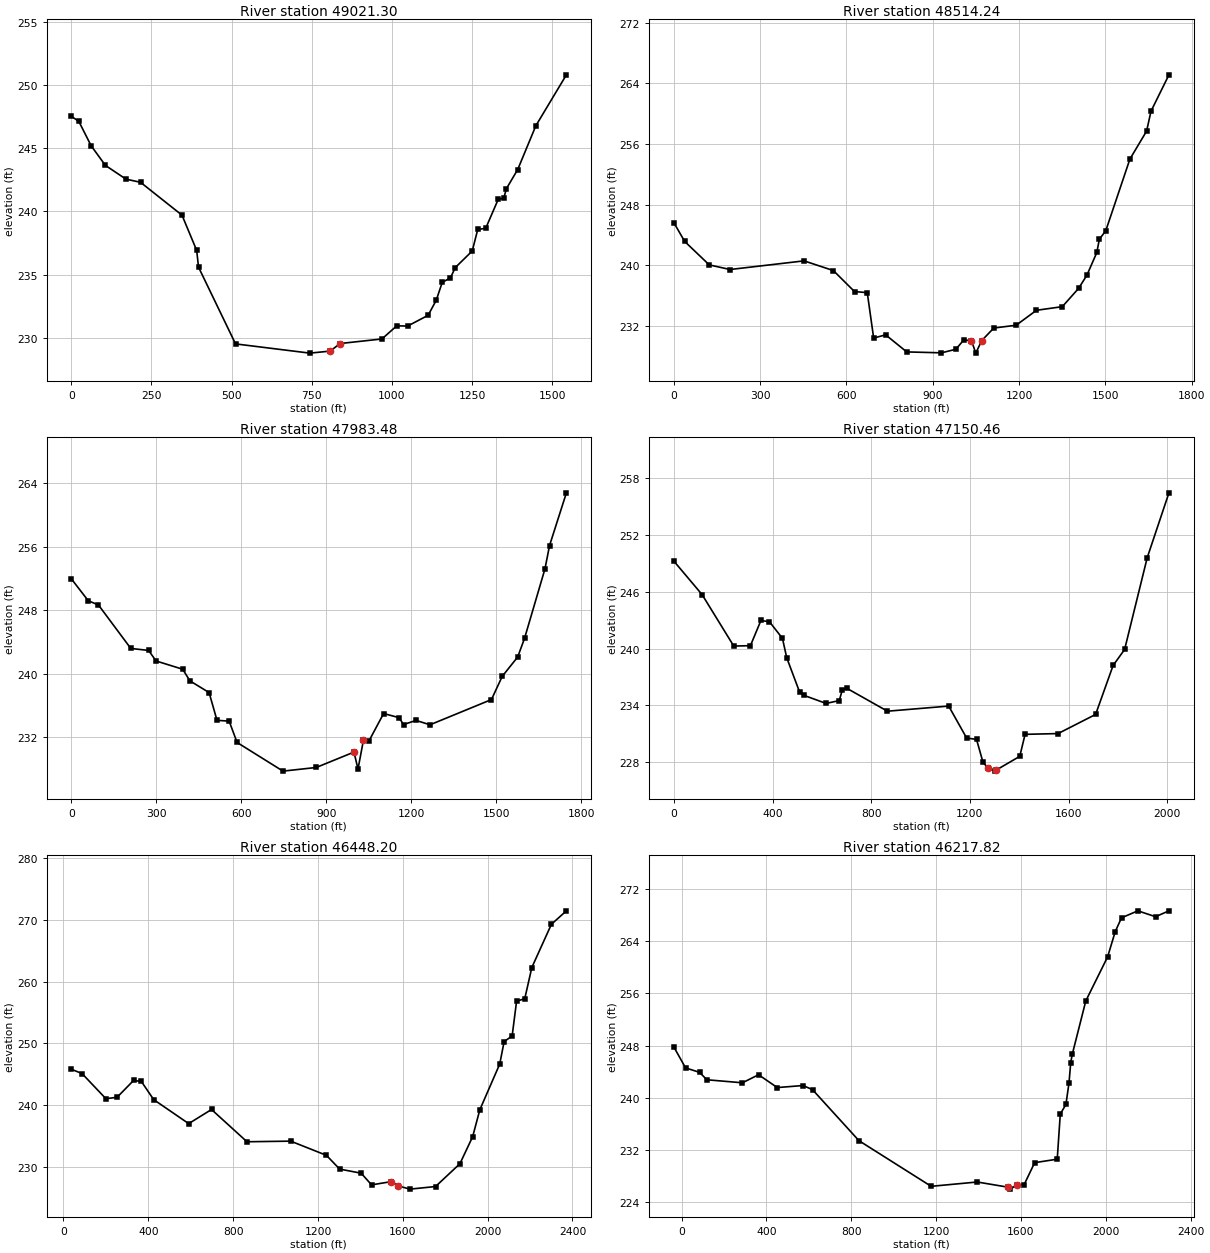
Type RM Length L Ch R = 1 ,49021.30,448.7,507.06,494.18
XS GIS Cut Line= 2
     1835909.038      413568.356     1834887.545      412410.128
#Sta/Elev= 30
       0  247.52   23.45  247.12   61.88  245.19  106.26  243.64   170.5  242.55
  215.96   242.3  345.33   239.7  391.16  236.91  396.84  235.59  512.32  229.52
  744.03  228.79  807.54  228.95  838.57  229.55     969  229.91 1015.11  230.95
 1049.06  230.93 1112.91  231.78 1138.29  232.97 1156.95  234.38 1182.71  234.75
 1197.92  235.56 1250.64  236.87 1267.77  238.57 1292.64  238.66 1331.77  240.96
 1348.81  241.03 1357.04  241.79 1392.46  243.31 1449.19  246.78 1544.32   250.8
#Mann= 0 , 0 , 0
Bank Sta=807.54,838.57
Exp/Cntr=.3,.1

Type RM Length L Ch R = 1 ,48514.24,491.98,530.75,498.95
XS GIS Cut Line= 4
     1836421.645      413438.861     1835943.735      412970.499
     1835476.551      412265.695     1835347.672      412104.597
#Sta/Elev= 30
       0  245.63   37.75  243.15     123  240.06  195.27  239.45  452.61  240.59
  554.56  239.31  627.98  236.54  672.35   236.4  694.57  230.41  736.27  230.83
  809.56  228.58  930.33  228.46  980.34  228.93 1007.55  230.15 1034.48  230.08
 1049.55  228.42  1070.4  230.08 1112.12  231.73 1189.94   232.1 1260.45  234.07
 1350.39  234.55 1406.75  236.95 1435.87   238.7 1470.35   241.7 1479.12  243.45
 1501.31  244.55 1585.26  254.01 1643.39  257.71 1658.64  260.33 1721.04  265.13
#Mann= 0 , 0 , 0
Bank Sta=1034.48,1070.4
Exp/Cntr=.3,.1

Type RM Length L Ch R = 1 ,47983.48,604.09,833.02,405.68
XS GIS Cut Line= 3
     1836684.786      413328.942     1836507.578      412962.444
     1835770.555      411842.813
#Sta/Elev= 30
       0  251.97   59.91   249.2   95.82  248.67  210.02  243.19  272.82  242.94
  299.31  241.61  393.24  240.57  418.48  239.11  486.39  237.63  514.27  234.13
  557.17  234.03   585.2  231.34   747.2  227.73  864.53  228.19  997.84  230.13
 1011.94  227.98 1031.04  231.61 1050.63  231.53 1102.38  234.99 1156.67  234.47
 1172.81   233.6 1216.73  234.12 1266.22  233.57 1483.04  236.75 1520.99  239.67
 1575.59  242.11 1599.78  244.46 1671.74   253.2  1688.1  256.16 1747.53   262.8
#Mann= 0 , 0 , 0
Bank Sta=997.84,1031.04
Exp/Cntr=.3,.1

Type RM Length L Ch R = 1 ,47150.46,418.16,702.26,775.76
XS GIS Cut Line= 3
     1836809.637      413304.777     1836781.445       412241.53
      1835984.01      411738.099
#Sta/Elev= 30
       0  249.22  114.67  245.68  242.82  240.26  310.39   240.3  352.96  242.96
  387.57  242.82  440.06  241.08  457.63  239.02  509.66  235.41  527.35  235.06
  617.02  234.21  670.36  234.51   682.9  235.64  701.54   235.8  865.79  233.39
 1113.98  233.93 1186.47  230.57 1226.89  230.41 1252.98     228 1274.24  227.38
 1303.12  227.07 1304.34  227.15 1402.06  228.63 1423.55  230.95 1557.17  231.03
 1709.46  233.05 1780.28  238.21    1827   239.9 1918.51  249.57 2006.67  256.42
#Mann= 0 , 0 , 0
Bank Sta=1274.24,1304.34
Exp/Cntr=.5,.3

Type RM Length L Ch R = 1 ,46448.20,219.62,230.38,192.73
XS GIS Cut Line= 6
     1836927.342      413178.914     1836917.594       412678.25
     1836798.464      412099.557     1836891.095      411672.648
     1836911.232      411459.193      1836677.64      410915.487
#Sta/Elev= 30
   36.77  245.81   87.64   245.1  199.89  241.03  252.63  241.26  330.49  243.99
  367.26  243.82  425.35  240.88  590.36  236.99  697.97  239.28  865.25  234.05
 1071.33  234.15 1239.83  231.85  1302.2  229.62 1403.77  228.95 1452.62  227.06
  1542.6  227.57 1577.62   226.9 1633.79  226.37 1754.25  226.79 1869.31  230.49
 1929.44  234.88 1963.11  239.23 2057.02  246.65 2077.79  250.29 2115.55   251.2
  2136.5  256.84 2174.99  257.24 2208.41   262.3 2300.68  269.31 2371.39  271.49
#Mann= 3 , 0 , 0
   36.77               0  1542.6               0 1577.62               0
Bank Sta=1542.6,1577.62
Exp/Cntr=.5,.3

Type RM Length L Ch R = 1 ,46217.82,221.29,193.51,178.78
XS GIS Cut Line= 6
     1837118.842      413173.875     1837109.094      412673.211
     1836989.964      412094.518     1837082.595      411667.608
     1837102.732      411454.153      1836869.14      410910.447
#Sta/Elev= 30
  -36.77  247.78   18.44  244.58   84.28   243.9  119.17  242.76  286.51   242.3
  362.77  243.53  450.99  241.57  572.38  241.88  617.09  241.25   836.2  233.44
 1176.68  226.46 1393.83  227.12 1536.76  226.34 1549.21  226.03 1583.46  226.72
  1614.5  226.68 1664.57  230.08 1771.06  230.61 1785.45  237.52 1812.02  238.98
  1826.6  242.29  1834.7  245.38 1841.76  246.63  1905.8  254.83 2008.84  261.58
 2044.34  265.41 2074.15  267.54 2151.26  268.61  2234.7  267.71 2297.85  268.61
#Mann= 3 , 0 , 0
  -36.77               0 1536.76               0 1583.46               0
Bank Sta=1536.76,1583.46
Exp/Cntr=.5,.3

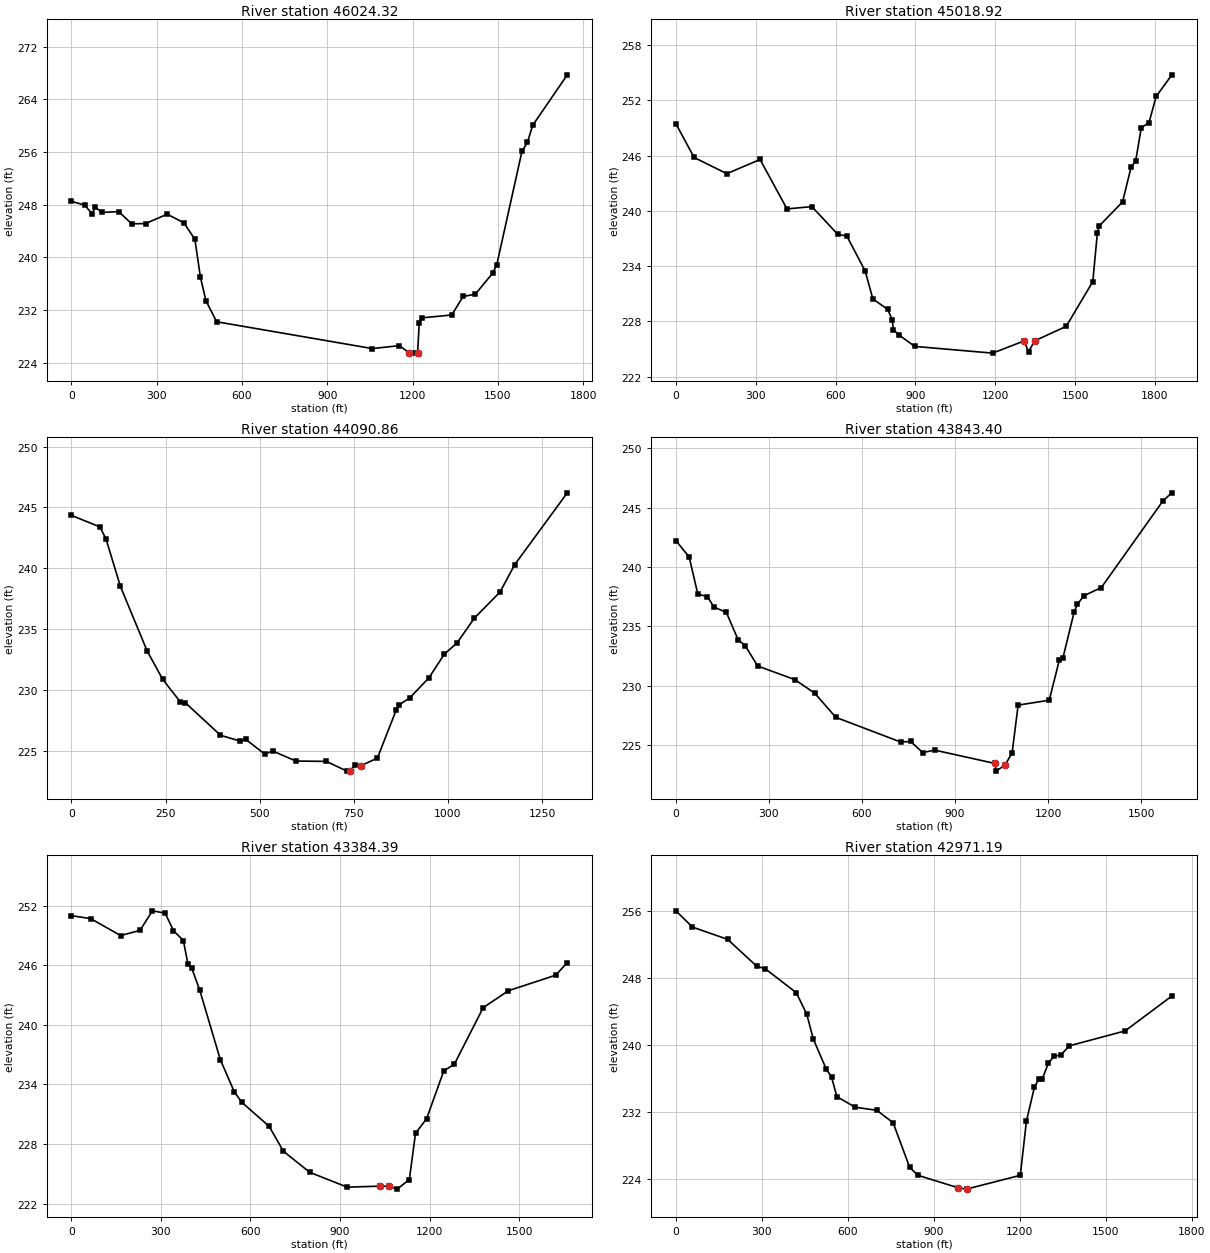
Type RM Length L Ch R = 1 ,46024.32,1016.97,1005.4,786.15
XS GIS Cut Line= 4
     1837409.728      412740.934      1837216.41      412338.189
     1837280.849      411291.052     1837147.943      411081.624
#Sta/Elev= 30
       0  248.52   47.14  247.93   73.68  246.59   83.31  247.63  108.75  246.83
  166.45  246.96  212.43   245.1  260.94  245.14  336.96  246.56  395.75  245.26
  434.44  242.74  453.83  237.02   473.1  233.44  510.89  230.24 1058.48  226.17
 1153.72  226.62 1187.59  225.52 1209.47  225.48 1217.43   225.5 1223.28  230.04
 1232.03  230.83 1337.73  231.27 1377.51  234.08 1420.17  234.41 1481.72  237.63
 1495.99  238.91 1584.37  256.09 1603.52  257.45 1622.23  260.05  1743.9  267.71
#Mann= 0 , 0 , 0
Bank Sta=1187.59,1217.43
Exp/Cntr=.3,.1

Type RM Length L Ch R = 1 ,45018.92,517.35,928.06,885.9
XS GIS Cut Line= 3
     1838307.849      412571.781     1838195.081      411713.934
      1837832.61      410783.593
#Sta/Elev= 30
       0  249.47   68.42   245.8  191.32  244.04  316.28  245.58  417.45  240.21
  510.98  240.46  607.48  237.47  642.46  237.25  711.47  233.45  740.07  230.43
   795.9  229.29  812.82  228.19  817.25  227.09  836.69  226.54  897.69  225.27
 1190.14  224.54 1308.04  225.86 1325.37  224.69  1347.9  225.87 1466.67  227.45
 1566.62  232.31 1583.65  237.57 1590.44  238.35 1678.38  240.97 1710.82  244.79
 1727.41  245.38 1748.89  249.04 1777.46  249.56  1804.7  252.43 1863.69  254.78
#Mann= 0 , 0 , 0
Bank Sta=1308.04,1347.9
Exp/Cntr=.3,.1

Type RM Length L Ch R = 1 ,44090.86,341.65,247.46,149.74
XS GIS Cut Line= 3
     1838336.041      412217.365     1838742.814      411383.683
     1838698.512      410997.048
#Sta/Elev= 30
       0  244.35    75.7   243.4   92.04  242.41  130.36   238.5  200.97  233.22
  242.66  230.86  289.33  229.01  302.41  228.95  396.01  226.27  447.76  225.79
  462.75  225.94     513  224.73  534.99  224.97  596.18  224.15  676.67  224.12
  732.02  223.32  738.72  223.35   754.2  223.79  769.01  223.77  812.56  224.39
  862.51  228.34  870.93  228.78  898.66  229.35  949.44  230.99  990.12  232.93
 1024.25  233.87 1070.25  235.91 1138.36  238.05 1177.01  240.29 1316.79   246.2
#Mann= 0 , 0 , 0
Bank Sta=738.72,769.01
Exp/Cntr=.3,.1

Type RM Length L Ch R = 1 ,43843.40,491.61,459.01,347.32
XS GIS Cut Line= 3
     1839149.587      412527.479     1838795.171      411266.887
     1838746.841      410980.938
#Sta/Elev= 30
       0  242.23   42.85  240.84   70.75  237.71  101.52  237.51  122.63  236.62
  162.57  236.18  200.58  233.87  223.85  233.35   263.7  231.65  383.71   230.5
  447.98  229.35  515.54  227.32  724.42  225.24  756.84  225.28   796.1  224.35
  834.97  224.55 1028.46  223.43 1032.88  222.78 1062.05  223.31 1084.39  224.34
 1103.67  228.35 1203.87  228.76 1236.47  232.13 1248.08  232.32  1284.4  236.21
  1294.8  236.85 1315.38  237.57  1372.1  238.27 1571.35   245.6 1599.47  246.26
#Mann= 0 , 0 , 0
Bank Sta=1028.46,1062.05
Exp/Cntr=.3,.1

Type RM Length L Ch R = 1 ,43384.39,348.12,413.2,288.36
XS GIS Cut Line= 5
     1839818.144      412177.091     1839741.622      411850.867
     1839568.442      411669.632     1838960.296      411125.926
     1838787.116      410932.608
#Sta/Elev= 30
       0  250.99    64.6   250.7  165.08  248.99  229.97  249.51   271.5  251.48
  314.06  251.25  342.12  249.48  375.16  248.49  390.81  246.08  402.94  245.73
  429.91   243.5  499.06  236.48  545.92  233.24  571.33  232.18  662.44  229.78
  710.28  227.26  798.65  225.14  924.08  223.65 1034.61  223.75 1064.73  223.74
 1091.02  223.45 1131.93  224.41 1152.66  229.07 1189.93  230.55  1247.5  235.37
 1282.55  236.02 1379.46  241.73 1463.59  243.43 1622.28     245 1661.05  246.27
#Mann= 0 , 0 , 0
Bank Sta=1034.61,1064.73
Exp/Cntr=.3,.1

Type RM Length L Ch R = 1 ,42971.19,569.17,672.78,666.05
XS GIS Cut Line= 5
     1840321.575      411746.154     1839874.528       411387.71
      1839302.63      411065.514     1839056.955      410932.608
     1838895.857      410779.565
#Sta/Elev= 30
       0  256.07   57.74  254.13  180.72  252.66  282.85  249.43   311.3  249.17
  420.29  246.29  456.68  243.73  479.74  240.74  525.07  237.15  543.09  236.24
  561.86  233.88  625.88  232.62  701.41  232.25  758.18  230.76  815.69  225.46
  844.03   224.5  983.17  223.02 1014.83  222.84 1016.06  222.86 1202.03  224.49
 1223.24  230.94 1251.22  235.01 1266.44  235.95 1278.68  236.01 1300.34   237.9
 1320.16  238.73 1342.88  238.82 1372.92  239.95  1567.7  241.73 1730.94   245.9
#Mann= 0 , 0 , 0
Bank Sta=983.17,1016.06
Exp/Cntr=.3,.1

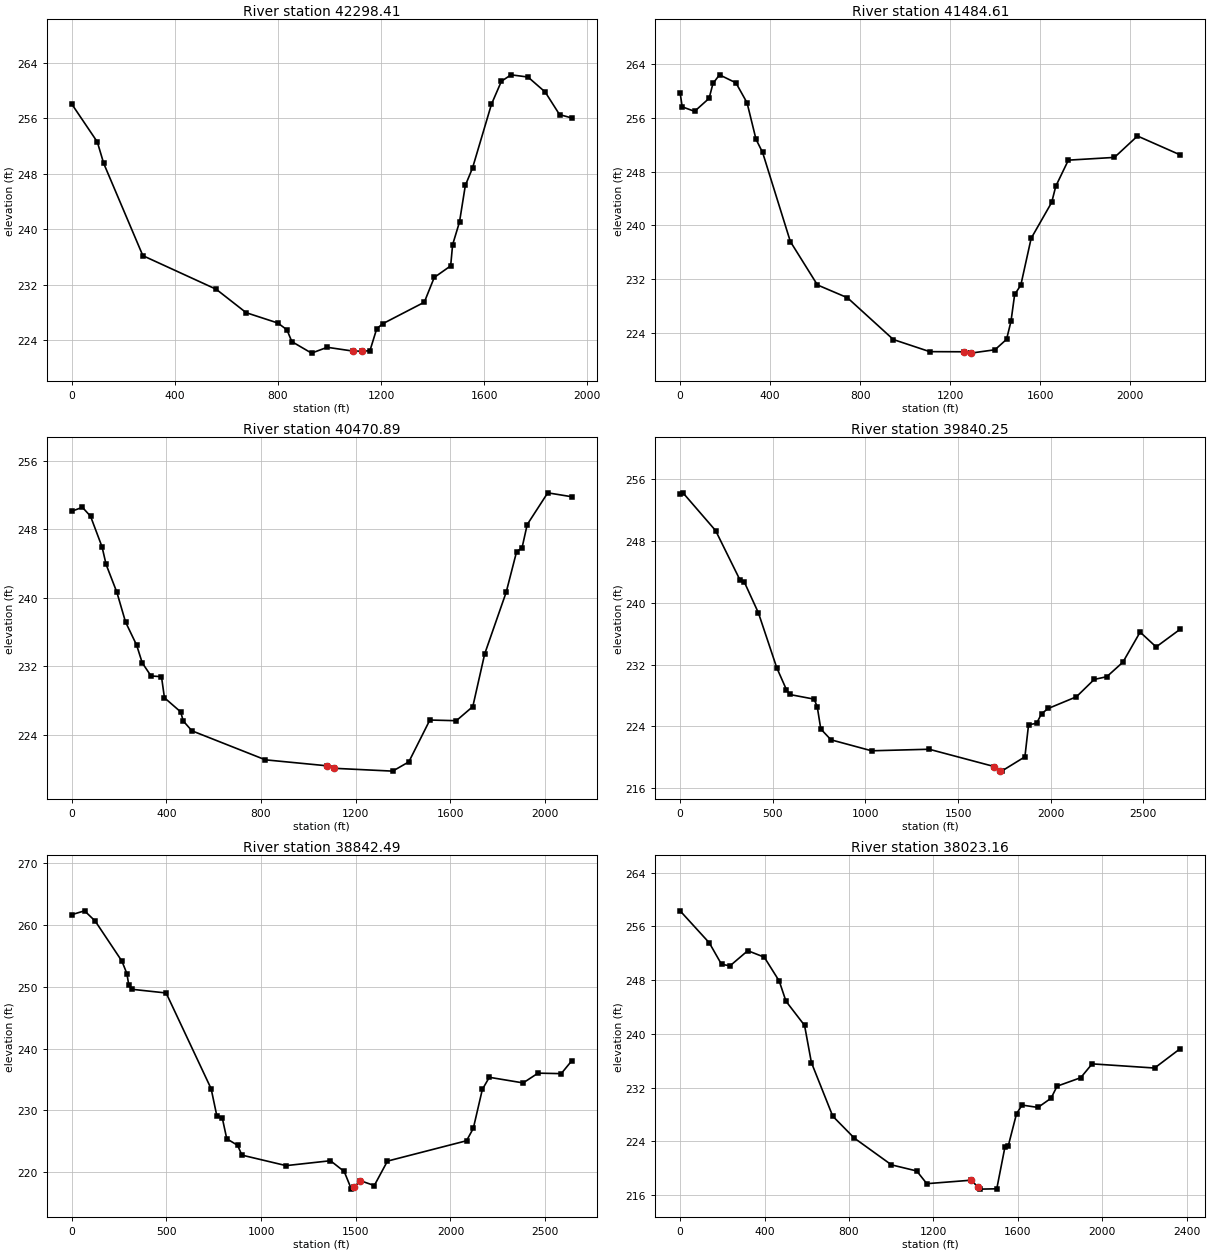
Type RM Length L Ch R = 1 ,42298.41,704.41,813.8,756.26
XS GIS Cut Line= 2
     1840469.562      411678.192     1839455.445      410024.199
#Sta/Elev= 30
       0   258.1   99.83   252.6  124.69   249.5  276.49   236.2  560.83  231.36
  677.16  227.98  799.92  226.49  835.08  225.52  854.22  223.81  930.62  222.15
  991.52  222.99 1092.18  222.44 1127.22  222.43 1157.09   222.5 1183.41  225.67
 1206.83  226.39 1367.91  229.49 1406.47  233.06 1470.15  234.73 1477.64  237.77
 1504.41  241.06 1527.03  246.33 1554.84  248.83 1628.41  258.04 1666.94  261.35
 1704.46  262.27 1770.06  261.95 1836.68  259.79 1892.46  256.53 1940.14  256.05
#Mann= 0 , 0 , 0
Bank Sta=1092.18,1127.22
Exp/Cntr=.3,.1

Type RM Length L Ch R = 1 ,41484.61,865.6,1013.71,809.02
XS GIS Cut Line= 2
     1840992.373      411573.629     1840187.434       409501.35
#Sta/Elev= 30
       0  259.76    9.37  257.64   64.43  256.97  128.84   258.9  146.23  261.12
  175.15   262.4  248.11  261.21  297.58  258.24  337.31  252.82  366.71  250.85
  489.99   237.6  610.28  231.15  743.52  229.25   947.7  223.03 1109.29  221.23
 1260.51  221.21 1290.62  221.01 1291.63  221.01 1399.15  221.51 1450.62  223.06
 1470.41  225.75 1486.61  229.73 1513.97  231.12 1559.91  238.08 1651.19  243.43
 1669.39  245.83  1725.2  249.71 1930.11  250.12 2032.41   253.3 2223.12  250.48
#Mann= 0 , 0 , 0
Bank Sta=1260.51,1291.63
Exp/Cntr=.3,.1

Type RM Length L Ch R = 1 ,40470.89,671.26,630.64,565.59
XS GIS Cut Line= 4
     1841740.389       411110.32     1841402.579      410318.882
     1841209.541      409916.719     1840702.816      409289.346
#Sta/Elev= 30
       0  250.09   45.67  250.56   80.09  249.52  128.84  245.93  145.94  243.88
  191.54  240.62  227.98  237.16  274.86  234.46  298.34   232.4   335.5  230.86
  379.86  230.77  392.26  228.31  460.82  226.66  471.76   225.6  508.26  224.45
   818.6  221.06 1079.78  220.36 1109.36  220.07 1356.11  219.74 1424.45  220.82
 1513.21  225.71 1625.01  225.63 1694.67  227.28 1744.83  233.43 1835.53  240.63
 1879.74  245.39 1902.55  245.82 1924.41  248.54  2011.2  252.25 2113.06  251.79
#Mann= 0 , 0 , 0
Bank Sta=1079.78,1109.36
Exp/Cntr=.3,.1

Type RM Length L Ch R = 1 ,39840.25,994.82,997.76,850.49
XS GIS Cut Line= 6
     1842995.803      410699.016     1842838.732      410642.632
     1842552.783      410618.467      1842399.74       410566.11
     1841437.179      409321.628     1841034.434      409007.487
#Sta/Elev= 30
       0  254.06    15.6  254.21  191.82  249.32   322.6  242.97  346.77  242.66
  422.74  238.68  521.62  231.59  573.72  228.76   591.3  228.13  723.18  227.53
  740.13  226.54  759.21  223.67  814.25  222.27 1033.32  220.85 1343.93  221.05
 1695.39  218.81 1725.09  218.29 1735.18  218.22 1860.61  220.07 1880.31  224.22
 1923.72   224.4 1950.42  225.65 1986.24  226.32 2138.32  227.83 2234.72  230.08
 2302.55  230.43 2389.44  232.31 2482.33   236.2  2568.7  234.28 2699.67  236.59
#Mann= 0 , 0 , 0
Bank Sta=1695.39,1725.09
Exp/Cntr=.3,.1

Type RM Length L Ch R = 1 ,38842.49,788.83,819.33,530.65
XS GIS Cut Line= 6
     1843612.003      409490.781     1843450.905      409563.275
     1843112.599      409514.946     1842862.897      409402.177
     1841666.744      408677.236     1841223.724      408681.263
#Sta/Elev= 30
       0  261.64   68.53  262.27  124.59  260.62   265.7  254.14  292.28  252.11
  302.32   250.2  319.99  249.58  499.17  248.99  736.71  233.51  766.51  229.17
  795.59  228.78  819.23  225.42   876.6  224.36  898.96  222.78 1132.33  221.08
  1366.6  221.87 1439.08  220.13 1476.81  217.28 1492.02  217.57 1523.71  218.65
 1597.91  217.86 1667.29  221.81 2084.59   225.1 2120.48   227.1 2168.24   233.4
 2204.97  235.36 2383.48  234.45 2462.11  236.03 2584.48  235.95 2640.74  238.05
#Mann= 0 , 0 , 0
Bank Sta=1492.02,1523.71
Exp/Cntr=.3,.1

Type RM Length L Ch R = 1 ,38023.16,314.24,421.84,413.07
XS GIS Cut Line= 6
     1843519.372      408604.741     1843217.313      408447.671
      1842999.83      408371.149     1842617.222      408487.945
     1841992.967      408524.192     1841219.697      408532.247
#Sta/Elev= 30
       0   258.3  138.29  253.54  196.17  250.35  236.51  250.12  320.65  252.37
  398.64  251.41  469.47  247.86  501.49  244.86  589.58  241.26  621.87  235.74
  723.09  227.76  825.14   224.5 1001.12  220.52 1120.76  219.61 1168.61  217.72
 1379.14  218.24 1409.95  217.24 1421.05  216.91 1499.91  216.96 1538.55  223.16
 1554.71  223.38 1593.61  228.14 1619.96  229.41 1695.05  229.06 1757.11  230.43
 1785.51  232.22 1897.35  233.48 1951.64  235.54 2247.37  234.92 2369.66  237.82
#Mann= 0 , 0 , 0
Bank Sta=1379.14,1409.95
Exp/Cntr=.3,.1

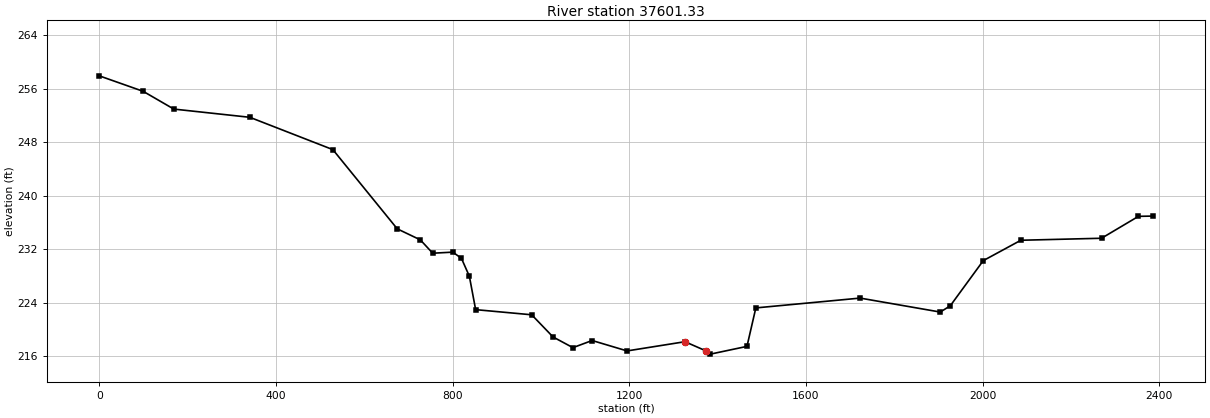
Type RM Length L Ch R = 1 ,37601.33,705.91,684.19,582.36
XS GIS Cut Line= 6
     1843539.509      408560.439      1843048.16       408306.71
     1842758.183      408266.436     1842625.277      408254.353
     1842146.011       408101.31     1841288.163      407819.388
#Sta/Elev= 30
       0  257.94   99.49  255.62  168.92  252.96  341.02  251.73     529  246.89
  674.77  235.03  727.01  233.38   755.1  231.38  800.58  231.54  820.04  230.62
  838.07  227.93  852.25  222.93  979.21  222.16 1027.51  218.84 1072.53  217.24
 1116.05  218.31  1195.1  216.75 1326.23  218.13 1373.93  216.75  1383.7  216.27
 1466.58  217.43 1486.65  223.19 1722.78  224.66 1904.17  222.57 1926.82   223.5
 2001.63  230.27 2086.72  233.32 2269.36  233.62 2352.92   236.9  2385.3  236.94
#Mann= 0 , 0 , 0
Bank Sta=1326.23,1373.93
Exp/Cntr=.3,.1