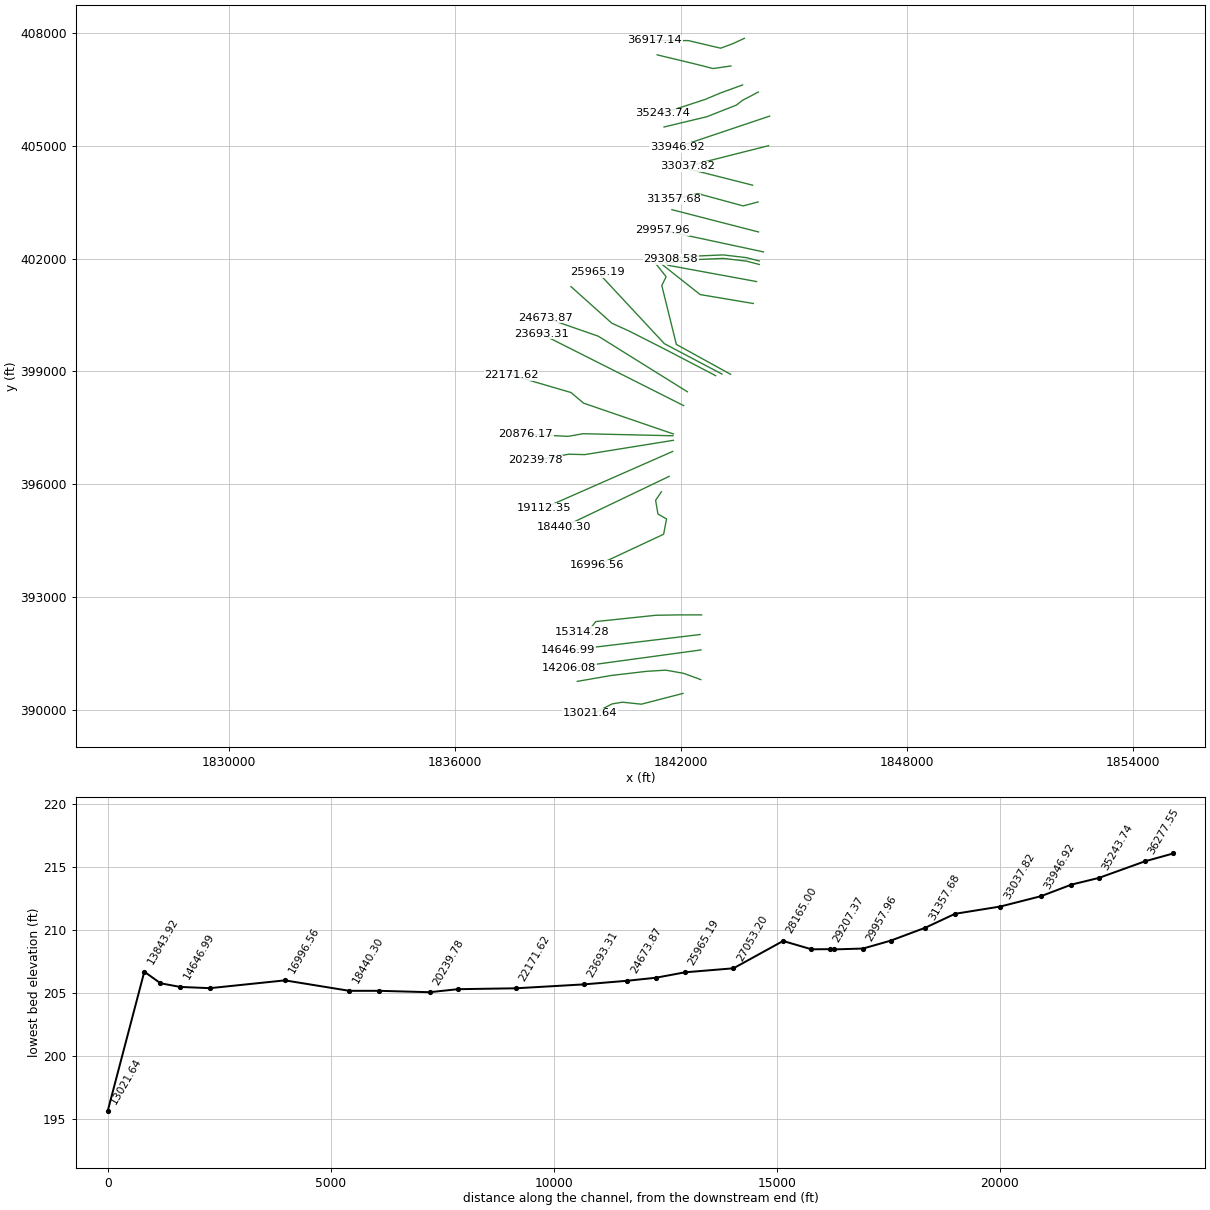
HEC-RAS study gum_limited.prj: Gum Swamp

--- gum_limited.g01 (geometry) --- (continued)

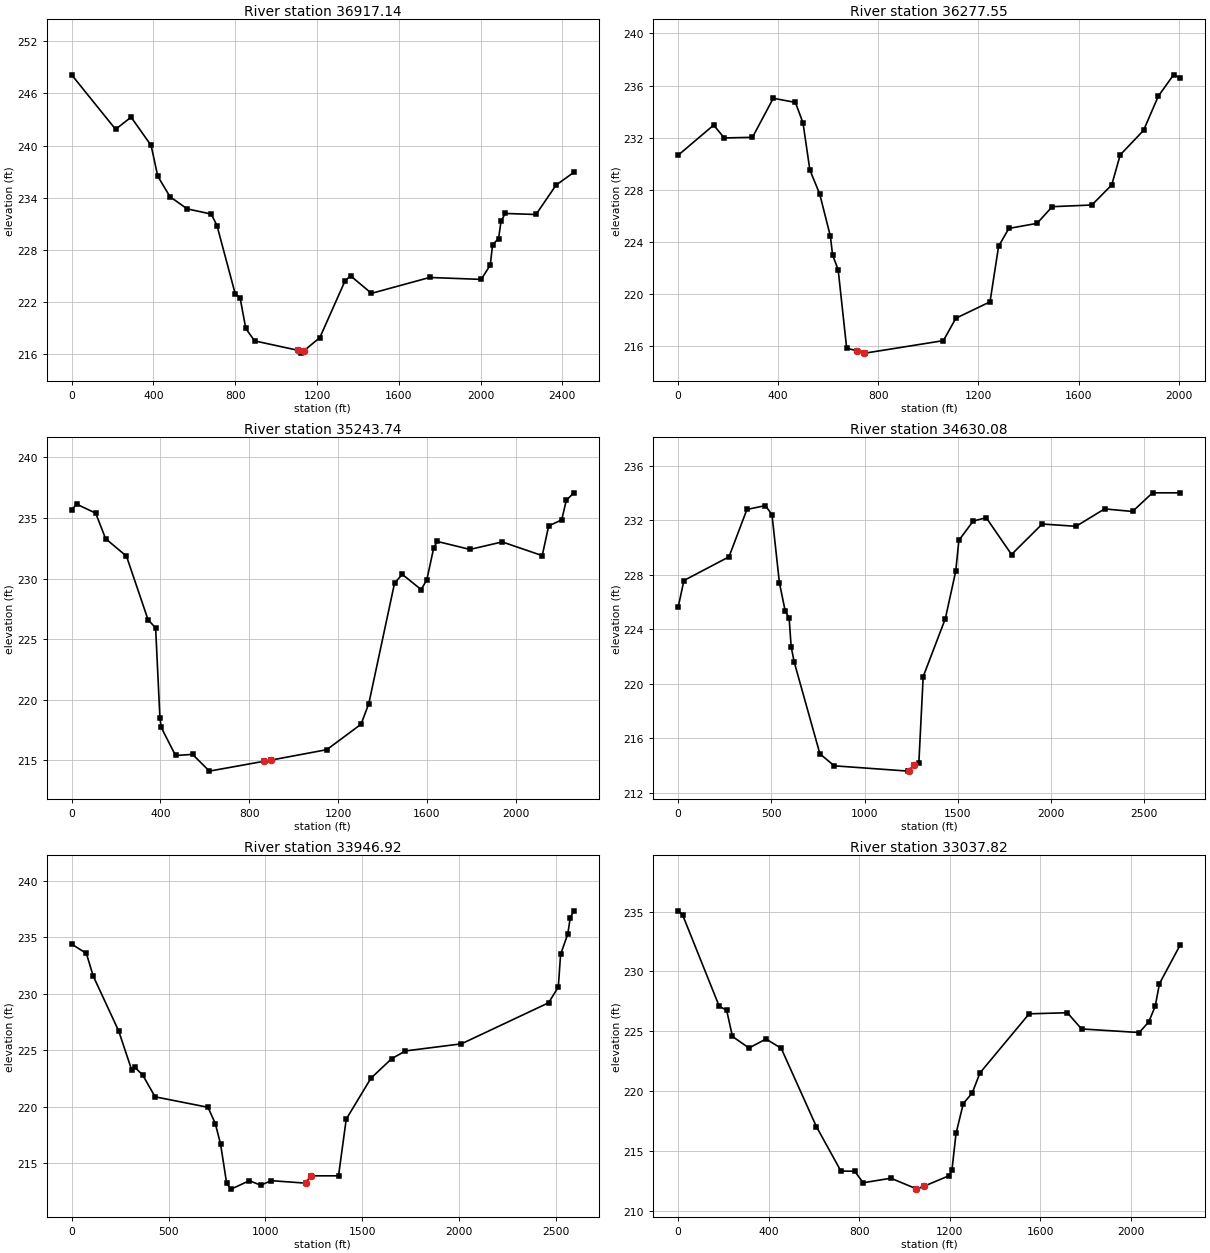
Type RM Length L Ch R = 1 ,36917.14,578.53,639.59,566.89
XS GIS Cut Line= 5
      1843680.47      407847.581     1843374.383       407706.62
      1843048.16      407585.796      1842194.34      407787.169
     1841300.246      407795.224
#Sta/Elev= 30
       0  248.15  214.92  241.87  290.75  243.27  388.64  240.01  421.17  236.46
  481.01   234.1  564.83   232.7  682.64   232.1  710.75  230.78  800.05   222.9
  823.98  222.44   851.6  218.91  894.98  217.48 1107.52  216.39 1122.02  216.07
 1137.52  216.37 1213.93  217.86 1337.63  224.42 1364.13  224.98 1466.53  222.96
 1750.86  224.79 2003.22  224.57 2047.34  226.22 2059.02  228.58 2088.05  229.27
 2100.15  231.28 2120.56  232.17 2271.17  232.05  2369.3  235.44 2456.24  236.91
#Mann= 0 , 0 , 0
Bank Sta=1107.52,1137.52
Exp/Cntr=.3,.1

Type RM Length L Ch R = 1 ,36277.55,850.32,1033.81,985.41
XS GIS Cut Line= 4
     1843322.136      407113.824     1842846.343      407045.278
     1842419.877      407154.859     1841364.685      407408.588
#Sta/Elev= 30
       0  230.64  142.06  232.96  184.11  231.97  297.09  232.02  380.22  235.02
  468.51   234.7  498.91  233.13  526.36  229.51  565.74  227.66  608.36  224.41
  617.05  222.99  639.35  221.85  673.37  215.82  714.24  215.62  744.33  215.46
  747.36  215.44 1059.75   216.4 1109.59  218.12 1246.07  219.38  1280.4  223.65
 1321.31  225.02    1434  225.41 1494.44  226.69 1653.01  226.82 1732.29  228.36
 1766.21  230.67  1859.4  232.55 1918.42  235.18 1979.33  236.82 2006.29  236.58
#Mann= 0 , 0 , 0
Bank Sta=714.24,744.33
Exp/Cntr=.3,.1

Type RM Length L Ch R = 1 ,35243.74,452.94,613.65,447.78
XS GIS Cut Line= 4
     1843632.256      406609.806     1843039.381      406393.775
     1842637.219      406224.866     1841501.618      405853.992
#Sta/Elev= 30
       0  235.66   21.92  236.15  108.37   235.4  152.88   233.3  247.01  231.85
  343.91  226.62  378.22  225.93   397.6   218.5  403.51  217.72  467.96  215.41
  544.75   215.5   620.3  214.12  868.33  214.94  898.23  215.03 1149.25  215.89
 1303.48  217.99 1338.31  219.69 1454.16  229.62 1488.83  230.36 1574.02   229.1
 1599.63   229.9 1630.89  232.55 1646.38  233.07 1794.01  232.41 1939.09  233.03
 2119.44   231.9 2148.42  234.35 2207.22  234.85 2227.82  236.46 2261.83  237.08
#Mann= 0 , 0 , 0
Bank Sta=868.33,898.23
Exp/Cntr=.3,.1

Type RM Length L Ch R = 1 ,34630.08,543.01,683.16,529.06
XS GIS Cut Line= 6
     1844050.995      406421.863     1843626.862      406199.094
     1843471.042      406075.502     1843159.408      405953.573
     1842685.478      405766.401     1841546.842       405492.84
#Sta/Elev= 30
       0  225.61   31.11  227.59  272.89  229.33  369.07  232.81   467.8  233.09
  503.27  232.43  543.28  227.42  574.35  225.34  595.37  224.84  606.12  222.74
  622.21  221.62  760.36  214.86  837.39  213.98 1233.92  213.59 1236.17  213.61
  1263.1  214.05 1291.11  214.22 1314.29  220.53  1433.1  224.79 1488.71  228.27
 1505.74  230.54 1582.65  231.96  1652.6   232.2 1787.95   229.5 1952.49  231.74
 2134.08  231.57 2287.16  232.85 2436.88  232.66 2544.36  234.03 2693.19  234.03
#Mann= 0 , 0 , 0
Bank Sta=1236.17,1263.1
Exp/Cntr=.3,.1

Type RM Length L Ch R = 1 ,33946.92,675.12,909.1,658.82
XS GIS Cut Line= 2
     1844349.027      405781.498     1841892.281       404955.87
#Sta/Elev= 30
       0  234.41   75.96  233.58  111.38  231.57  242.54  226.71  309.72  223.25
  325.63  223.49  366.77  222.79  430.59  220.86  703.75  219.93  741.49  218.48
  768.59  216.67  800.11  213.17  823.02  212.67  917.09  213.42  975.59  213.02
  1030.1  213.42 1207.76   213.2 1233.68  213.85 1377.32  213.85 1417.18  218.88
 1544.66  222.51 1651.33  224.24 1722.67  224.93 2011.62  225.56 2461.41   229.2
 2511.67   230.6 2523.31  233.49 2560.58  235.31 2573.09  236.74 2591.77  237.36
#Mann= 0 , 0 , 0
Bank Sta=1207.76,1233.68
Exp/Cntr=.3,.1

Type RM Length L Ch R = 1 ,33037.82,730.74,1017.22,594.42
XS GIS Cut Line= 2
     1844320.834      404996.145     1842170.175      404452.439
#Sta/Elev= 30
       0  235.06   19.67  234.73  181.58   227.1  214.42  226.77  239.99  224.58
  313.14  223.62  388.14  224.37  455.27   223.6  611.14  217.05  718.99  213.36
  779.93  213.34   817.7  212.38  939.93  212.76 1049.27   211.9 1052.88  211.85
 1084.76  212.08 1198.39  212.98 1209.73  213.46 1227.59  216.49 1259.78  218.99
 1298.82  219.86  1333.3  221.54 1550.52  226.47 1719.37  226.56 1782.04  225.21
 2036.89  224.91 2078.92   225.8 2107.59  227.11 2126.31  228.99 2218.32  232.23
#Mann= 0 , 0 , 0
Bank Sta=1049.27,1084.76
Exp/Cntr=.3,.1

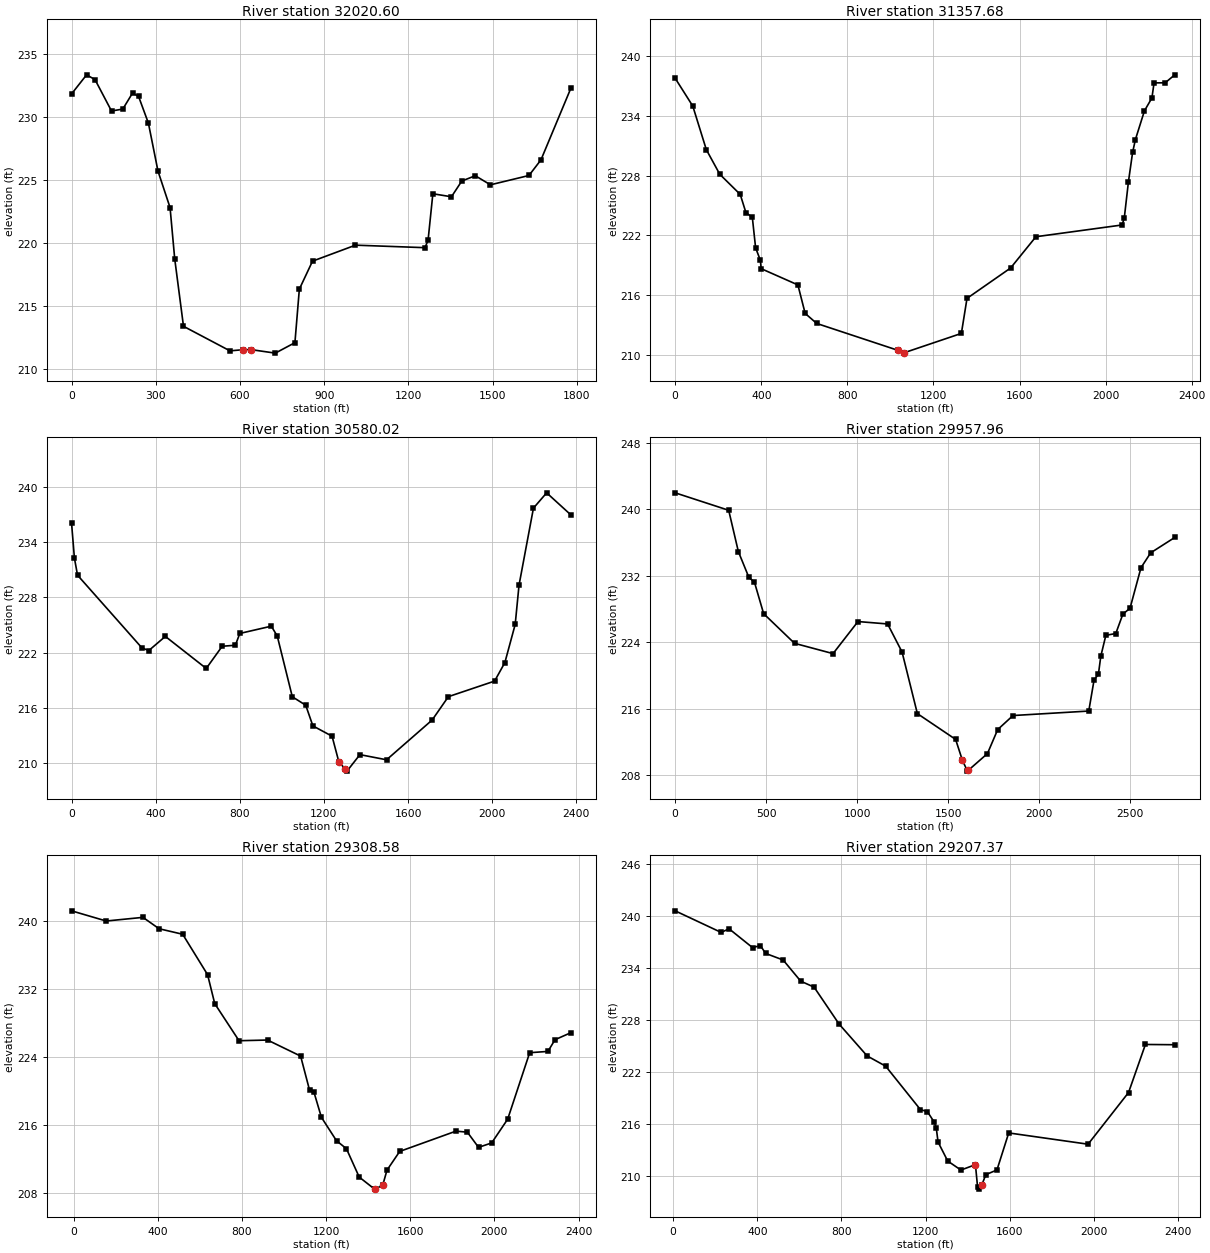
Type RM Length L Ch R = 1 ,32020.60,589.96,662.93,647.75
XS GIS Cut Line= 2
      1843896.67      403947.979     1842171.542      404385.336
#Sta/Elev= 30
       0  231.84   53.66  233.36   83.71  232.98  142.43  230.49  182.59  230.64
  217.25  231.91  238.79  231.65  273.92  229.52  307.97  225.72  351.01  222.82
  367.56  218.76  398.85   213.4  564.46  211.45  610.45  211.54  638.91  211.55
  725.91  211.27  795.77   212.1  811.55  216.35  858.44  218.57  1011.5  219.84
  1259.1  219.64 1270.08  220.23 1287.12  223.92 1353.32  223.68 1390.19  224.93
 1438.31  225.35 1492.25  224.63 1629.46  225.37 1672.24  226.61  1779.7  232.35
#Mann= 0 , 0 , 0
Bank Sta=610.45,638.91
Exp/Cntr=.3,.1

Type RM Length L Ch R = 1 ,31357.68,641.56,777.66,595.45
XS GIS Cut Line= 4
      1844042.94       403501.96      1843648.25      403397.247
     1842444.042       403723.47     1841795.622      403574.454
#Sta/Elev= 30
       0  237.78   81.94  234.98  144.89   230.6  207.43  228.13  302.32  226.11
  328.68  224.29  358.59   223.8  373.75  220.75  395.58  219.51  399.86  218.65
  570.26  217.02  603.95  214.16  657.76  213.15 1035.29  210.45 1062.49  210.17
 1065.47  210.22 1329.81  212.15 1355.98  215.67 1558.56  218.72  1676.2  221.86
  2076.5  223.04 2086.68  223.74 2106.05  227.39 2125.36  230.33 2138.39  231.62
  2180.3   234.5 2215.11   235.8 2224.97  237.31 2276.66  237.32 2321.28  238.12
#Mann= 0 , 0 , 0
Bank Sta=1035.29,1065.47
Exp/Cntr=.3,.1

Type RM Length L Ch R = 1 ,30580.02,543,622.07,561.77
XS GIS Cut Line= 2
     1844056.517      402704.311     1841755.981      403296.873
#Sta/Elev= 30
       0  236.09   13.72  232.26   28.64   230.4  334.49  222.52   367.2  222.22
   446.1  223.76  640.55  220.28   716.4  222.69  779.03   222.8  800.17  224.08
  950.02  224.87  978.25   223.8 1049.82  217.21 1113.69  216.29 1147.63  214.05
 1238.85  212.93 1270.96  210.16 1299.47  209.41  1309.7  209.14 1371.34  210.93
 1498.04  210.37  1714.9  214.69 1791.85  217.22 2011.72  218.91 2060.52  220.92
 2109.61  225.06 2127.82  229.32 2196.39  237.68 2259.18  239.34 2375.62  236.92
#Mann= 0 , 0 , 0
Bank Sta=1270.96,1299.47
Exp/Cntr=.3,.1

Type RM Length L Ch R = 1 ,29957.96,410.89,649.37,520.47
XS GIS Cut Line= 2
     1844186.792      402175.648      1841503.12      402750.181
#Sta/Elev= 30
       0     242  294.09   239.9  347.16  234.93  404.88  231.83  435.82  231.23
  486.03  227.46  655.69  223.89  867.28  222.65 1004.17  226.51 1167.01  226.22
 1246.48  222.84 1330.54  215.43  1540.6  212.33 1578.08   209.8 1605.82  208.51
 1611.01  208.62 1715.38  210.62 1771.76  213.51 1855.86   215.2 2272.04  215.74
 2301.21  219.49 2324.93  220.16 2338.14  222.34 2365.88  224.85 2420.49  225.07
 2459.52  227.41 2498.66  228.11 2558.92  232.99 2612.18  234.78 2744.48  236.63
#Mann= 0 , 0 , 0
Bank Sta=1578.08,1611.01
Exp/Cntr=.5,.3

Type RM Length L Ch R = 1 ,29308.58,93.46,101.21,93.64999
XS GIS Cut Line= 6
     1844073.052      401934.807     1843730.719      402023.411
     1843114.519      402095.905     1842377.495      402063.685
     1841849.899      402007.301      1841721.02      401979.109
#Sta/Elev= 30
    -9.5  241.22  155.41  240.02  330.07  240.45  406.59  239.11  518.76  238.46
  637.12   233.7  671.12  230.29  786.59  225.92  922.09     226  1079.3  224.11
 1121.61  220.11 1142.94  219.84 1178.07   216.9 1249.86  214.14 1297.04   213.2
 1357.77  209.86  1430.8  208.44 1434.16  208.44 1469.77  208.92 1489.66  210.67
 1550.18  212.88 1817.48  215.27 1871.74  215.15 1924.84  213.36 1987.18  213.88
 2063.35  216.68 2167.87  224.51 2254.64  224.66 2288.25  226.04 2364.94  226.88
#Mann= 3 , 0 , 0
    -9.5               0 1434.16               0 1469.77               0
Bank Sta=1434.16,1469.77
Exp/Cntr=.5,.3

Type RM Length L Ch R = 1 ,29207.37,364.28,405.44,265.64
XS GIS Cut Line= 6
     1844076.733      401841.552       1843734.4      401930.156
       1843118.2       402002.65     1842381.176       401970.43
      1841853.58      401914.046     1841724.702      401885.854
#Sta/Elev= 30
     9.5  240.55   228.2  238.06  265.66  238.48  377.18  236.31  414.76  236.54
  439.31  235.64  522.68  234.88  606.24  232.44  669.85  231.75  788.66  227.49
  921.82  223.82 1009.83  222.64 1175.15  217.63 1208.11   217.4 1239.26  216.24
 1250.24  215.54    1259  213.89  1304.8   211.7 1367.63  210.66 1436.54  211.28
 1446.79   208.7 1451.73  208.46  1467.4  208.97 1485.93  210.13 1538.87  210.67
 1594.77  214.94 1971.89  213.64  2164.3   219.6  2244.4  225.14 2383.94  225.11
#Mann= 3 , 0 , 0
     9.5               0 1436.54               0  1467.4               0
Bank Sta=1436.54,1467.4
Exp/Cntr=.5,.3

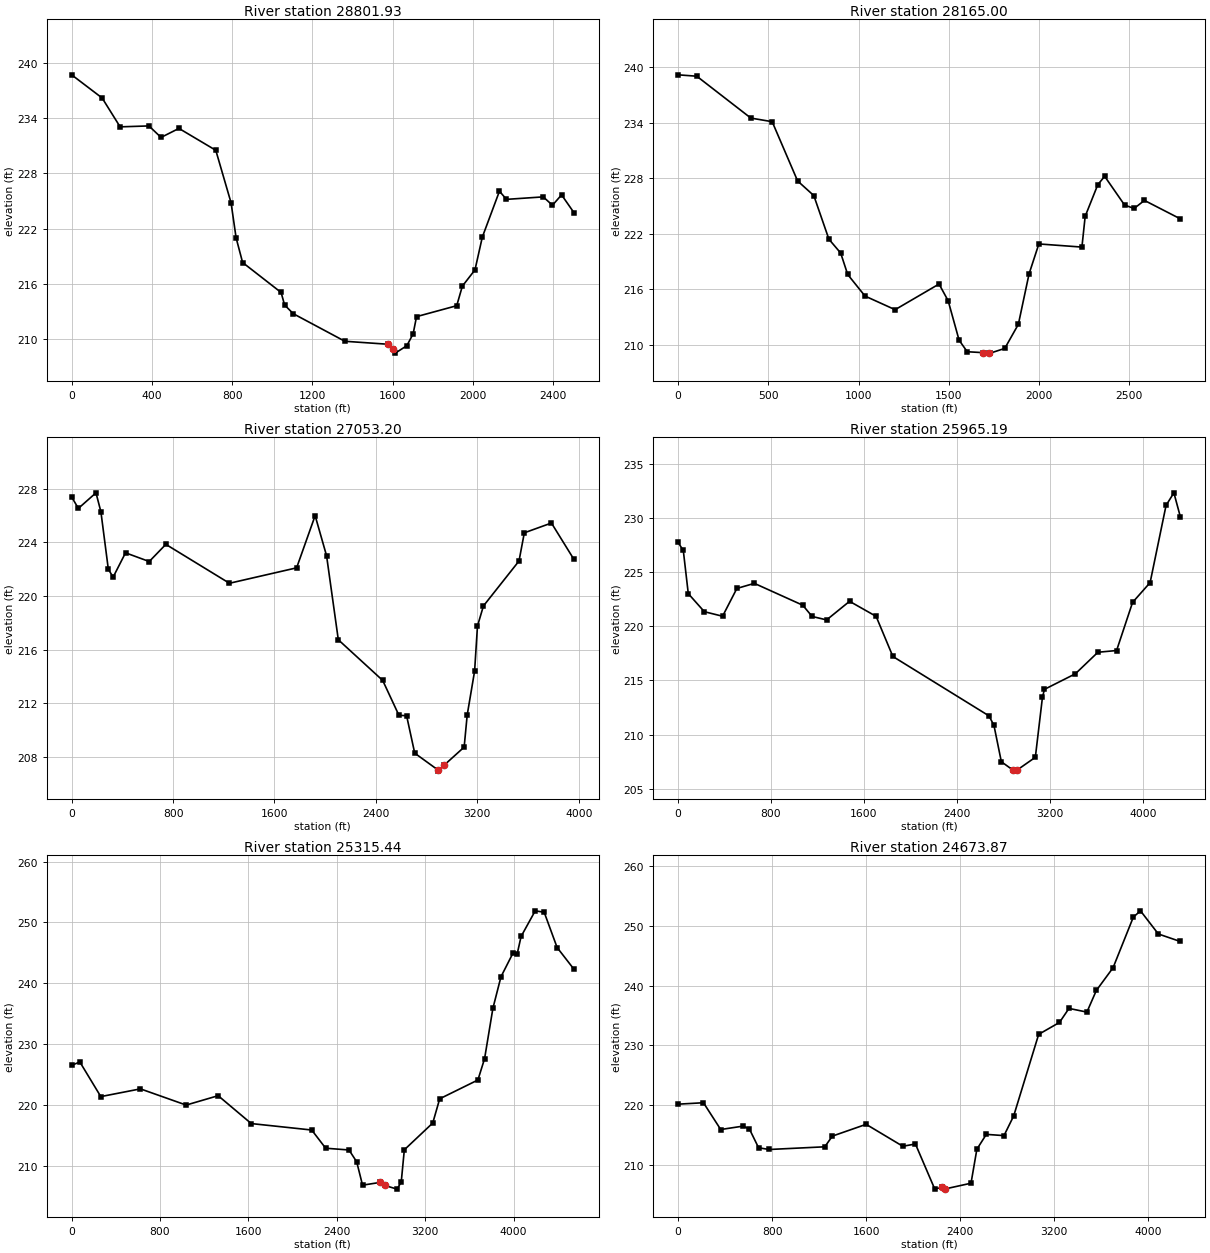
Type RM Length L Ch R = 1 ,28801.93,593.01,636.93,458.33
XS GIS Cut Line= 3
     1844002.666      401387.548     1841658.689      401818.486
      1841578.14       401907.09
#Sta/Elev= 30
       0  238.73  151.89  236.21  241.62  233.07  385.14  233.17  445.59  231.92
   534.8   232.9  718.42  230.52  794.51  224.81  819.71  220.99  852.06  218.31
 1043.96  215.05  1061.3  213.69 1104.55  212.74 1361.74  209.74 1574.39  209.42
 1601.92  208.89 1612.93  208.45 1670.74  209.26 1702.01  210.55 1718.96  212.42
 1919.23  213.61 1947.36  215.74 2010.29  217.51 2046.82  221.07 2132.25  226.07
 2167.17  225.18 2350.65  225.45 2396.35  224.54 2441.92  225.67 2503.01  223.75
#Mann= 0 , 0 , 0
Bank Sta=1574.39,1601.92
Exp/Cntr=.3,.1

Type RM Length L Ch R = 1 ,28165.00,926.43,1111.8,715.68
XS GIS Cut Line= 3
     1843915.158      400805.174     1842505.348      401042.259
     1841443.307      401881.555
#Sta/Elev= 30
       0  239.16  103.48  239.01  403.04  234.49  521.29   234.1  662.29   227.7
  752.11  226.12  835.72  221.41  900.88  219.92  939.87   217.6    1036  215.27
 1202.64   213.8  1446.1  216.57 1496.73  214.76 1557.17  210.51 1602.37  209.26
 1692.22  209.16 1722.83  209.12 1730.13  209.11 1810.38  209.62 1885.71  212.22
 1944.93  217.66 1999.29   220.9 2237.95  220.56    2256  223.88 2326.02   227.3
 2364.05   228.2 2474.33   225.1 2527.17  224.73 2584.44   225.6 2783.25  223.61
#Mann= 0 , 0 , 0
Bank Sta=1692.22,1722.83
Exp/Cntr=.3,.1

Type RM Length L Ch R = 1 ,27053.20,759.93,1088.01,1062.92
XS GIS Cut Line= 5
      1843312.52      398924.947     1841873.093      399718.369
      1841486.53      401281.258     1841601.031      401516.286
     1841323.818      401865.816
#Sta/Elev= 30
       0  227.37   52.96  226.52  191.89  227.68   230.7  226.27  289.41  221.98
  327.33   221.4  424.96  223.21  611.91  222.56     743  223.84 1244.75  220.94
 1774.52  222.09 1920.53  225.98 2010.76  222.99 2103.36  216.73 2453.44   213.7
 2581.47   211.1 2641.98  211.07 2706.01  208.28 2891.64  207.01 2892.43  206.94
 2935.21  207.36 3095.95  208.73 3119.95  211.12 3178.47   214.4 3200.98  217.75
 3248.04  219.25 3528.67   222.6 3570.53   224.7 3784.42  225.43 3961.15  222.73
#Mann= 0 , 0 , 0
Bank Sta=2891.64,2935.21
Exp/Cntr=.3,.1

Type RM Length L Ch R = 1 ,25965.19,451.4,649.75,642.39
XS GIS Cut Line= 3
     1843083.518      398930.973     1841553.379      399739.027
     1839787.094      401636.813
#Sta/Elev= 30
       0  227.76   44.59  227.02   87.52  223.03  225.76  221.36  382.66  220.94
  505.84  223.51  656.32  223.98 1072.88  221.96  1153.4  220.92 1278.24   220.6
 1475.87  222.32 1704.36  220.93 1848.69  217.22 2675.86  211.73 2718.76  210.85
 2782.38  207.49 2881.81  206.72 2898.27  206.62 2914.26  206.69 3075.06   207.9
 3136.29  213.45 3153.46  214.18 3419.74  215.62 3613.57  217.61  3774.4  217.77
 3912.04  222.22 4063.02  224.05 4200.35  231.19  4267.7  232.35 4322.96  230.15
#Mann= 0 , 0 , 0
Bank Sta=2881.81,2914.26
Exp/Cntr=.3,.1

Type RM Length L Ch R = 1 ,25315.44,569.93,641.56,511.53
XS GIS Cut Line= 5
      1842914.78      398888.788     1841589.511      399580.049
     1840624.759      400069.957     1840159.897      400280.902
     1839074.058      401254.136
#Sta/Elev= 30
       0  226.52   73.83  227.09  263.91  221.39  622.51  222.66 1036.41     220
 1326.06  221.54 1625.87  216.96 2172.92   215.9  2299.1  212.91 2510.51  212.62
 2579.93  210.68 2632.84  206.84 2790.86  207.29 2831.77  206.81 2945.33  206.19
  2983.2  207.37 3011.07  212.65 3268.33  217.05 3331.28  221.03 3677.12  224.12
 3737.56  227.63 3812.84   235.9 3885.74  241.07 3996.55  245.04  4032.1  244.79
 4067.96   247.7 4195.85  251.91 4276.93  251.68 4394.05  245.88 4545.38  242.34
#Mann= 0 , 0 , 0
Bank Sta=2790.86,2831.77
Exp/Cntr=.3,.1

Type RM Length L Ch R = 1 ,24673.87,564.78,980.56,614.15
XS GIS Cut Line= 3
     1842165.215      398461.102     1839798.715      399936.684
     1838395.002      400425.513
#Sta/Elev= 30
       0  220.16  215.71   220.4  362.68  215.92  553.33  216.49  607.62  215.98
  685.04  212.87  774.97  212.58 1248.43  213.03 1313.35  214.82 1600.68  216.79
 1912.85  213.12 2020.29   213.5 2185.09  205.95  2244.5  206.27 2274.43  205.99
 2493.47  206.94 2543.35  212.62 2623.73  215.11 2774.31   214.9 2856.86   218.2
 3069.45  231.84  3246.5  233.83  3327.6  236.18 3480.06  235.56 3560.42  239.18
 3702.78  242.98 3875.19  251.44 3936.21   252.5 4088.11  248.63 4275.24  247.37
#Mann= 0 , 0 , 0
Bank Sta=2244.5,2274.43
Exp/Cntr=.3,.1

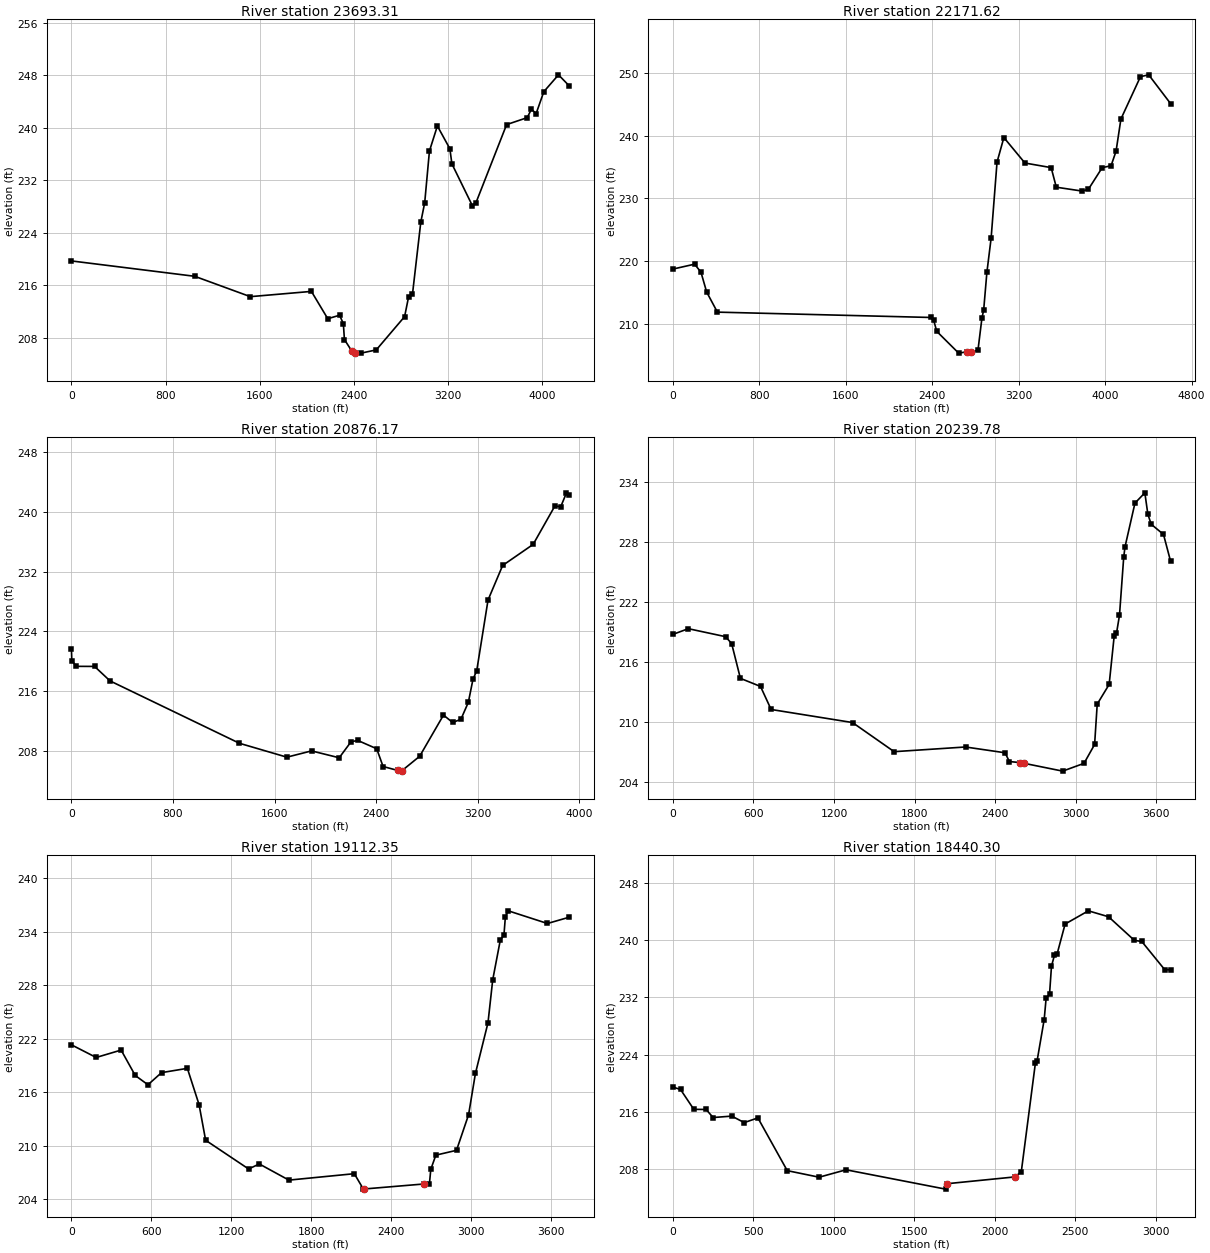
Type RM Length L Ch R = 1 ,23693.31,1099.67,1521.69,1076.24
XS GIS Cut Line= 4
     1842065.812      398093.556     1840128.448      399069.467
     1839706.069      399282.232     1838286.891      399997.117
#Sta/Elev= 30
       0   219.7 1048.15  217.36 1521.15  214.26 2040.46  215.06 2179.54   210.9
 2279.88  211.43 2312.05  210.15 2321.12  207.73 2382.21  206.02 2412.21  205.71
 2462.48  205.66 2591.77  206.15 2832.84  211.22 2866.02  214.17 2899.87  214.65
 2970.42   225.6 3003.74  228.57    3044  236.44 3111.45  240.25 3217.81  236.78
 3234.78  234.49 3408.78  228.12 3439.12  228.54 3700.03  240.46 3875.37  241.52
 3911.11  242.81 3951.08  242.13  4016.3  245.47 4141.29  248.04 4231.29  246.38
#Mann= 0 , 0 , 0
Bank Sta=2382.21,2412.21
Exp/Cntr=.3,.1

Type RM Length L Ch R = 1 ,22171.62,714.83,1295.45,1218.69
XS GIS Cut Line= 4
     1841793.875      397340.011     1839410.755      398157.579
     1839073.277      398440.625     1837494.753      398903.296
#Sta/Elev= 30
       0  218.74  200.77  219.52  259.63  218.24  312.33  215.08  411.67  211.88
 2385.41  211.03 2413.18  210.58 2441.21  208.82  2644.1  205.35 2720.68  205.56
  2753.7  205.53 2822.61   205.8 2859.41  210.93 2875.65  212.24 2905.27  218.21
 2944.35  223.64 2999.12  235.77 3062.38  239.69  3257.3  235.63 3499.97   234.9
 3547.55  231.78 3783.93  231.17 3843.81  231.43 3972.06  234.89 4054.35   235.2
 4100.52  237.52 4145.41  242.64 4326.38  249.39 4402.49  249.68 4604.86   245.1
#Mann= 0 , 0 , 0
Bank Sta=2720.68,2753.7
Exp/Cntr=.3,.1

Type RM Length L Ch R = 1 ,20876.17,486.66,636.39,524.82
XS GIS Cut Line= 4
     1841781.822        397291.8     1839394.425      397346.544
     1838997.073      397275.783     1837870.333      397335.658
#Sta/Elev= 30
       0  221.63    3.06  220.07   39.59  219.32  182.23  219.31  304.03  217.37
 1323.59  209.01 1697.07  207.15 1891.34  207.99 2109.23  207.07 2202.73  209.22
 2255.78  209.39 2404.53  208.28 2454.82   205.9 2570.99  205.37 2589.22  205.28
 2604.17  205.35 2742.96  207.27 2930.74  212.79 3002.35   211.8 3067.71  212.22
 3126.47   214.5 3162.96  217.59 3192.35  218.72  3281.6  228.21  3396.7  232.84
 3636.84  235.66 3807.88   240.8 3854.25  240.71 3899.59  242.57 3919.96  242.29
#Mann= 0 , 0 , 0
Bank Sta=2570.99,2604.17
Exp/Cntr=.3,.1

Type RM Length L Ch R = 1 ,20239.78,723.46,1127.43,1097.5
XS GIS Cut Line= 4
     1841793.875      397171.273     1839437.971      396791.339
     1839013.402      396802.225     1838132.373      396639.318
#Sta/Elev= 30
       0  218.75  114.59  219.32  391.99  218.52   437.5  217.83  502.73  214.34
  652.58  213.53  731.53  211.22 1337.84  209.91 1648.05  206.99 2179.64  207.46
 2474.17  206.88 2506.26     206 2583.79   205.9 2613.45  205.83 2903.27  205.04
 3062.29  205.82  3141.2  207.71 3160.69  211.76  3249.5  213.73    3287  218.57
 3304.18  218.85 3326.56  220.67  3357.9  226.47 3367.45  227.51 3441.76  231.91
 3515.44  232.94  3537.8   230.8 3562.76  229.79 3654.32  228.77 3707.02  226.09
#Mann= 0 , 0 , 0
Bank Sta=2583.79,2613.45
Exp/Cntr=.3,.1

Type RM Length L Ch R = 1 ,19112.35,609.04,672.05,671.65
XS GIS Cut Line= 2
     1841775.921      396875.912     1838354.776      395370.667
#Sta/Elev= 30
       0  221.33  185.87  219.91  373.21  220.74  479.29  217.89  574.81  216.85
  676.62  218.21  870.75  218.69  958.72  214.62 1007.92  210.63 1330.55  207.41
 1411.24  207.97 1633.44  206.16 2124.65  206.88 2192.84  205.15    2194  205.16
 2649.99  205.73 2688.73  205.75 2699.08  207.37 2737.01  208.96 2892.12   209.5
 2982.81  213.49 3034.24  218.12 3128.57   223.8  3164.2  228.62 3221.58  233.11
 3248.22   233.6 3259.35  235.71 3281.05  236.35 3575.06  234.93 3737.65  235.63
#Mann= 0 , 0 , 0
Bank Sta=2194,2649.99
Exp/Cntr=.3,.1

Type RM Length L Ch R = 1 ,18440.30,1378.27,1443.74,20921.76
XS GIS Cut Line= 2
     1841681.283      396213.449     1838890.946      394877.531
#Sta/Elev= 30
       0  219.45   47.34  219.11  129.88  216.33   206.5  216.31  249.96  215.18
  365.84  215.38  443.59  214.47  528.24  215.13  710.74  207.74  908.96  206.82
 1076.17  207.86 1695.01  205.15  1704.6  205.91 2125.34  206.86 2165.62  207.57
 2253.58  222.85 2263.37  223.05 2308.04  228.91 2320.13  231.91 2341.19  232.43
 2353.41  236.39 2371.64   237.9 2389.06  238.16 2438.14  242.29 2582.66  244.14
 2708.07  243.31 2868.85     240 2914.57  239.85 3057.17   235.9 3093.65  235.88
#Mann= 0 , 0 , 0
Bank Sta=1704.6,2125.34
Exp/Cntr=.3,.1

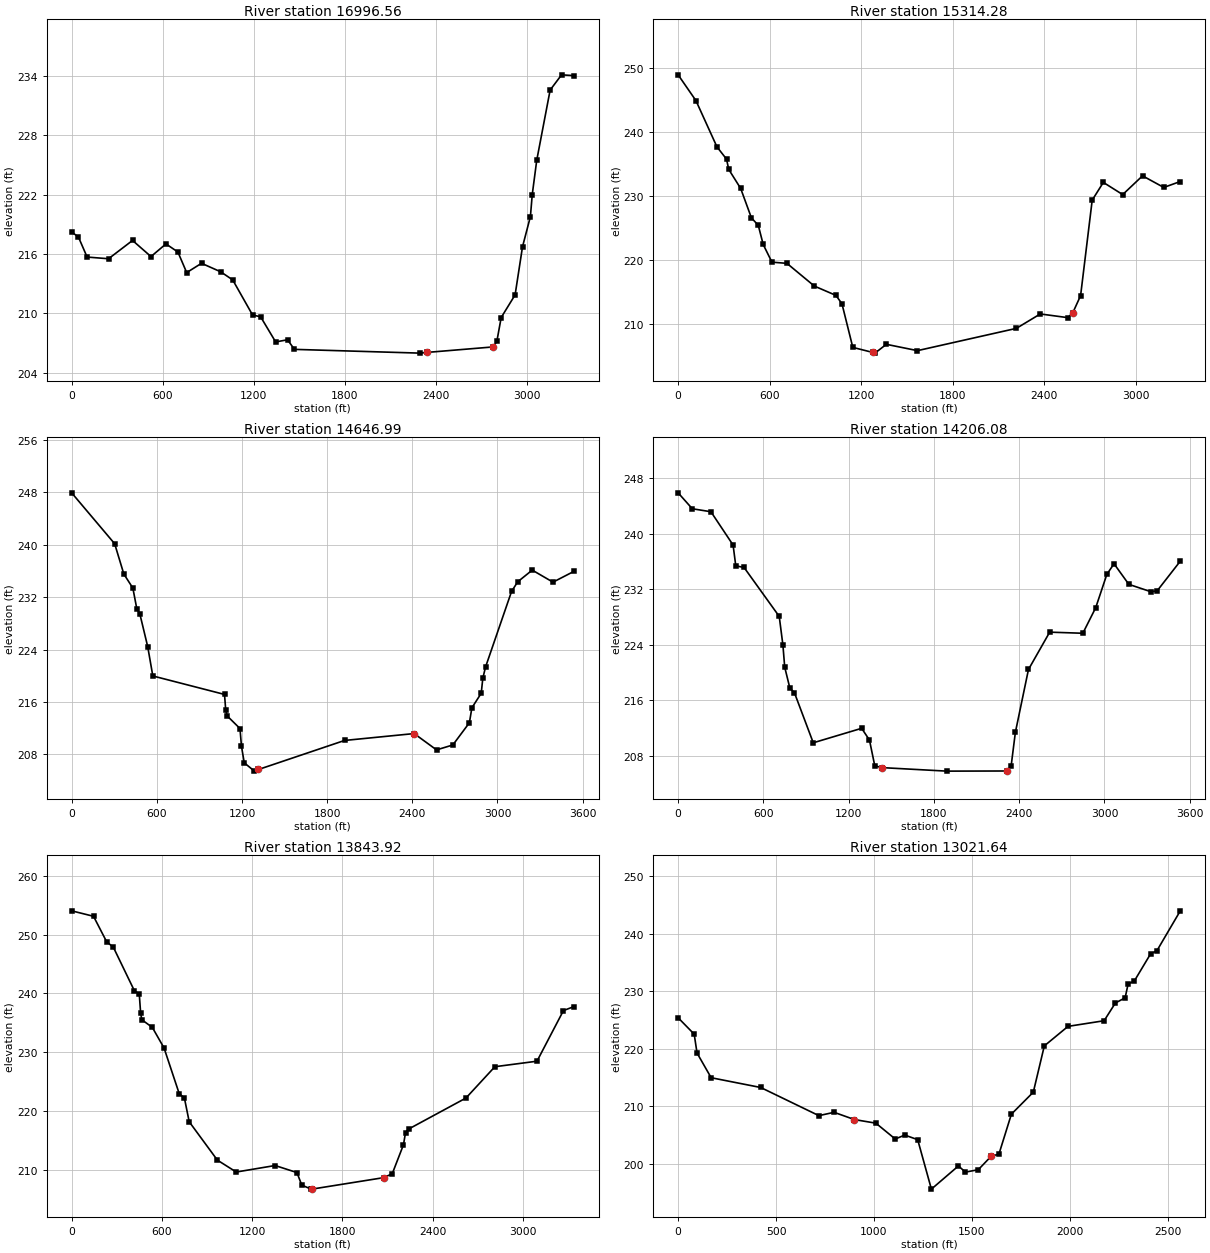
Type RM Length L Ch R = 1 ,16996.56,1886.59,1682.28,35351.56
XS GIS Cut Line= 6
     1841476.625      395805.234     1841321.812      395577.002
     1841384.999      395214.049     1841612.781      395082.831
     1841534.741      394676.355     1839769.015      393850.743
#Sta/Elev= 30
       0  218.23   44.84  217.71  101.93  215.69  243.28  215.52  401.46  217.37
  523.15  215.74  621.91  217.02  700.63   216.2  758.56  214.12  856.38  215.06
  982.96   214.2 1062.12  213.38 1192.74  209.84 1246.14  209.65 1345.23  207.11
 1423.63  207.33 1468.84  206.36 2297.08  205.98 2341.22  206.05 2781.65  206.61
 2804.23  207.21 2832.46  209.58 2924.18  211.87 2973.02  216.73 3025.14  219.79
 3037.23  222.01 3066.83  225.47 3155.19  232.57 3230.56  234.11 3311.49  234.03
#Mann= 0 , 0 , 0
Bank Sta=2341.22,2781.65
Exp/Cntr=.3,.1

Type RM Length L Ch R = 1 ,15314.28,654.18,667.29,665.24
XS GIS Cut Line= 6
     1842543.113      392534.437      1841931.93      392534.437
      1841325.97       392523.99     1839732.714      392356.828
     1839586.448      392168.772     1839367.049      392090.415
#Sta/Elev= 30
       0  248.98   116.7  244.94  254.46  237.69  317.02  235.77  331.83  234.15
  409.89  231.17  480.07  226.57  525.26  225.39  557.44  222.39   614.7  219.62
  713.05  219.43  892.63  215.87 1034.04  214.41 1073.48   213.1 1144.57  206.26
 1276.69  205.46 1289.67  205.36 1364.32  206.74 1568.26  205.75 2216.18  209.24
 2372.99   211.5 2553.52  210.92 2586.29   211.7 2637.13  214.37 2713.17  229.34
 2786.04  232.12 2912.98  230.21 3042.97  233.15 3182.17  231.33 3290.45  232.26
#Mann= 0 , 0 , 0
Bank Sta=1276.69,2586.29
Exp/Cntr=.3,.1

Type RM Length L Ch R = 1 ,14646.99,433.77,440.9,455.4
XS GIS Cut Line= 2
     1842504.327      392012.834      1838991.37      391592.188
#Sta/Elev= 30
       0  247.92  303.07  240.15  367.62  235.53  431.24  233.39  459.14  230.22
  479.86   229.5  535.97  224.44  571.84  219.98 1077.03  217.16 1085.61  214.71
  1097.2  213.85 1185.89  211.96 1196.47  209.25 1215.99  206.73 1287.56  205.46
 1316.16  205.71 1922.76  210.14 2412.95  211.19 2570.73   208.7 2685.51  209.45
 2802.17  212.84  2819.7  215.12 2885.55  217.34 2896.79  219.63 2916.07  221.35
 3099.37  232.88 3142.82  234.35 3244.94  236.13  3391.2  234.29 3538.05  235.93
#Mann= 0 , 0 , 0
Bank Sta=1316.16,2412.95
Exp/Cntr=.3,.1

Type RM Length L Ch R = 1 ,14206.08,380.12,362.17,364.26
XS GIS Cut Line= 2
     1842527.065      391603.557     1839025.476      391126.068
#Sta/Elev= 30
       0  245.92   99.87  243.62   230.9  243.19   386.9  238.38  405.76  235.38
  463.92  235.15  711.57  228.08  737.61  223.92   750.1  220.76  786.76   217.7
  818.08  217.09     951  209.84 1291.57  211.93 1346.61  210.23 1383.82  206.53
 1431.27  206.26 1890.54  205.75 2314.77  205.77 2343.93  206.56 2373.33  211.35
 2465.47  220.42 2614.78  225.81 2848.17  225.65  2938.7  229.34 3017.06  234.15
 3067.59  235.68 3171.85  232.71 3327.71  231.64 3371.68  231.79    3534  236.06
#Mann= 0 , 0 , 0
Bank Sta=1431.27,2314.77
Exp/Cntr=.3,.1

Type RM Length L Ch R = 1 ,13843.92,887.58,822.28,773.49
XS GIS Cut Line= 6
     1842522.218       390815.81     1842062.524      390982.971
     1841592.383      391066.552     1841080.452      391035.209
     1840145.393       390925.51     1839241.678      390768.796
#Sta/Elev= 30
       0  254.05  145.37  253.12  232.06  248.81  277.83  247.82  417.09  240.44
  449.49  239.88  458.54  236.64  466.56  235.51  536.33   234.2  614.36  230.69
  714.78  222.94  749.66  222.16   781.4  218.14  968.62  211.61 1094.09  209.58
 1352.43  210.69 1497.52  209.49 1529.57  207.36 1591.98  206.67 1599.01  206.68
 2073.03  208.62 2131.11  209.29 2205.67  214.22 2219.43  216.31 2239.44  216.89
 2621.16  222.18 2813.24  227.51 3093.26  228.45 3269.12  237.07 3338.22  237.74
#Mann= 0 , 0 , 0
Bank Sta=1599.01,2073.03
Exp/Cntr=.5,.3

Type RM Length L Ch R = 1 ,13021.64,190.54,157.69,202.48
XS GIS Cut Line= 6
     1842048.978      390448.586     1840941.601      390162.718
      1840440.61      390216.137     1840166.022      390169.688
     1839713.067       389937.09     1839584.526      389918.727
#Sta/Elev= 30
       0  225.41   82.12  222.55   96.61  219.27  168.74  214.97  421.84  213.27
  718.98  208.37  796.65  208.95  900.33  207.69 1010.16  207.06 1109.12   204.3
 1157.44  204.99 1223.66  204.19 1293.65  195.58 1431.83  199.62 1467.34  198.54
 1533.16  198.96 1600.58  201.36  1638.3  201.64 1702.26  208.63 1814.25  212.46
 1870.44  220.51 1991.51  223.91 2175.94  224.89 2233.46  227.98 2283.22  228.88
 2298.54  231.31 2329.78  231.78  2413.2  236.53 2445.39  237.07 2565.03  244.02
#Mann= 3 , 0 , 0
       0               0  900.33               0 1600.58               0
Bank Sta=900.33,1600.58
Exp/Cntr=.5,.3