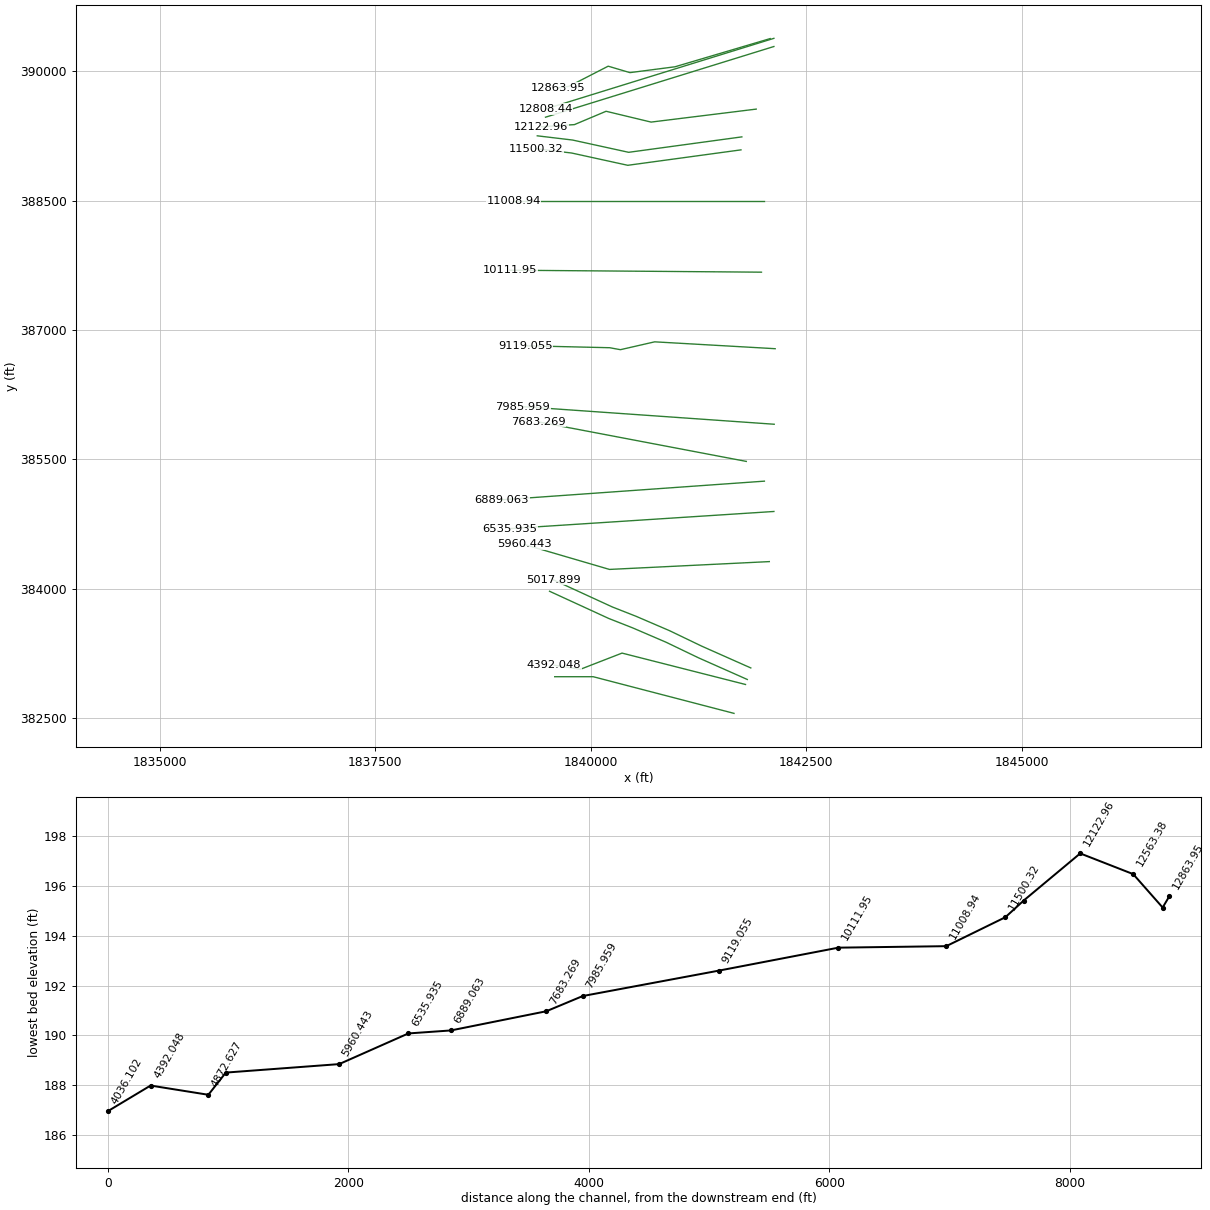
HEC-RAS study gum_limited.prj: Gum Swamp

--- gum_limited.g01 (geometry) --- (continued)

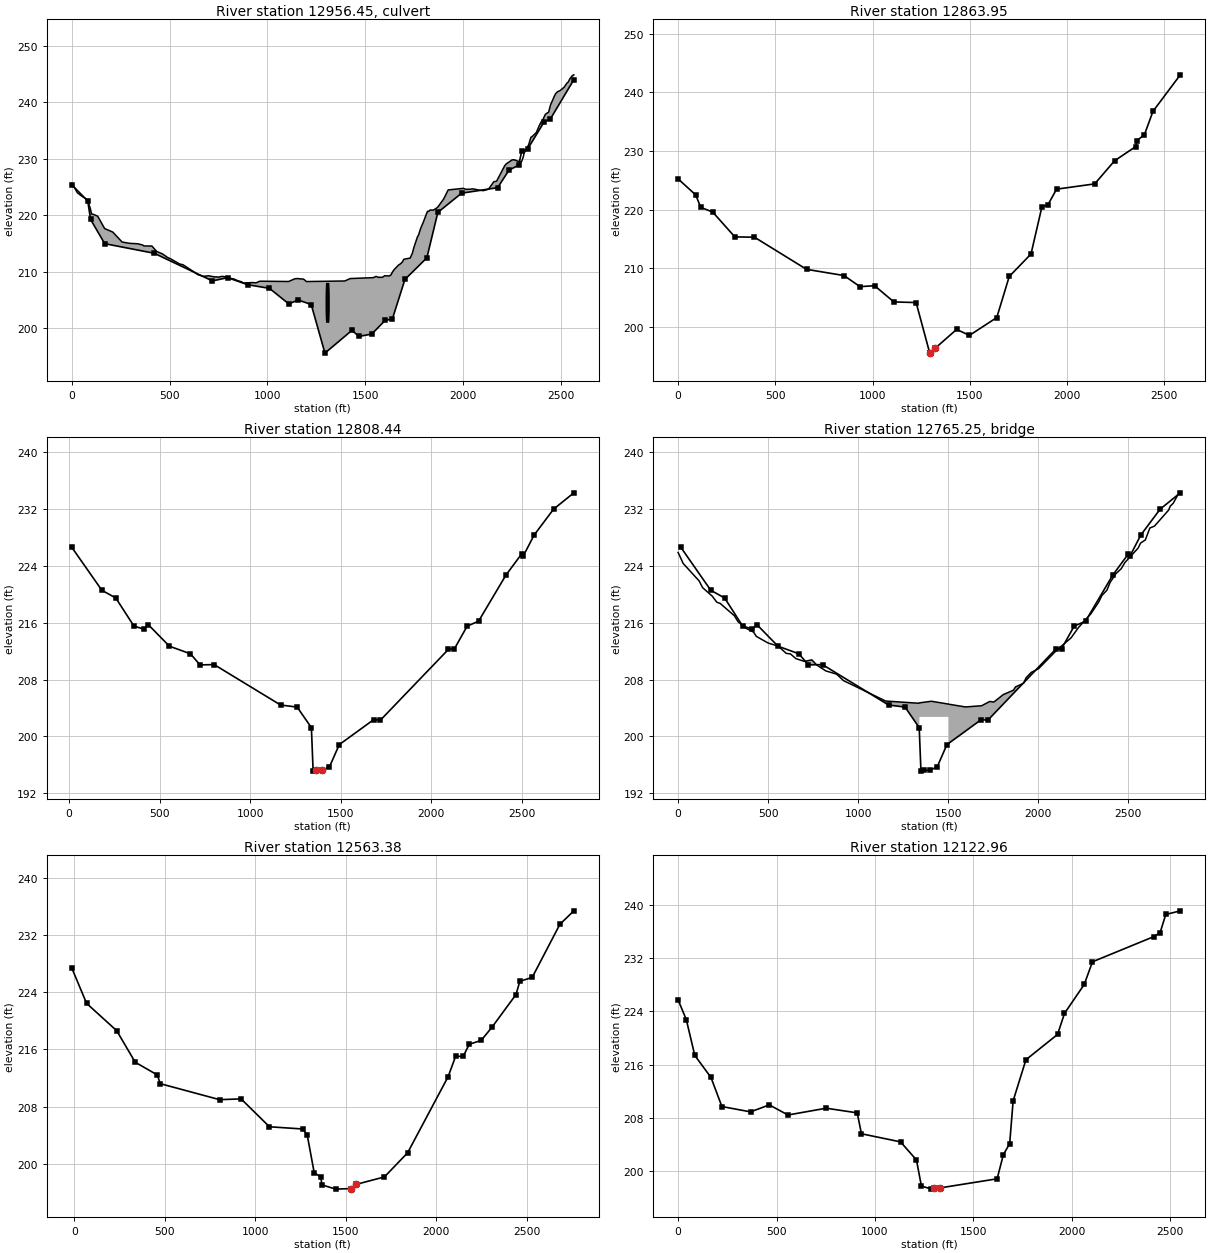
Type RM Length L Ch R = 2 ,12956.45,,,
BEGIN DESCRIPTION:
Laurel Mill Dam (SCOTL-008)
END DESCRIPTION:
Bridge Culvert--1,0,-1,-1, 0
Deck Dist Width WeirC Skew NumUp NumDn MinLoCord MaxHiCord MaxSubmerge Is_Ogee
50.19,30,2.6,0,169,169,208,,.95,0,0,0,,
       0    8.51   10.66   20.74   29.04   50.31   50.73   51.05   55.51   70.98
   72.17   82.32   84.73   95.11     102   107.4  132.89  168.48  210.26  257.67
  296.32   338.6  363.34  368.98   410.1  434.07  464.34  489.25  507.98  550.19
  569.59  622.79   647.2  650.76  668.87  671.63  681.45  698.75  733.66  741.05
  745.13  752.57  764.19  775.72  776.44  801.31  806.09  815.16  826.62  846.32
  868.53  873.63  881.22  920.79  941.81  959.99  967.63 1098.27 1098.47  1108.3
 1128.42 1129.08 1135.02  1139.2 1140.41 1141.84 1143.68 1150.53 1158.34 1161.59
 1179.38 1183.11 1187.85 1199.19 1394.63 1401.71 1412.66 1421.93 1422.96 1495.11
 1518.71 1540.29 1554.93 1568.65 1572.27 1586.99 1598.91 1621.99 1631.23 1639.02
 1647.51  1669.9 1679.48 1689.66 1696.73 1729.15 1740.65 1748.12 1758.28 1766.26
 1771.57 1782.72 1791.53 1796.28 1814.41 1818.58 1824.42 1830.35 1847.34 1862.81
 1869.99 1900.38 1923.04 2000.45 2005.62 2013.45 2036.36 2047.26 2062.72  2077.8
 2094.58 2100.64 2102.62 2129.36  2156.3 2168.51 2171.09 2212.44 2214.61 2215.87
  2220.6 2243.25 2249.26  2255.7  2263.8 2284.85 2292.09 2296.82 2306.37 2311.56
 2319.82 2334.66 2345.97  2350.3 2355.47  2373.7 2387.61 2397.13 2407.61 2417.56
 2419.41    2421 2435.19 2436.31 2445.79 2464.81 2472.04 2481.45 2493.43 2512.35
 2514.54 2516.68 2530.62 2536.23  2544.1 2547.58 2549.96 2558.14 2565.03
  225.65  225.26  225.12   224.5     224  223.41   223.4   223.4   223.3  222.97
  222.92   222.7  222.31  221.23   220.2  220.21  219.84  217.65  217.02  215.26
  215.03  214.95  214.72  214.57  214.55  213.59  213.15  212.54  212.24  211.39
  211.22  210.01  209.43  209.44  209.21   209.2  209.21  209.28  209.07   209.1
  209.04  209.05  209.17  209.15  209.15  208.99  208.93  208.78  208.74  208.44
   208.2  208.06     208  208.08  208.03  208.31  208.32  208.29  208.29  208.27
  208.59  208.58  208.69  208.74  208.74  208.75  208.77  208.78  208.79  208.75
  208.71   208.7   208.6  208.26  208.36  208.46  208.63  208.77  208.79  208.88
   208.9  208.95  209.17     209  209.01  209.01  209.29  209.25  209.45  209.97
  210.39  211.19   211.4  211.75  212.21  212.42  213.33  214.31  215.39  216.18
  216.49  217.68  218.37  218.79  220.45  220.71   220.7  220.93  220.91  221.25
  221.45  222.89  224.49  224.77   224.7   224.6  224.62  224.68   224.6  224.47
  224.41  224.37  224.36  224.63  225.94  226.02  226.08  228.81   228.9  228.96
  229.12  229.65   229.8  229.84  229.79  229.51  229.52   229.4  230.29  231.09
  231.48  232.54  233.83  233.89  234.05  234.68  235.83  236.47  236.99  237.75
  237.87  237.93  238.24  238.27  239.53  241.05  241.54  241.88  242.06   242.6
  242.65  242.75  243.45  243.58  244.15  244.27  244.42  244.77  244.88
                                                                                
                                                                                
                                                                                
                                                                                
                                                                                
                                                                                
                                                                                
                                                                                
                                                                                
                                                                                
                                                                                
                                                                                
                                                                                
                                                                                
                                                                                
                                                                                
                                                                        
       0    8.51   10.66   20.74   29.04   50.31   50.73   51.05   55.51   70.98
   72.17   82.32   84.73   95.11     102   107.4  132.89  168.48  210.26  257.67
  296.32   338.6  363.34  368.98   410.1  434.07  464.34  489.25  507.98  550.19
  569.59  622.79   647.2  650.76  668.87  671.63  681.45  698.75  733.66  741.05
  745.13  752.57  764.19  775.72  776.44  801.31  806.09  815.16  826.62  846.32
  868.53  873.63  881.22  920.79  941.81  959.99  967.63 1098.27 1098.47  1108.3
 1128.42 1129.08 1135.02  1139.2 1140.41 1141.84 1143.68 1150.53 1158.34 1161.59
 1179.38 1183.11 1187.85 1199.19 1394.63 1401.71 1412.66 1421.93 1422.96 1495.11
 1518.71 1540.29 1554.93 1568.65 1572.27 1586.99 1598.91 1621.99 1631.23 1639.02
 1647.51  1669.9 1679.48 1689.66 1696.73 1729.15 1740.65 1748.12 1758.28 1766.26
 1771.57 1782.72 1791.53 1796.28 1814.41 1818.58 1824.42 1830.35 1847.34 1862.81
 1869.99 1900.38 1923.04 2000.45 2005.62 2013.45 2036.36 2047.26 2062.72  2077.8
 2094.58 2100.64 2102.62 2129.36  2156.3 2168.51 2171.09 2212.44 2214.61 2215.87
  2220.6 2243.25 2249.26  2255.7  2263.8 2284.85 2292.09 2296.82 2306.37 2311.56
 2319.82 2334.66 2345.97  2350.3 2355.47  2373.7 2387.61 2397.13 2407.61 2417.56
 2419.41    2421 2435.19 2436.31 2445.79 2464.81 2472.04 2481.45 2493.43 2512.35
 2514.54 2516.68 2530.62 2536.23  2544.1 2547.58 2549.96 2558.14 2565.03
  225.65  225.26  225.12   224.5     224  223.41   223.4   223.4   223.3  222.97
  222.92   222.7  222.31  221.23   220.2  220.21  219.84  217.65  217.02  215.26
  215.03  214.95  214.72  214.57  214.55  213.59  213.15  212.54  212.24  211.39
  211.22  210.01  209.43  209.44  209.21   209.2  209.21  209.28  209.07   209.1
  209.04  209.05  209.17  209.15  209.15  208.99  208.93  208.78  208.74  208.44
   208.2  208.06     208  208.08  208.03  208.31  208.32  208.29  208.29  208.27
  208.59  208.58  208.69  208.74  208.74  208.75  208.77  208.78  208.79  208.75
  208.71   208.7   208.6  208.26  208.36  208.46  208.63  208.77  208.79  208.88
   208.9  208.95  209.17     209  209.01  209.01  209.29  209.25  209.45  209.97
  210.39  211.19   211.4  211.75  212.21  212.42  213.33  214.31  215.39  216.18
  216.49  217.68  218.37  218.79  220.45  220.71   220.7  220.93  220.91  221.25
  221.45  222.89  224.49  224.77   224.7   224.6  224.62  224.68   224.6  224.47
  224.41  224.37  224.36  224.63  225.94  226.02  226.08  228.81   228.9  228.96
  229.12  229.65   229.8  229.84  229.79  229.51  229.52   229.4  230.29  231.09
  231.48  232.54  233.83  233.89  234.05  234.68  235.83  236.47  236.99  237.75
  237.87  237.93  238.24  238.27  239.53  241.05  241.54  241.88  242.06   242.6
  242.65  242.75  243.45  243.58  244.15  244.27  244.42  244.77  244.88
                                                                                
                                                                                
                                                                                
                                                                                
                                                                                
                                                                                
                                                                                
                                                                                
                                                                                
                                                                                
                                                                                
                                                                                
                                                                                
                                                                                
                                                                                
                                                                                
                                                                        
Multiple Barrel Culv=1,7,,30,.27,.7,1,2,2,201,201, 2,Culvert #1  , 0 ,50.19
 1303.69 1303.69 1311.69 1311.69
BC Design=,, 0 ,, 0 ,,,,,,

Type RM Length L Ch R = 1 ,12863.95,45.36,55.51,102.44
XS GIS Cut Line= 6
     1842082.497      390376.576     1840977.751       390049.94
     1840455.157      389982.192     1840202.172      390056.911
     1839749.218      389824.312     1839620.676      389805.949
#Sta/Elev= 30
       0  225.25   90.67  222.51  116.23   220.4  177.86   219.6   291.7  215.37
  392.29  215.32  660.13  209.85  852.94  208.79   934.9   206.9 1010.16  207.06
 1109.12   204.3 1223.66  204.19 1293.49   195.6 1293.65  195.58 1321.89  196.42
 1431.83  199.62 1497.67   198.6  1638.3  201.64 1702.26  208.63 1814.25  212.46
 1870.44  220.51 1901.12  220.83 1945.72   223.5 2141.72   224.4 2243.74  228.33
 2352.92  230.76 2358.21  231.77 2397.04  232.75 2441.38  236.76 2581.81  242.97
#Mann= 0 , 0 , 0
Bank Sta=1293.49,1321.89
Exp/Cntr=.5,.3

Type RM Length L Ch R = 1 ,12808.44,134.06,245.06,104.18
XS GIS Cut Line= 2
     1842125.825       390379.55     1839474.689      389560.417
#Sta/Elev= 30
    14.4  226.61  181.54  220.54  258.46  219.46  358.11  215.53  411.47  215.09
  437.56  215.72  554.36  212.69  670.69  211.62  723.51  210.06  801.92   210.1
    1169  204.42  1260.4  204.13 1339.07  201.24 1348.67  195.13 1365.73  195.22
 1399.02  195.27 1438.92  195.72 1492.82  198.85 1683.58  202.37 1719.98  202.28
 2096.58  212.25 2129.78  212.34 2199.89  215.51 2262.79   216.2 2413.33  222.65
 2500.51  225.65 2509.73  225.36 2569.61   228.3 2677.08  231.94  2789.2  234.24
#Mann= 3 , 0 , 0
    14.4               0 1365.73               0 1399.02               0
Bank Sta=1365.73,1399.02
Exp/Cntr=.5,.3

Type RM Length L Ch R = 3 ,12765.25,,,
BEGIN DESCRIPTION:
NC 144 / SR 1319 (NCDOT # 3)
END DESCRIPTION:
Bridge Culvert--1,0,-1,-1, 0
Deck Dist Width WeirC Skew NumUp NumDn MinLoCord MaxHiCord MaxSubmerge Is_Ogee
23.69,39,2.6,0, 60, 60,204.15,,.95,0,0,0,,
       0   28.17  116.71  136.19  189.52  214.86  234.03  312.99  332.21  374.46
  419.43   434.1  499.15  556.27  600.41  624.13  654.23  701.51  742.78  769.49
  820.72  880.35   918.6 1152.66  1337.2    1340 1406.61    1504  1506.7 1595.72
 1685.67 1731.06 1753.69 1806.16 1862.95 1873.64 1919.15 1932.42 1961.07 2001.71
 2102.27 2181.83  2223.6 2292.21 2336.24 2353.63 2381.62 2399.26 2430.91 2461.35
 2481.25 2554.74 2568.88 2594.71 2620.12 2645.63  2724.5 2733.44 2749.52  2774.8
  225.86  224.31  221.86  220.91  219.72  218.87  218.69  216.95  216.15  215.24
  214.66  214.07  213.14  212.69  211.68   211.6  210.94  210.55  210.77  210.05
  209.21  208.76  207.85  204.98  204.67  204.72  204.95  204.54  204.52  204.15
  204.32  204.92  204.84  205.89  206.51  206.96  207.49  208.24     209  209.52
  212.12  213.84  215.31  217.23   218.9  219.81  220.56  221.64  222.86  223.58
  224.44  226.47  227.19  227.61   229.3  229.56  231.82  232.37  232.76  233.93
                                                                                
                                                                                
                                          202.75  202.75  202.75
                                                                                
                                                                                
                                                                                
       0   28.17  116.71  136.19  189.52  214.86  234.03  312.99  332.21  374.46
  419.43   434.1  499.15  556.27  600.41  624.13  654.23  701.51  742.78  769.49
  820.72  880.35   918.6 1152.66  1337.2    1340 1406.61    1504  1506.7 1595.72
 1685.67 1731.06 1753.69 1806.16 1862.95 1873.64 1919.15 1932.42 1961.07 2001.71
 2102.27 2181.83  2223.6 2292.21 2336.24 2353.63 2381.62 2399.26 2430.91 2461.35
 2481.25 2554.74 2568.88 2594.71 2620.12 2645.63  2724.5 2733.44 2749.52  2774.8
  225.86  224.31  221.86  220.91  219.72  218.87  218.69  216.95  216.15  215.24
  214.66  214.07  213.14  212.69  211.68   211.6  210.94  210.55  210.77  210.05
  209.21  208.76  207.85  204.98  204.67  204.72  204.95  204.54  204.52  204.15
  204.32  204.92  204.84  205.89  206.51  206.96  207.49  208.24     209  209.52
  212.12  213.84  215.31  217.23   218.9  219.81  220.56  221.64  222.86  223.58
  224.44  226.47  227.19  227.61   229.3  229.56  231.82  232.37  232.76  233.93
                                                                                
                                                                                
                                          202.75  202.75  202.75
                                                                                
                                                                                
                                                                                
BR Coef=-1 , 1 , 0 ,, 0 ,,,.8,0,1.2,0,
WSPro=,,,, 1 ,,,, 0 ,,,, 0 ,,,,-1 ,-1 ,-1 , 0 , 0 , 0 , 0 , 0
BC Design=,, 0 ,, 0 ,,,,,,

Type RM Length L Ch R = 1 ,12563.38,521.75,440.42,347.36
XS GIS Cut Line= 2
      1842125.78      390284.821     1839474.644      389465.689
#Sta/Elev= 30
   -14.4  227.44    68.1  222.45  234.33  218.63  337.04  214.21  458.96  212.44
  474.96  211.22  803.18  208.98  921.81  209.09 1078.61  205.19 1262.35  204.88
 1287.09  204.06 1325.72  198.78 1363.17  198.14 1367.45  197.07  1445.3  196.47
 1528.73  196.55 1558.73  197.14 1713.96  198.18 1841.93  201.55 2066.07  212.21
 2107.08  215.04 2149.19  215.04 2182.43  216.73 2248.06  217.26 2308.93  219.14
 2440.65  223.68 2461.94  225.53 2530.31  226.08 2683.35  233.51  2760.4  235.39
#Mann= 3 , 0 , 0
   -14.4               0 1528.73               0 1558.73               0
Bank Sta=1528.73,1558.73
Exp/Cntr=.5,.3

Type RM Length L Ch R = 1 ,12122.96,363.73,470.07,427.76
XS GIS Cut Line= 5
     1841920.437      389559.489      1840700.16      389409.043
     1840177.781      389534.414     1839810.026       389379.79
     1839425.555      389354.716
#Sta/Elev= 30
       0  225.74   41.58  222.77   84.73  217.39   166.8  214.09  222.39  209.71
  368.01  208.91  463.16  209.96  558.11  208.44  752.37  209.46  909.75  208.76
   931.2  205.62 1129.83   204.4  1210.7  201.68 1235.75  197.77 1287.04   197.3
 1300.99   197.5  1331.6  197.49 1620.38  198.85 1652.25  202.48  1684.2  204.15
 1701.81  210.57 1766.73  216.74 1927.58  220.55 1962.68  223.71 2062.83  228.05
 2104.76  231.46 2416.14  235.24 2448.21  235.83 2477.11  238.57 2550.96  239.12
#Mann= 0 , 0 , 0
Bank Sta=1300.99,1331.6
Exp/Cntr=.3,.1

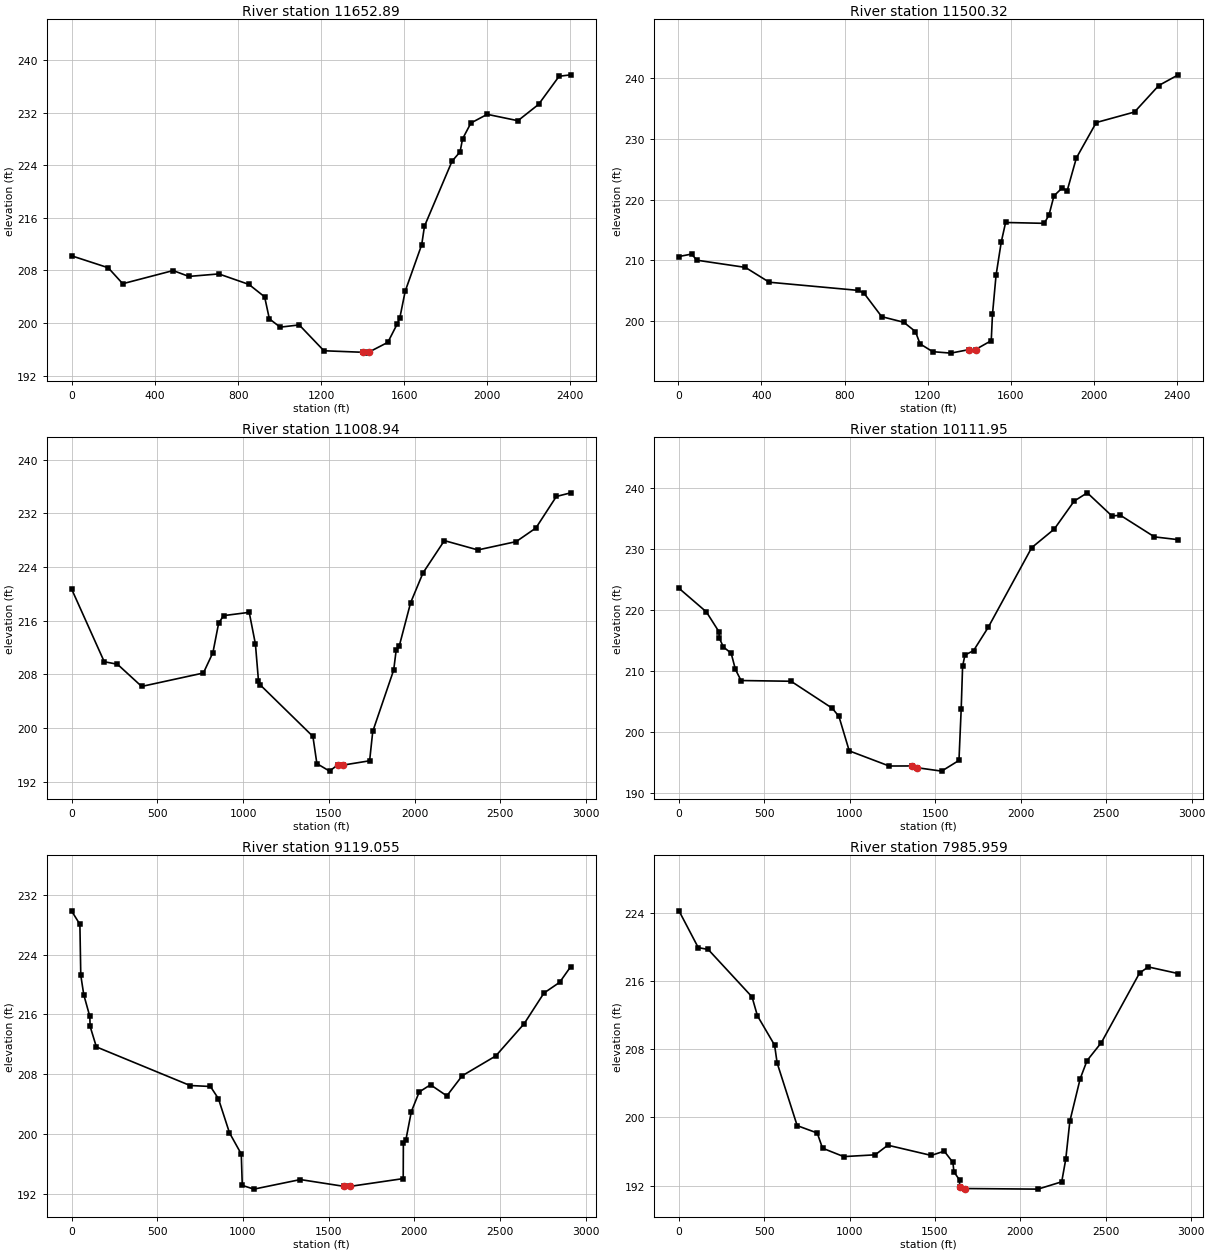
Type RM Length L Ch R = 1 ,11652.89,148.43,152.57,153.89
XS GIS Cut Line= 4
     1841753.926      389237.763     1840439.788      389058.881
     1839789.081      389201.037     1839378.973      389250.005
#Sta/Elev= 30
   -2.55  210.22   174.2   208.4   244.2  205.97  486.82  207.97  562.98  207.08
  707.16  207.46  852.38  205.86  927.83  203.97  950.58  200.63  1002.6  199.36
 1094.52   199.7 1213.42  195.77 1399.76  195.54 1414.86  195.41 1431.03  195.58
 1521.34  197.05 1566.29  199.83 1579.43  200.82 1605.02  204.83 1684.58  211.91
 1697.85  214.72 1830.69  224.61 1869.39  226.03 1881.26     228 1921.58  230.42
 2000.15  231.74 2148.03  230.77  2247.5  233.25 2346.41  237.53 2402.78  237.75
#Mann= 3 , 0 , 0
   -2.55               0 1399.76               0 1431.03               0
Bank Sta=1399.76,1431.03
Exp/Cntr=.3,.1

Type RM Length L Ch R = 1 ,11500.32,434.57,491.38,449.44
XS GIS Cut Line= 4
     1841743.547      389087.259     1840429.409      388908.378
     1839778.702      389050.533     1839368.594      389099.501
#Sta/Elev= 30
    2.55  210.64   63.03  211.04   89.16  210.03  322.41  208.85  437.27  206.41
  864.24  205.07  892.64  204.66  979.17  200.74 1085.36  199.82 1141.65  198.29
 1163.78  196.27  1224.7  194.98 1312.12  194.74 1399.67  195.32 1431.12  195.33
 1506.93  196.79 1512.82  201.12 1530.05  207.55 1555.08  213.02 1576.07  216.24
 1761.88   216.1 1784.75  217.43 1809.04  220.62 1848.95  221.94 1872.11   221.4
 1917.02  226.86 2012.82  232.69 2197.09  234.42  2313.9  238.78 2407.88  240.54
#Mann= 3 , 0 , 0
    2.55               0 1399.67               0 1431.12               0
Bank Sta=1399.67,1431.12
Exp/Cntr=.3,.1

Type RM Length L Ch R = 1 ,11008.94,869.85,896.99,869.46
XS GIS Cut Line= 2
     1842015.469      388499.877     1839105.058      388499.877
#Sta/Elev= 30
       0  220.75  190.88  209.88  267.63  209.51  408.99   206.2  768.76   208.2
  824.27  211.24  857.63  215.62  886.17  216.75 1035.85  217.24 1072.08  212.51
 1089.84  207.05    1100  206.43  1407.2  198.75 1430.35   194.7 1504.23  193.58
 1554.16  194.56 1583.26  194.48 1737.74  195.12 1755.98  199.49 1878.07  208.65
 1892.35  211.57 1909.89  212.16 1976.66  218.67 2048.99  223.12 2173.54  227.93
 2368.81  226.54 2592.04  227.78 2707.06  229.81 2826.37  234.51 2910.41  235.05
#Mann= 0 , 0 , 0
Bank Sta=1554.16,1583.26
Exp/Cntr=.3,.1

Type RM Length L Ch R = 1 ,10111.95,823.64,992.9,906.6
XS GIS Cut Line= 2
     1841981.363      387669.955     1839059.583      387692.692
#Sta/Elev= 30
       0  223.57  160.31  219.69   234.4  216.41  236.26  215.38  259.58  213.93
  305.39   212.9  330.09  210.25  363.12  208.41  655.93  208.29  896.81  203.86
  936.08  202.51  996.36  196.85 1230.13  194.36 1361.19  194.37 1391.32  194.09
 1537.19  193.52  1638.5  195.28 1651.46  203.67 1659.73  210.74 1673.44   212.6
  1723.8  213.32 1809.26  217.13 2064.26  230.25  2196.2   233.3 2312.92  237.91
 2389.45  239.26 2533.55  235.46 2583.25  235.57 2782.49  232.02 2921.87  231.56
#Mann= 0 , 0 , 0
Bank Sta=1361.19,1391.32
Exp/Cntr=.3,.1

Type RM Length L Ch R = 1 ,9119.055,860.68,1133.1,779.41
XS GIS Cut Line= 5
     1842140.526      386783.189     1840742.164       386862.77
     1840344.256       386771.82       1840219.2      386794.558
     1839241.483      386817.295
#Sta/Elev= 30
       0  229.88   48.91  228.07   54.14  221.25   71.65  218.63  106.86  215.73
  108.67   214.4  145.15  211.65  692.03  206.48  810.82  206.35  857.36  204.72
  921.79  200.15  990.79   197.3  996.65   193.1 1064.85   192.6 1335.46  193.88
 1590.71  192.97 1623.59  192.96  1935.9  194.01 1936.72  198.74 1951.71  199.23
 1983.34  202.99  2029.4  205.62 2095.27  206.58 2190.36  205.09 2279.84  207.78
 2475.97  210.44 2641.41  214.75 2757.38  218.87 2848.74   220.3 2913.88  222.42
#Mann= 3 , 0 , 0
       0               0 1590.71               0 1623.59               0
Bank Sta=1590.71,1623.59
Exp/Cntr=.3,.1

Type RM Length L Ch R = 1 ,7985.959,339.1,302.69,253.05
XS GIS Cut Line= 2
     1842129.157      385907.792     1839210.079      386112.116
#Sta/Elev= 30
       0  224.27  112.95  219.95  171.31  219.73  428.19  214.16  459.79  211.94
  560.27   208.5  575.32   206.4  692.71  199.04  810.37  198.17   841.2  196.39
   965.6   195.4 1149.85  195.61 1223.98  196.74 1478.44  195.54 1554.67  196.04
 1605.68  194.71 1611.18  193.62 1644.54  192.64 1644.92  191.81 1677.15  191.65
 2103.81  191.58 2243.14  192.44 2266.88   195.1 2290.77  199.55    2351  204.52
 2391.38  206.67  2475.8   208.8 2699.28  216.96 2750.24  217.68 2926.22   216.9
#Mann= 0 , 0 , 0
Bank Sta=1644.92,1677.15
Exp/Cntr=.3,.1

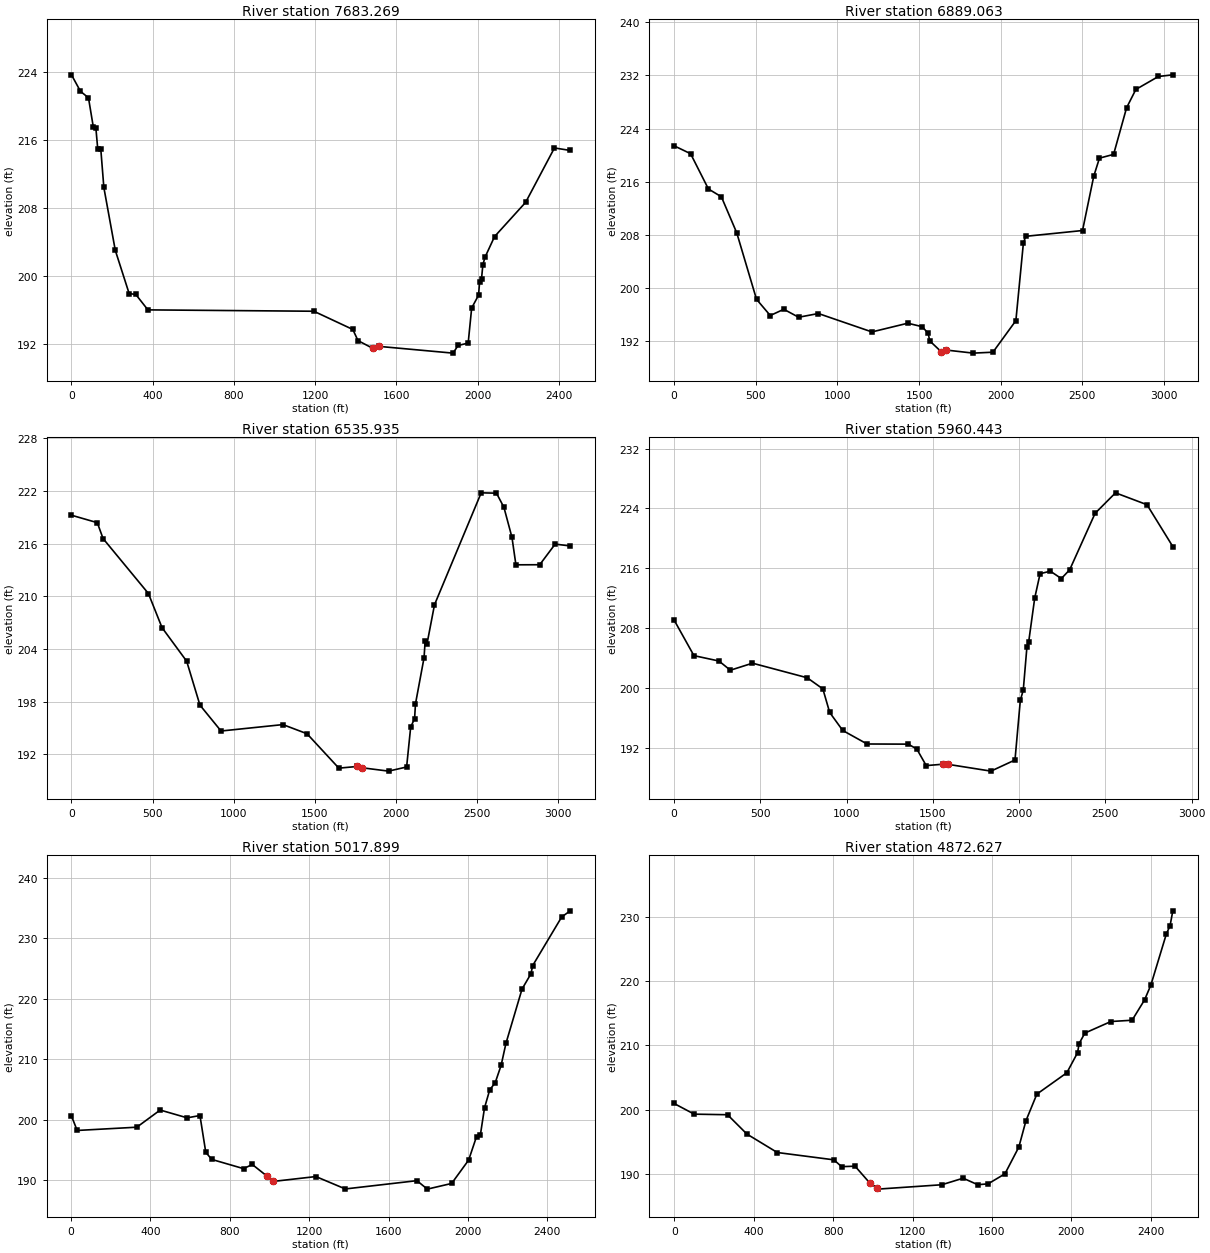
Type RM Length L Ch R = 1 ,7683.269,501.34,794.21,684.96
XS GIS Cut Line= 2
     1841805.166      385477.162     1839393.147      385935.141
#Sta/Elev= 30
       0  223.66   44.35  221.72   83.71  220.96   107.7   217.5  120.21  217.38
   129.5   214.9  144.27  214.95  159.36  210.43  215.62  203.05  283.86  197.97
  316.73  197.86  376.26  196.05 1193.22  195.89 1385.02  193.75 1410.46  192.44
 1482.89  191.54  1514.8  191.76 1878.23  190.97 1903.41  191.87 1952.92  192.15
  1970.1  196.27    2004  197.77 2009.29  199.35 2018.57  199.69 2025.38  201.37
 2035.93  202.24  2082.8  204.66 2235.71  208.68  2377.6  215.07 2455.11  214.78
#Mann= 0 , 0 , 0
Bank Sta=1482.89,1514.8
Exp/Cntr=.3,.1

Type RM Length L Ch R = 1 ,6889.063,354.2,353.13,346.76
XS GIS Cut Line= 2
     1842015.469      385248.402     1838968.632      385032.395
#Sta/Elev= 30
       0   221.4  100.89  220.21  210.22   214.9  289.44  213.73  383.66   208.3
  504.64   198.3  588.95  195.86  671.92   196.8  762.63   195.6  883.64  196.16
 1211.54  193.39 1430.91   194.7 1519.66  194.18  1556.5  193.16 1565.35  192.05
  1637.2  190.38 1667.75  190.66 1832.02   190.2 1952.75  190.34 2093.22  195.09
 2139.31  206.78 2153.74  207.78 2501.45  208.65 2570.37  216.84  2605.1  219.54
 2691.78  220.11 2771.27  227.12 2828.14  229.88 2966.03  231.83 3054.48  232.08
#Mann= 0 , 0 , 0
Bank Sta=1637.2,1667.75
Exp/Cntr=.3,.1

Type RM Length L Ch R = 1 ,6535.935,560.23,575.49,549.27
XS GIS Cut Line= 2
     1842125.751      384897.057     1839057.296      384698.599
#Sta/Elev= 30
       0  219.23  159.18  218.38  194.84  216.57  474.41  210.31  558.43  206.42
  710.28   202.6  792.07   197.6  922.19  194.65 1303.73  195.38 1452.19  194.34
 1648.48  190.42  1761.9  190.61 1792.65  190.46 1955.11  190.08 2066.34  190.55
 2091.55  195.12 2115.48  196.04 2120.89  197.73 2173.81  202.99 2180.56  204.88
 2192.14  204.58 2238.28  209.03 2526.14  221.78 2620.46  221.74 2666.28  220.13
 2715.88  216.71 2740.29  213.58 2887.06  213.59 2982.23  215.94 3074.87  215.73
#Mann= 0 , 0 , 0
Bank Sta=1761.9,1792.65
Exp/Cntr=.3,.1

Type RM Length L Ch R = 1 ,5960.443,850.85,942.54,512.8
XS GIS Cut Line= 3
     1842072.313      384316.161       1840217.5      384225.512
     1839225.222      384515.408
#Sta/Elev= 30
       0  209.06  114.98   204.3  259.91  203.58  326.15  202.35  454.34  203.29
  771.49  201.34  862.19  199.85  901.78   196.7  977.36  194.29 1118.56  192.48
 1356.56  192.46 1406.46  191.82 1461.36  189.59 1561.02  189.78 1589.93  189.75
 1836.55  188.85 1975.91  190.34 2006.86  198.32 2023.92  199.69 2044.96  205.42
  2055.3  206.14 2090.24     212 2121.39  215.26 2180.77   215.6 2244.68  214.61
 2293.04  215.79 2440.29  223.34 2558.65  226.08  2741.1  224.49 2890.79  218.89
#Mann= 0 , 0 , 0
Bank Sta=1561.02,1589.93
Exp/Cntr=.5,.3

Type RM Length L Ch R = 1 ,5017.899,155.01,145.27,168.41
XS GIS Cut Line= 6
     1841857.444      383084.087     1841289.649      383335.674
     1840915.138      383515.418     1840524.971       383682.76
     1840249.348      383791.041     1839562.345      384106.268
#Sta/Elev= 30
    1.88  200.61   30.54  198.22  331.16  198.76  448.89   201.6  584.79  200.31
  649.35  200.69  678.62  194.61   708.6  193.43  869.08   191.9  913.09  192.59
  987.06  190.66 1019.73  189.79 1233.43  190.59 1382.01  188.54 1742.82  189.91
 1795.12  188.51 1917.74  189.45 2003.41  193.32 2043.25  197.22 2062.29  197.43
  2083.3  201.95 2109.67  204.95 2137.14  206.11 2167.11  209.01 2191.49  212.65
 2272.42  221.62 2317.28  224.15  2326.1  225.51 2472.27  233.55 2515.09  234.57
#Mann= 3 , 0 , 0
    1.88               0  987.06               0 1019.73               0
Bank Sta=987.06,1019.73
Exp/Cntr=.5,.3

Type RM Length L Ch R = 1 ,4872.627,209.01,480.58,327.38
XS GIS Cut Line= 6
     1841816.855      382950.325      1841249.06      383201.912
     1840874.548      383381.657     1840484.381      383548.999
     1840208.759      383657.279     1839521.755      383972.506
#Sta/Elev= 30
   -1.88  200.95   99.33  199.29  267.29   199.2  365.08  196.19  518.04  193.32
  803.17  192.18  842.07  191.12  909.95  191.19  985.81  188.52 1020.99  187.79
 1023.86  187.62 1346.77   188.3 1454.62  189.32 1528.28  188.31 1580.19  188.44
 1665.28     190 1735.38  194.17 1771.36  198.28  1826.2  202.41 1977.19  205.73
 2031.23  208.85 2039.16  210.28 2068.09  211.91 2199.37  213.71 2306.07  213.91
 2368.85  217.07 2400.67  219.38 2479.37   227.4 2497.31   228.6 2511.33  230.94
#Mann= 3 , 0 , 0
   -1.88               0  985.81               0 1020.99               0
Bank Sta=985.81,1020.99
Exp/Cntr=.5,.3

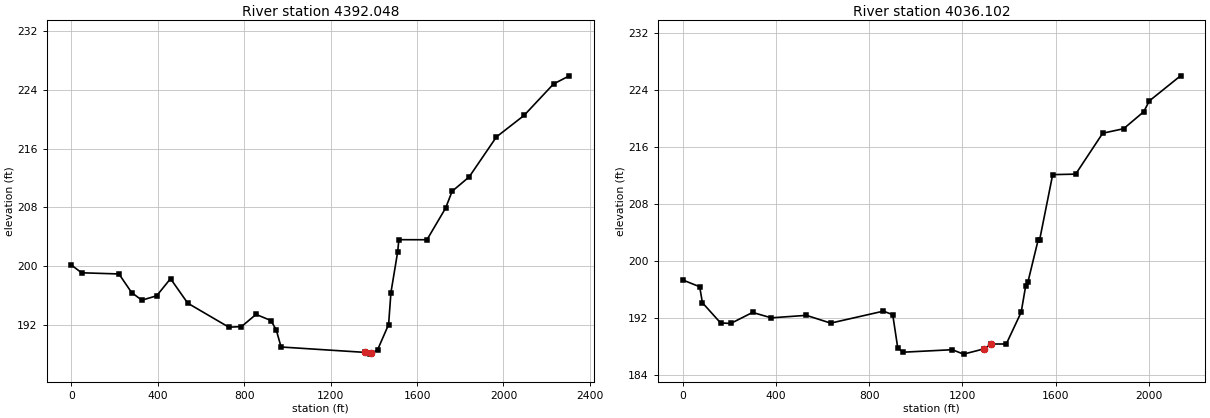
Type RM Length L Ch R = 1 ,4392.048,356.38,355.95,352.7
XS GIS Cut Line= 4
      1841796.01      382892.371     1840362.973      383256.031
     1839879.902      383068.548     1839575.343      383115.291
#Sta/Elev= 30
       0  200.12    47.1  199.07  219.96  198.91   278.8  196.37  325.84  195.34
  394.32  195.93  458.73  198.27  538.44  194.93  728.65  191.66  787.03  191.74
  854.68   193.4  923.29  192.57  948.05   191.3  970.45  188.96  1357.5  188.23
 1380.92  187.99 1387.47  188.08  1417.4  188.59 1468.22  192.02 1479.02  196.38
 1510.32  201.94 1515.78  203.58 1645.77  203.57 1731.91  207.87 1762.36  210.18
 1841.18  212.13 1967.44  217.58 2095.13   220.5 2231.72  224.79 2304.76   225.9
#Mann= 0 , 0 , 0
Bank Sta=1357.5,1387.47
Exp/Cntr=.3,.1

Type RM Length L Ch R = 1 ,4036.102,277.88,382.29,385.9
XS GIS Cut Line= 3
     1841662.788      382557.516     1840028.117      382982.386
     1839581.643      382982.386
#Sta/Elev= 30
       0  197.37    73.1  196.41   84.71  194.17  162.63  191.34  205.99  191.26
  299.99  192.81  380.05  192.05  530.65   192.4  634.98  191.31  861.14  192.99
   901.1  192.49  922.53  187.84  945.61  187.23 1156.42  187.58 1204.72  186.96
 1291.95  187.69 1323.98  188.38 1388.05  188.38 1451.98  192.84 1470.89  196.45
 1480.98  197.08 1525.18  203.03 1530.76  202.92 1587.12  212.14 1685.75  212.21
  1801.7  217.95 1891.39  218.58 1977.61  220.96 2001.63  222.48 2135.46     226
#Mann= 0 , 0 , 0
Bank Sta=1291.95,1323.98
Exp/Cntr=.5,.3