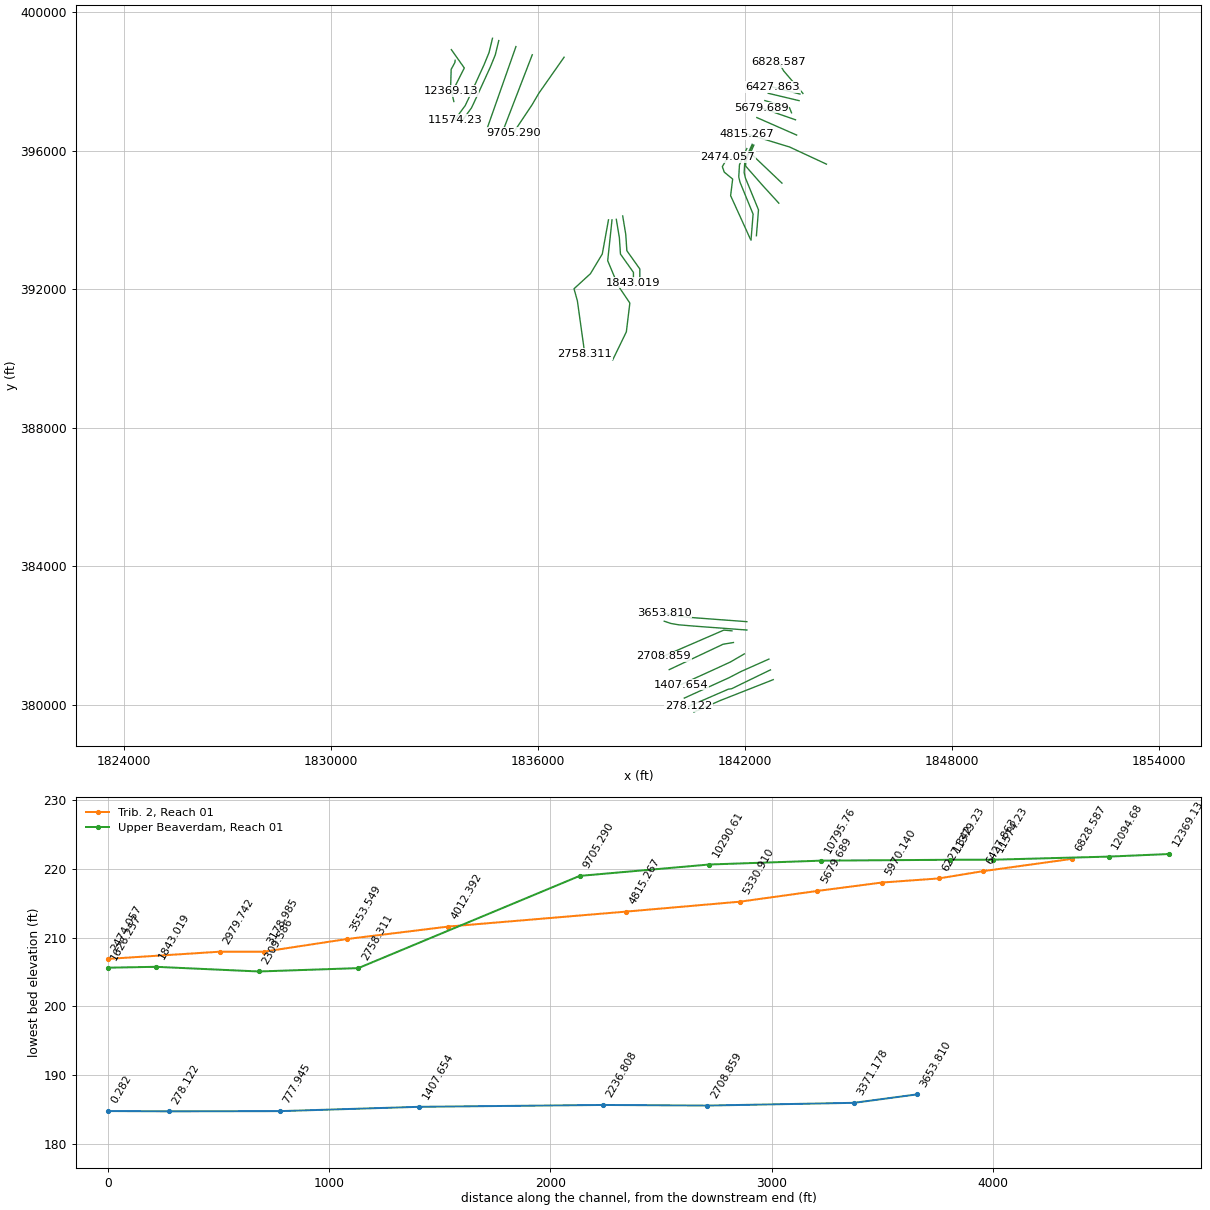
HEC-RAS study gum_limited.prj: Gum Swamp

--- gum_limited.g01 (geometry) --- (continued)

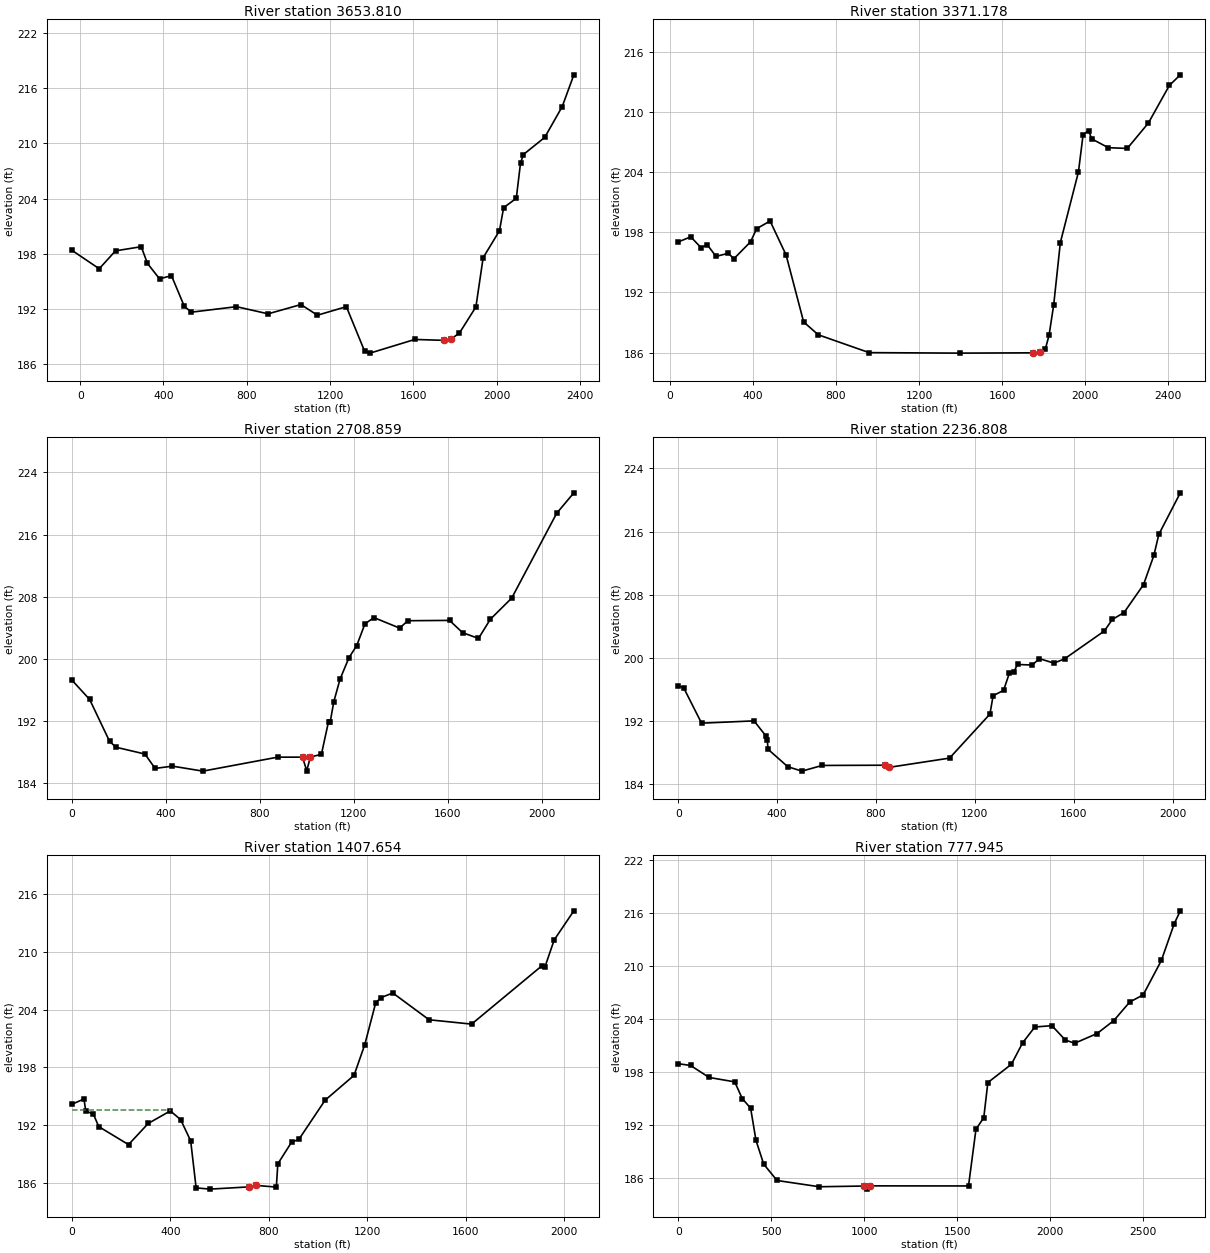
Type RM Length L Ch R = 1 ,3653.810,243.77,282.63,250.97
XS GIS Cut Line= 5
     1842061.406      382399.215     1840539.773      382511.729
     1840088.266      382549.808     1839865.233      382587.887
     1839669.399      382653.165
#Sta/Elev= 30
  -40.54  198.37   91.26  196.35  169.58   198.3  293.13  198.75  322.98  196.93
  381.15  195.25  438.32   195.6  499.97  192.26  533.88  191.62   750.6  192.22
  902.47  191.44  1060.1  192.45 1139.28  191.29 1278.37  192.22 1366.66  187.34
 1391.94  187.16 1607.23  188.65 1748.67  188.55 1780.33  188.68 1821.31  189.34
 1900.61  192.19 1935.32  197.55 2013.77  200.49 2033.73     203 2094.56  204.02
 2115.03  207.88  2128.9  208.79 2231.35  210.66 2315.16  214.01 2371.05  217.47
#Mann= 3 , 0 , 0
  -40.54               0 1748.67               0 1780.33               0
Bank Sta=1748.67,1780.33
Exp/Cntr=.5,.3

Type RM Length L Ch R = 1 ,3371.178,296.18,662.32,619.58
XS GIS Cut Line= 5
     1842061.406      382157.803     1840534.081      382270.738
     1840082.574      382308.817      1839859.54      382346.895
     1839663.706      382412.174
#Sta/Elev= 30
   40.54  197.03  100.78  197.54  150.37  196.46  179.66  196.77  222.32  195.59
  281.95   195.9  308.29  195.35  388.53  197.04  418.07  198.35  482.72  199.12
   559.8  195.73  644.35  189.05  714.67  187.77   959.5  185.99 1396.26  185.94
 1746.27  185.97  1782.7  186.01 1808.46  186.38 1825.87  187.72 1848.26  190.76
 1880.27  196.97 1967.43  204.02 1989.75  207.73 2016.61  208.14  2030.6  207.32
 2111.47  206.43  2202.6  206.36 2304.02  208.89 2405.34  212.65 2457.83   213.7
#Mann= 3 , 0 , 0
   40.54               0 1746.27               0  1782.7               0
Bank Sta=1746.27,1782.7
Exp/Cntr=.5,.3

Type RM Length L Ch R = 1 ,2708.859,378.78,472.05,394.36
XS GIS Cut Line= 4
     1841627.489      382134.232     1841393.576      382155.991
     1840906.499      381946.038     1839646.574      381402.664
#Sta/Elev= 30
       0  197.28   76.11  194.77  160.89  189.38  187.97  188.62  311.49  187.74
   354.8  185.89  428.78  186.18  558.14  185.54   876.6  187.34  982.34  187.34
 1000.17  185.59 1015.94  187.36 1062.74   187.7 1092.96  191.91 1100.45  191.91
 1115.62   194.5 1142.31   197.4 1180.23  200.16 1213.24  201.71 1248.24  204.52
 1286.63  205.31 1395.73  203.96 1430.97  204.91 1608.12  204.95 1663.88  203.37
 1731.49  202.63 1781.98   205.1 1873.06  207.83  2064.2  218.74 2137.43  221.38
#Mann= 0 , 0 , 0
Bank Sta=982.34,1015.94
Exp/Cntr=.3,.1

Type RM Length L Ch R = 1 ,2236.808,588.49,829.15,587.99
XS GIS Cut Line= 3
     1841671.007      381796.961     1841371.816      381748.003
     1839808.116      381013.416
#Sta/Elev= 30
       0  196.45   21.59  196.22    94.3  191.71  306.51     192  355.17  190.07
  360.32  189.63   362.9  188.41  442.99  186.19  500.26  185.63  582.05  186.35
   836.7  186.38  850.91   186.1 1097.46  187.28 1260.75  192.86 1273.61  195.19
 1316.02  195.87 1339.14  198.03 1357.78  198.23 1372.27  199.15 1431.59  199.08
 1461.02  199.89 1519.72  199.32 1562.98  199.87 1723.73   203.4 1755.92  204.86
  1803.2  205.73 1881.98  209.27  1923.8  212.97 1943.86  215.64 2030.82  220.91
#Mann= 0 , 0 , 0
Bank Sta=836.7,850.91
Exp/Cntr=.3,.1

Type RM Length L Ch R = 1 ,1407.654,442.54,629.71,412.68
XS GIS Cut Line= 4
     1841987.557      381468.773     1841583.455      381235.218
     1841037.753      380985.104     1840153.292      380583.877
#Sta/Elev= 30
       0  194.16   49.62  194.72   56.68  193.48   87.86  193.14  109.55  191.85
  230.41  189.98  310.48  192.18  400.14  193.48  442.15  192.57  482.67  190.37
  504.89  185.49  561.19  185.36  717.46  185.59  748.03  185.75   830.5  185.57
   836.4  187.98  892.45  190.24  921.88  190.52 1028.42  194.59 1145.85  197.17
 1189.39  200.35 1233.86   204.7 1255.86  205.25 1303.38  205.72 1450.61  202.94
 1623.19  202.49 1907.88  208.53  1920.3  208.38 1958.46  211.23 2038.24  214.25
#Mann= 0 , 0 , 0
#XS Ineff= 2 , 0
          398.01  193.53
Bank Sta=717.46,748.03
Exp/Cntr=.3,.1

Type RM Length L Ch R = 1 ,777.945 ,329.17,499.82,329.92
XS GIS Cut Line= 4
     1842699.137      381318.255     1841888.601      380959.226
     1841540.451      380779.711     1840245.769      380192.208
#Sta/Elev= 30
       0  198.95   66.28  198.75  165.97  197.39  303.71  196.89  344.35  194.99
  389.25  193.91  418.08  190.26   459.7  187.56  531.34  185.71  758.21     185
   997.8  185.08 1014.73  184.73 1033.07   185.1 1560.98  185.09 1601.07  191.51
 1643.07  192.84 1664.96  196.81 1791.47  198.88 1852.11  201.32 1917.57  203.11
 2009.52  203.26 2081.74  201.63 2131.91  201.27 2252.47  202.37 2342.51  203.84
 2427.89  205.94 2500.16  206.75 2597.98  210.65 2667.42  214.83 2699.95  216.28
#Mann= 0 , 0 , 0
Bank Sta=997.8,1033.07
Exp/Cntr=.3,.1

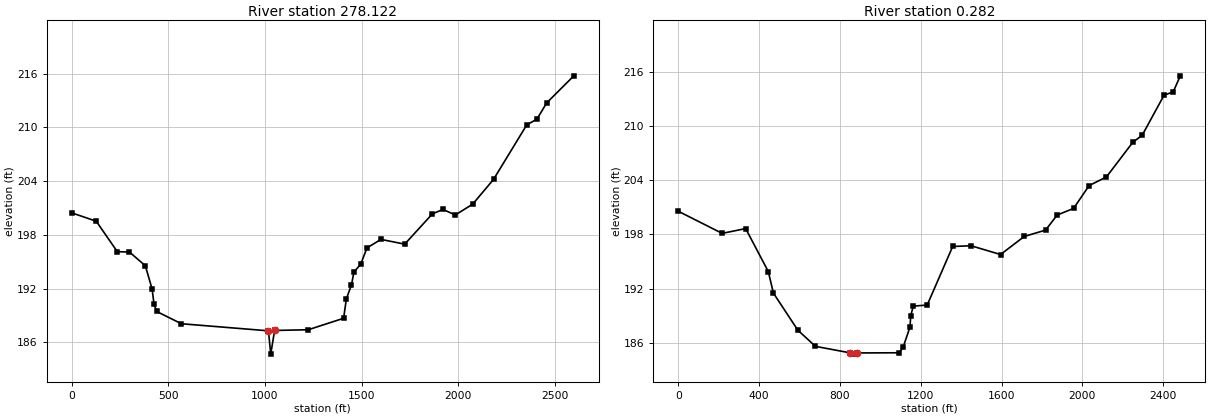
Type RM Length L Ch R = 1 ,278.122 ,238.2,277.84,233.66
XS GIS Cut Line= 5
     1842743.396      381007.045     1842038.207      380666.778
     1841617.561       380462.14     1841526.611      380450.771
      1840373.36      379952.567
#Sta/Elev= 30
       0  200.46  126.56  199.53  235.81  196.13  298.52  196.09  380.86  194.56
  415.95  191.95  425.64  190.27  439.31  189.46  567.41  188.09 1017.91   187.3
 1029.85   184.7 1049.87  187.34  1223.9  187.42 1407.02   188.7 1421.26  190.86
 1447.51  192.42 1460.62  193.87 1495.04  194.71 1527.89  196.55 1600.21   197.5
 1723.28  196.97 1866.49  200.35 1921.04  200.84 1985.26  200.23 2075.04  201.43
 2183.17   204.2 2355.34  210.29 2407.47  210.91  2458.1  212.73 2598.69  215.75
#Mann= 0 , 0 , 0
Bank Sta=1017.91,1049.87
Exp/Cntr=.3,.1

Type RM Length L Ch R = 1 ,0.282   ,.58,.28,.58
XS GIS Cut Line= 3
     1842825.153      380724.961     1841292.869      380124.066
     1840523.934      379789.861
#Sta/Elev= 30
       0  200.55  217.33   198.1  333.67  198.63  445.73  193.87  470.98  191.49
  592.04  187.38   679.1   185.6  848.36  184.89  866.78  184.74  882.43  184.87
 1093.14  184.89  1112.7   185.5 1146.61  187.73 1150.59  189.01 1163.02  190.05
 1231.85  190.17    1358  196.65 1449.08  196.73 1594.82  195.76 1712.11  197.76
 1817.55  198.46  1875.1  200.13 1956.21  200.86 2033.17  203.39 2118.66  204.34
 2249.05  208.17 2295.81  208.96 2403.68  213.38 2449.27  213.76 2484.32  215.53
#Mann= 0 , 0 , 0
Bank Sta=848.36,882.43
Exp/Cntr=.3,.1

River Reach=Trib. 2         ,Reach 01

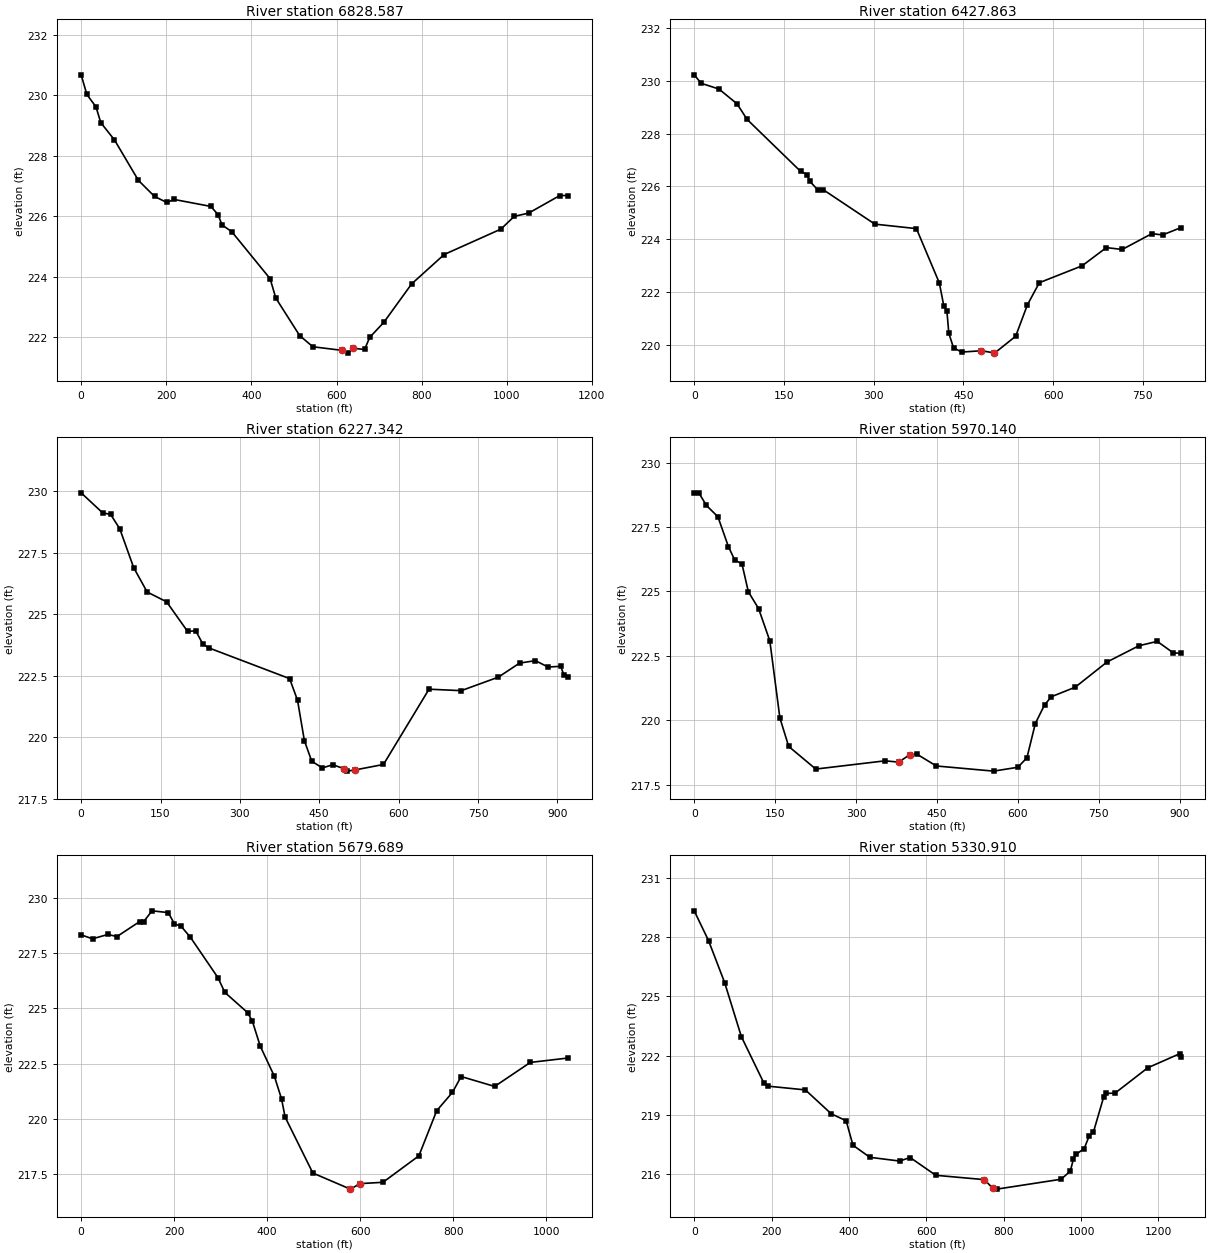
Type RM Length L Ch R = 1 ,6828.587,349.65,400.72,437.1
XS GIS Cut Line= 3
     1843686.682      397651.755     1843129.611      398299.776
     1842981.961      398548.594
#Sta/Elev= 30
       0  230.67   13.44  230.02   34.92  229.61   46.12  229.09   78.25  228.52
  134.56  227.18  172.47  226.65  201.28  226.45  218.39  226.55  304.78  226.32
   321.6  226.05  330.95  225.71  354.18  225.48  444.03  223.93  457.41  223.29
  513.43  222.05  544.48  221.68  613.95  221.56   627.6  221.47  639.43  221.63
  666.01  221.59  677.97  221.99  711.28  222.49  776.65  223.76  852.99  224.73
  986.28  225.57 1017.52  225.99 1051.58   226.1 1124.66  226.68 1143.88  226.68
#Mann= 0 , 0 , 0
Bank Sta=613.95,639.43
Exp/Cntr=.3,.1

Type RM Length L Ch R = 1 ,6427.863,198.88,200.52,201.72
XS GIS Cut Line= 2
     1843599.266      397633.733     1842810.911      397835.875
#Sta/Elev= 30
       0  230.23   11.59  229.91   41.45  229.69   71.62  229.13    88.4  228.54
  177.85  226.57  188.41  226.45  192.96   226.2  206.52  225.87  215.36  225.88
  301.97  224.57  371.45   224.4  409.76  222.34  417.17  221.48  422.33  221.29
  425.64  220.43  433.51  219.88  447.13  219.72  480.18  219.77  501.34  219.69
  502.05  219.68  537.33  220.32  556.98  221.51  576.91  222.35  648.43  222.99
  688.95  223.68  715.48  223.61  765.08  224.21   782.9  224.16  813.86  224.44
#Mann= 0 , 0 , 0
Bank Sta=480.18,501.34
Exp/Cntr=.3,.1

Type RM Length L Ch R = 1 ,6227.342,258.48,257.2,254.04
XS GIS Cut Line= 2
     1843574.035      397443.738     1842678.797      397656.167
#Sta/Elev= 30
       0  229.93   40.42  229.12   55.76  229.05   73.01  228.47    99.3  226.89
  124.77   225.9  161.55   225.5   201.1   224.3  216.67  224.32  229.93  223.79
   241.1  223.63  393.98  222.38  408.96   221.5  421.89  219.86  435.82  219.02
  455.93  218.75  475.52  218.88  496.73  218.72  503.34  218.62  518.01  218.67
  571.37  218.89  657.46  221.95  718.34  221.89  788.52  222.44  828.58  223.01
  858.56  223.11  882.49  222.85  906.29  222.88  912.52  222.52   920.1  222.43
#Mann= 0 , 0 , 0
Bank Sta=496.73,518.01
Exp/Cntr=.3,.1

Type RM Length L Ch R = 1 ,5970.140,280.51,290.45,258.45
XS GIS Cut Line= 3
     1843354.705       397092.93     1843295.192      397240.169
     1842580.348      397446.142
#Sta/Elev= 30
       0  228.83    8.76  228.82   22.65  228.34   43.95   227.9   63.39  226.74
   75.14  226.22   88.54  226.07  100.32  224.99  119.41  224.33   140.2  223.08
  158.81  220.09  175.15  218.98   225.4   218.1   353.8  218.42  379.15  218.37
  399.91  218.66  412.88  218.68  448.92  218.22   555.2  218.02  600.17  218.17
  616.92  218.54  632.51  219.87  649.52  220.59  662.22  220.91  706.49  221.28
  765.51  222.26  824.58  222.89  858.52  223.06  887.92  222.62  902.74  222.59
#Mann= 0 , 0 , 0
Bank Sta=379.15,399.91
Exp/Cntr=.3,.1

Type RM Length L Ch R = 1 ,5679.689,353.02,348.78,343.01
XS GIS Cut Line= 2
     1843470.206      396890.923     1842480.653      397233.461
#Sta/Elev= 30
       0  228.34   24.45  228.16   57.88  228.36   76.86  228.26  125.74  228.94
  134.18  228.93  152.44  229.43  187.33  229.35   200.7  228.84  214.96  228.73
  235.02  228.23  294.18   226.4  309.01  225.73  358.03  224.81  368.19  224.43
  385.23  223.29  415.66  221.92  431.13  220.89  438.72  220.07  498.38  217.53
  579.08   216.8  600.02  217.05   649.2  217.11   726.4  218.31  764.81  220.36
  798.63  221.19  817.37  221.91  889.44  221.46  966.11  222.55 1047.16  222.75
#Mann= 0 , 0 , 0
Bank Sta=579.08,600.02
Exp/Cntr=.3,.1

Type RM Length L Ch R = 1 ,5330.910,492.62,515.64,508.7
XS GIS Cut Line= 2
     1843503.057      396450.043     1842349.911      396954.544
#Sta/Elev= 30
       0  229.32   37.11  227.81   78.65  225.69  121.98  222.95  180.25   220.6
  190.38  220.45  287.34  220.26  354.33  219.05  392.78   218.7  410.46  217.46
  454.15  216.85  531.12  216.66  558.16  216.84  624.55  215.94  750.17  215.72
  771.57  215.29  782.52  215.24  948.48  215.74  972.33  216.15  980.16  216.75
  987.35     217 1008.16  217.29 1020.95  217.92 1031.83  218.11 1058.27  219.88
 1065.71  220.09 1087.46  220.09 1172.71  221.38 1256.27   222.1 1258.68  221.94
#Mann= 0 , 0 , 0
Bank Sta=750.17,771.57
Exp/Cntr=.3,.1

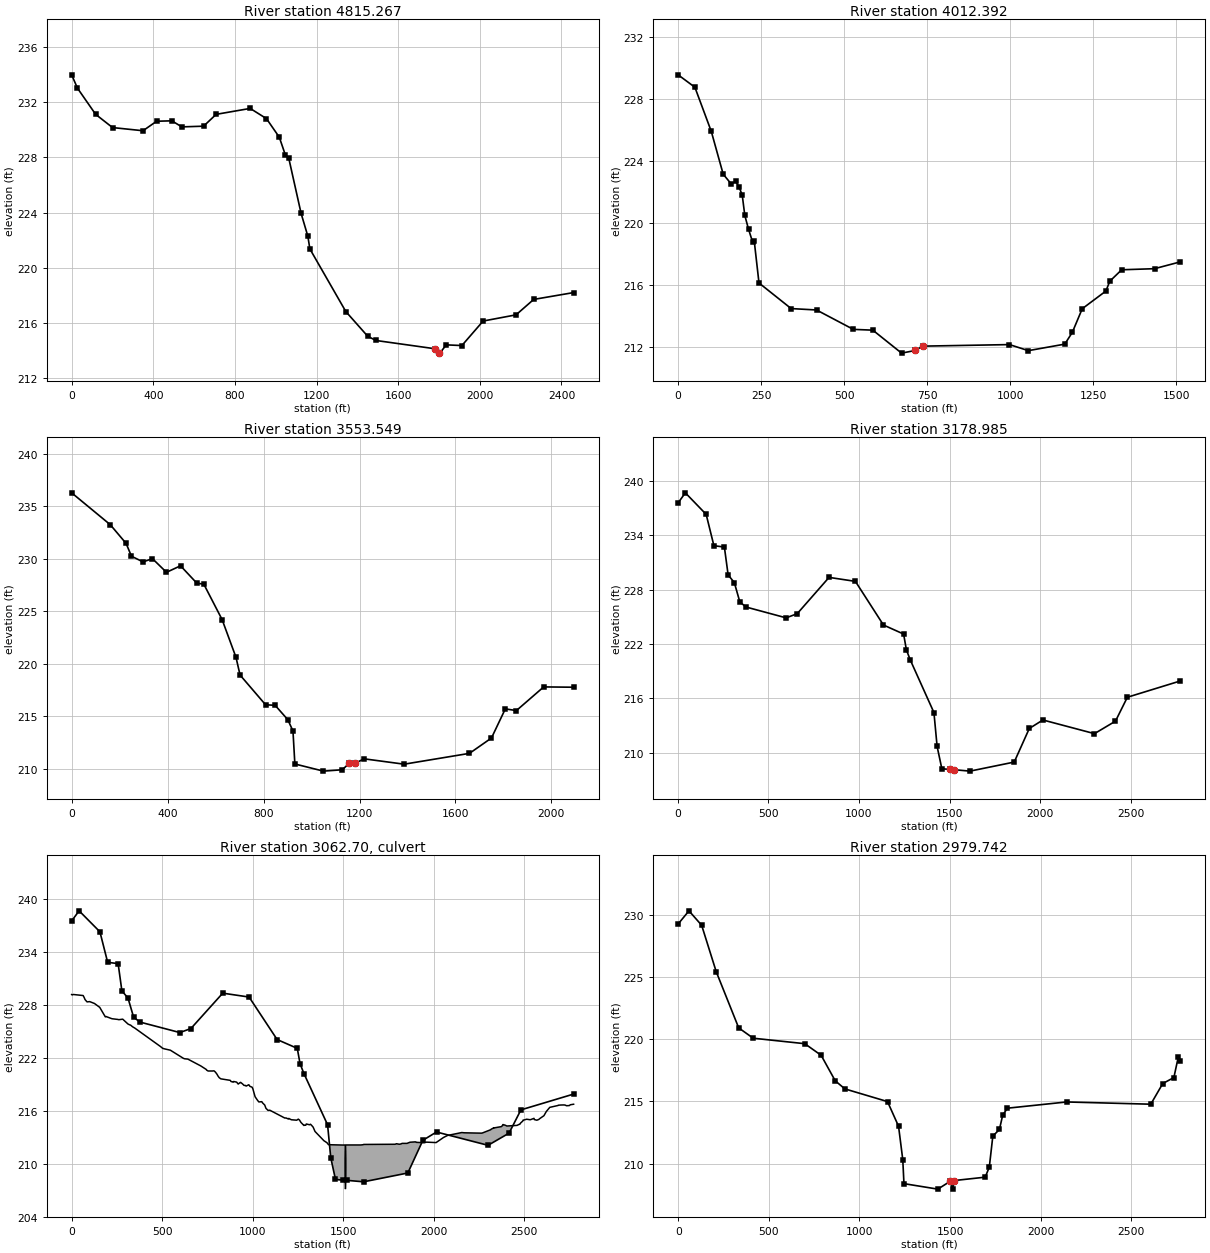
Type RM Length L Ch R = 1 ,4815.267,810.22,802.88,694.97
XS GIS Cut Line= 3
     1844367.135      395610.443     1843300.468      396104.605
     1842071.088       396478.24
#Sta/Elev= 30
       0     234   28.47  233.03  117.57  231.13  200.35  230.17  349.56  229.94
  416.41  230.63  491.22  230.66   539.6  230.22  646.29  230.27  707.97  231.13
  874.72  231.56   954.4  230.82 1017.36  229.47 1047.06  228.18 1063.54  227.96
 1124.17  223.94  1157.4  222.27 1167.07  221.36 1343.28  216.81 1450.25  215.02
  1490.4  214.71 1778.93  214.11 1801.07  213.81 1804.09  213.79  1835.3  214.39
 1911.89  214.34 2016.03  216.12 2177.37  216.57 2263.84  217.69 2460.48  218.19
#Mann= 0 , 0 , 0
Bank Sta=1778.93,1801.07
Exp/Cntr=.3,.1

Type RM Length L Ch R = 1 ,4012.392,428.36,458.84,386.07
XS GIS Cut Line= 3
     1843077.492      395062.043     1842161.484      395929.841
     1842263.932      396158.843
#Sta/Elev= 30
       0  229.54    50.5  228.74   99.98  225.89  135.74  223.14  159.89  222.51
  172.93  222.67  183.44  222.33   193.2  221.78  200.89  220.48  212.03   219.6
  224.29  218.77  229.42  218.81  243.59  216.13  340.48  214.48  416.98  214.39
  527.77  213.14  586.52  213.09  673.08  211.61  713.98  211.78  736.67  212.06
  998.15  212.16 1055.01  211.77 1164.71  212.19 1187.44  212.95 1217.26  214.47
 1288.54  215.61 1300.21  216.24 1336.01  216.98 1434.95  217.05 1512.68  217.49
#Mann= 0 , 0 , 0
Bank Sta=713.98,736.67
Exp/Cntr=.3,.1

Type RM Length L Ch R = 1 ,3553.549,343.51,374.56,262.37
XS GIS Cut Line= 6
     1842987.096      394483.512      1842517.04      394995.753
     1842022.877      395556.206     1842028.904      395676.733
     1842095.194      395875.603       1842233.8      396164.869
#Sta/Elev= 30
       0  236.26  160.96  233.23  226.91  231.45  249.38  230.23   297.5  229.69
  336.81     230  395.33   228.7  453.93  229.32  521.67  227.67  551.01  227.57
  627.28   224.2  685.16  220.61  702.03  218.93  808.42   216.1  848.21  216.05
   900.9  214.69  922.61  213.61  930.51  210.47 1049.55  209.79 1128.59  209.92
  1157.7  210.56 1180.73  210.53 1219.21  210.96 1386.16  210.45 1658.44  211.48
 1750.09  212.94 1807.87  215.71  1854.1  215.55 1967.85   217.8 2093.49  217.77
#Mann= 0 , 0 , 0
Bank Sta=1157.7,1180.73
Exp/Cntr=.5,.3

Type RM Length L Ch R = 1 ,3178.985,222.91,199.24,272.7
XS GIS Cut Line= 6
     1842336.959      393543.151     1842397.223      394290.421
     1842017.562      395212.455     1841981.403      395363.114
     1842001.749      395716.612     1842214.423      396182.701
#Sta/Elev= 30
    1.29  237.58   41.19  238.69  156.16  236.31  198.86  232.85  256.74   232.7
  277.43  229.62   311.5  228.78  341.88  226.65  375.49  226.08   597.7  224.88
  658.82  225.34  834.57  229.35  980.06  228.91  1134.9  224.09 1246.24  223.09
 1261.65  221.34 1283.01  220.23 1413.62  214.42 1431.14  210.68 1457.23  208.22
 1501.24  208.13 1523.42  208.11 1612.59  207.95 1856.89  208.95 1940.07  212.66
 2015.25   213.6 2299.93  212.09 2415.93  213.47 2481.46  216.11 2773.83  217.91
#Mann= 3 , 0 , 0
    1.29               0 1501.24               0 1523.42               0
Bank Sta=1501.24,1523.42
Exp/Cntr=.5,.3

Type RM Length L Ch R = 2 ,3062.70 ,,,
BEGIN DESCRIPTION:
SR 1337 (NCDOT 82 2047)
END DESCRIPTION:
Bridge Culvert--1,0,-1,-1, 0
Deck Dist Width WeirC Skew NumUp NumDn MinLoCord MaxHiCord MaxSubmerge Is_Ogee
103.29,26,2.6,0,171,171,212.12,,.95,0,0,0,,
       0     2.9    9.33   63.57   69.32   74.04   84.98   99.78  125.99  155.09
  186.01  189.97  222.51   255.1  260.65  280.83  282.12  301.02  311.13  319.01
  325.86  336.32  348.72  491.04  503.43  506.57   508.8  545.26  617.07   623.1
  641.81  712.39  712.74  712.89  743.86  745.48  751.09  753.75  778.13  786.16
  793.85  802.62  809.01  815.26  824.14  876.06  880.35  892.23  894.85  911.14
  919.85  928.31  929.41   933.3  941.29  943.65  952.45  958.65  963.54  978.55
  984.69  997.02 1001.32  1013.2 1026.53 1033.98 1048.36 1050.27 1054.12  1066.4
 1073.11 1084.68 1094.66  1176.7 1184.46 1196.34  1199.7 1202.57 1213.48 1236.15
 1243.02 1251.75 1258.63 1266.43 1281.66 1282.89 1283.25 1284.61 1293.09    1296
 1314.25 1319.09  1324.7 1333.91 1344.24 1393.45 1409.87 1418.84 1486.62 1499.95
 1522.13 1597.69    1610 1613.13 1777.81 1786.51 1794.31 1809.79 1819.13 1825.15
 1852.22 1868.52 1897.71 1901.58 1903.35  1947.6 1959.67 2012.97 2054.03 2073.63
 2076.27 2155.02 2165.66 2168.46 2263.34 2268.71 2311.86 2314.63 2316.68 2329.18
 2330.83 2331.68 2373.36 2379.61 2381.69  2383.8 2396.37 2403.78 2448.98 2459.91
 2471.99 2475.13 2479.88 2492.11 2493.74 2495.75 2513.65 2531.26 2532.48 2535.98
 2553.79 2555.51 2569.41 2579.88  2586.9 2607.12 2608.62 2621.63 2641.03 2642.77
  2645.9 2685.59  2687.1 2688.13 2700.81 2716.92 2724.72 2733.59 2748.96 2754.41
 2772.55
  229.19  229.15   229.2  229.08  228.85  228.62  228.36  228.39  228.18  227.74
  226.66   226.7  226.45  226.37  226.34   226.4   226.4  226.05  225.85  225.77
  225.72  225.54  225.39  223.29  223.08  223.08  223.05  222.88  221.96  221.91
  221.87   221.1   221.1   221.1  220.69  220.62  220.56  220.52  220.52  220.54
   220.4  220.16  219.93  219.76  219.63  219.46  219.33  219.26  219.33  219.26
  219.04  219.17  219.19  219.23   219.1  219.06  218.88  218.89  218.81  218.96
  218.78  218.68  218.47   217.6   217.2  217.01  217.03  217.04  216.91  216.66
  216.29  216.05  216.07  215.19  215.19  215.08  215.14   215.1  214.99  214.95
  214.94  215.06  214.95  214.69  214.35  214.34  214.35  214.37  214.37  214.51
  214.42  214.48  214.37  214.15  213.66  212.61  212.39  212.16  212.13  212.12
  212.13  212.13  212.16  212.19  212.22  212.21  212.27  212.21  212.25  212.31
  212.31  212.44  212.48  212.47  212.43  212.38  212.45   212.4  212.98  213.19
  213.21  213.54  213.52  213.51  213.47  213.49  213.85  213.86  213.91  214.05
  214.01  214.06  214.21  214.33  214.44  214.44  214.36  214.28  214.34  214.35
  214.47  214.47  214.62  214.85  214.95  214.95  215.05     215  214.99  215.01
  215.15  215.01  214.94  215.02  215.14  215.42  215.45  215.92   216.4  216.41
  216.42  216.61  216.61  216.64  216.66  216.67  216.66  216.58   216.6  216.69
  216.75
                                                                                
                                                                                
                                                                                
                                                                                
                                                                                
                                                                                
                                                                                
                                                                                
                                                                                
                                                                                
                                                                                
                                                                                
                                                                                
                                                                                
                                                                                
                                                                                
                                                                                
        
       0     2.9    9.33   63.57   69.32   74.04   84.98   99.78  125.99  155.09
  186.01  189.97  222.51   255.1  260.65  280.83  282.12  301.02  311.13  319.01
  325.86  336.32  348.72  491.04  503.43  506.57   508.8  545.26  617.07   623.1
  641.81  712.39  712.74  712.89  743.86  745.48  751.09  753.75  778.13  786.16
  793.85  802.62  809.01  815.26  824.14  876.06  880.35  892.23  894.85  911.14
  919.85  928.31  929.41   933.3  941.29  943.65  952.45  958.65  963.54  978.55
  984.69  997.02 1001.32  1013.2 1026.53 1033.98 1048.36 1050.27 1054.12  1066.4
 1073.11 1084.68 1094.66  1176.7 1184.46 1196.34  1199.7 1202.57 1213.48 1236.15
 1243.02 1251.75 1258.63 1266.43 1281.66 1282.89 1283.25 1284.61 1293.09    1296
 1314.25 1319.09  1324.7 1333.91 1344.24 1393.45 1409.87 1418.84 1486.62 1499.95
 1522.13 1597.69    1610 1613.13 1777.81 1786.51 1794.31 1809.79 1819.13 1825.15
 1852.22 1868.52 1897.71 1901.58 1903.35  1947.6 1959.67 2012.97 2054.03 2073.63
 2076.27 2155.02 2165.66 2168.46 2263.34 2268.71 2311.86 2314.63 2316.68 2329.18
 2330.83 2331.68 2373.36 2379.61 2381.69  2383.8 2396.37 2403.78 2448.98 2459.91
 2471.99 2475.13 2479.88 2492.11 2493.74 2495.75 2513.65 2531.26 2532.48 2535.98
 2553.79 2555.51 2569.41 2579.88  2586.9 2607.12 2608.62 2621.63 2641.03 2642.77
  2645.9 2685.59  2687.1 2688.13 2700.81 2716.92 2724.72 2733.59 2748.96 2754.41
 2772.55
  229.19  229.15   229.2  229.08  228.85  228.62  228.36  228.39  228.18  227.74
  226.66   226.7  226.45  226.37  226.34   226.4   226.4  226.05  225.85  225.77
  225.72  225.54  225.39  223.29  223.08  223.08  223.05  222.88  221.96  221.91
  221.87   221.1   221.1   221.1  220.69  220.62  220.56  220.52  220.52  220.54
   220.4  220.16  219.93  219.76  219.63  219.46  219.33  219.26  219.33  219.26
  219.04  219.17  219.19  219.23   219.1  219.06  218.88  218.89  218.81  218.96
  218.78  218.68  218.47   217.6   217.2  217.01  217.03  217.04  216.91  216.66
  216.29  216.05  216.07  215.19  215.19  215.08  215.14   215.1  214.99  214.95
  214.94  215.06  214.95  214.69  214.35  214.34  214.35  214.37  214.37  214.51
  214.42  214.48  214.37  214.15  213.66  212.61  212.39  212.16  212.13  212.12
  212.13  212.13  212.16  212.19  212.22  212.21  212.27  212.21  212.25  212.31
  212.31  212.44  212.48  212.47  212.43  212.38  212.45   212.4  212.98  213.19
  213.21  213.54  213.52  213.51  213.47  213.49  213.85  213.86  213.91  214.05
  214.01  214.06  214.21  214.33  214.44  214.44  214.36  214.28  214.34  214.35
  214.47  214.47  214.62  214.85  214.95  214.95  215.05     215  214.99  215.01
  215.15  215.01  214.94  215.02  215.14  215.42  215.45  215.92   216.4  216.41
  216.42  216.61  216.61  216.64  216.66  216.67  216.66  216.58   216.6  216.69
  216.75
                                                                                
                                                                                
                                                                                
                                                                                
                                                                                
                                                                                
                                                                                
                                                                                
                                                                                
                                                                                
                                                                                
                                                                                
                                                                                
                                                                                
                                                                                
                                                                                
                                                                                
        
Culvert=1,5,,26,.027,.7,1,2,1,207.12,1512.33,207.12,1512.33,Culvert #1  , 0 ,103.29
BC Design=,, 0 ,, 0 ,,,,,,

Type RM Length L Ch R = 1 ,2979.742,581.39,505.68,344.31
XS GIS Cut Line= 6
     1842180.583      393419.409     1842240.846      394166.679
     1841861.185      395088.714     1841825.027      395239.373
     1841845.372      395592.871     1842058.046      396058.959
#Sta/Elev= 30
   -1.29  229.24   58.61   230.3  128.65  229.14  209.12  225.41   333.2   220.9
  413.21  220.07  697.99  219.63  788.22   218.7  866.11  216.65  919.29     216
 1154.78  214.98 1215.71     213    1239  210.32 1245.56  208.39 1432.59  207.95
 1501.03  208.58 1514.23  207.96 1523.61  208.64 1694.11  208.91 1716.74  209.72
 1736.22  212.21 1772.53  212.74 1790.88   213.9  1816.9  214.45 2143.54  214.95
  2608.3  214.77 2674.36  216.43 2735.74  216.91 2760.67   218.6 2771.25  218.25
#Mann= 3 , 0 , 0
   -1.29               0 1501.03               0 1523.61               0
Bank Sta=1501.03,1523.61
Exp/Cntr=.5,.3

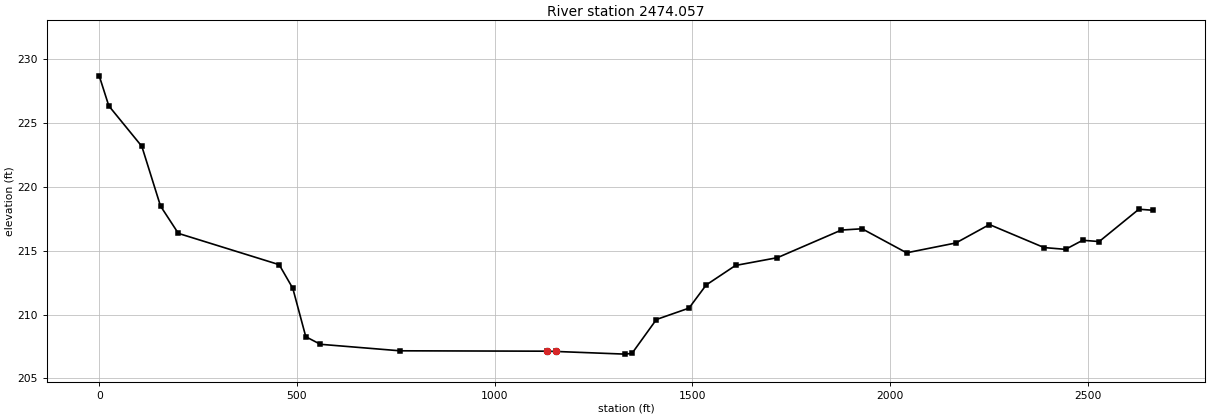
Type RM Length L Ch R = 1 ,2474.057,1574.89,2474.06,715.79
XS GIS Cut Line= 6
     1842161.484      393446.976     1841588.979      394700.461
     1841648.217      395178.818     1841404.643      395379.704
     1841348.756      395538.419     1841510.636       395815.34
#Sta/Elev= 30
       0  228.68   24.23  226.33   107.8  223.16  155.05  218.49  200.14  216.35
   455.2   213.9  489.65  212.05  522.51  208.26  559.46  207.67   760.8  207.16
 1131.92  207.13 1154.38  207.11 1330.01   206.9 1347.64  206.96 1409.34  209.61
 1491.76   210.5 1535.23  212.31 1609.47  213.84 1715.55  214.45 1877.21  216.61
 1929.61  216.71  2042.2  214.83 2166.88   215.6 2251.71  217.04  2389.9  215.24
 2444.19   215.1 2487.55  215.81 2529.31  215.71 2629.73  218.24 2664.81  218.16
#Mann= 0 , 0 , 0
Bank Sta=1131.92,1154.38
Exp/Cntr=.3,.1

River Reach=Upper Beaverdam ,Reach 01

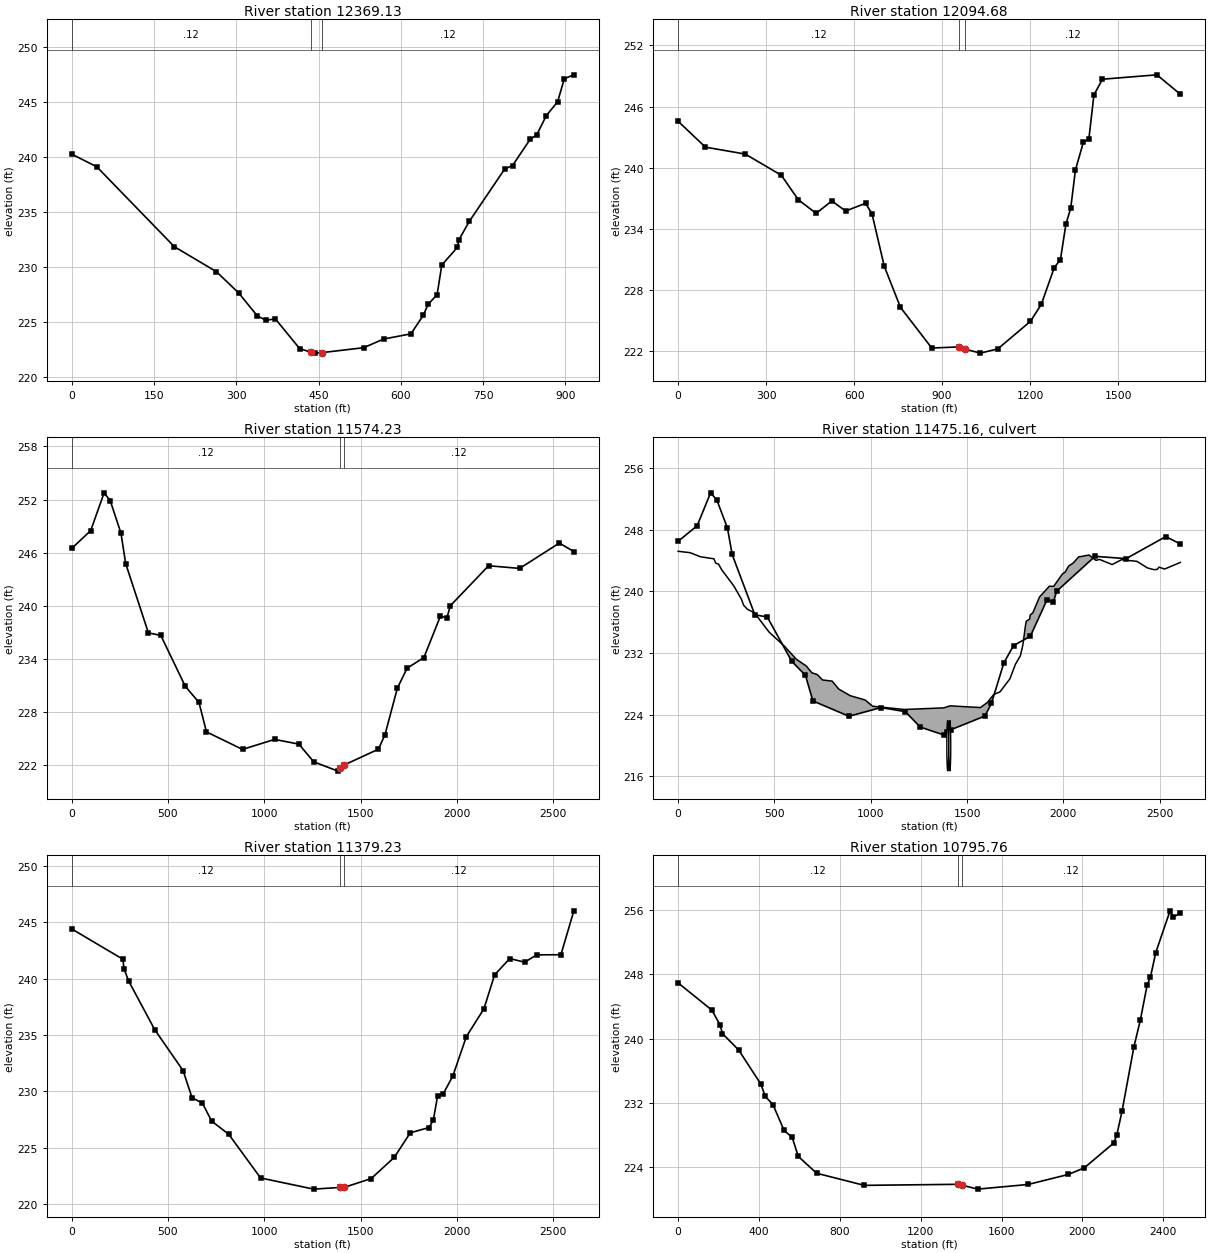
Type RM Length L Ch R = 1 ,12369.13,322.48,274.45,218.99
XS GIS Cut Line= 5
     1833601.627      398608.562     1833591.985      398541.067
     1833485.921      398348.223     1833471.457      397875.756
     1833476.279      397721.481
#Sta/Elev= 30
       0  240.25   45.83   239.1  187.04  231.85     264  229.57  304.26  227.65
  338.65  225.55  354.34  225.16  371.12   225.3  415.54  222.59  435.69  222.27
  443.14  222.18  456.74  222.23     532  222.67  568.65  223.46  618.33  223.93
  641.06  225.62  649.47   226.6  666.11  227.49  674.63  230.18  703.23  231.79
   705.6  232.45  724.99  234.16  789.42  238.91  803.54  239.21  835.48  241.58
  847.68     242   865.1  243.74  885.79  245.01  897.94   247.1  915.31  247.45
#Mann= 3 , 0 , 0
       0     .12       0  435.69    .055       0  456.74     .12       0
Bank Sta=435.69,456.74
Exp/Cntr=.3,.1

Type RM Length L Ch R = 1 ,12094.68,490.89,520.45,501.31
XS GIS Cut Line= 4
     1833490.742      398917.112     1833866.787      398386.792
     1833505.205       397673.27     1833563.058      397417.751
#Sta/Elev= 30
       0  244.56   93.12  242.02  228.98  241.34  351.87  239.26  409.99  236.85
  470.53  235.52  524.09  236.74   571.2  235.75  638.91  236.51  660.92  235.48
  702.65  230.34  758.02  226.29  864.77   222.3  957.01  222.41  977.56   222.2
  1030.3   221.8 1090.05  222.22 1201.03  224.92 1238.04  226.58 1282.28  230.19
 1303.39  230.99  1322.2  234.48 1338.38  236.02  1354.6   239.8 1381.97  242.54
 1400.22   242.8 1417.51  247.15 1446.74  248.69 1632.09  249.12 1712.01  247.22
#Mann= 3 , 0 , 0
       0     .12       0  957.01    .055       0  977.56     .12       0
Bank Sta=957.01,977.56
Exp/Cntr=.5,.3

Type RM Length L Ch R = 1 ,11574.23,195.99,195.01,198.9
XS GIS Cut Line= 6
     1834684.289        399244.7     1834583.046      398830.085
     1834438.413      398478.145     1834052.725      397639.275
     1833893.629      397301.798     1833594.721      396896.826
#Sta/Elev= 30
    -.08  246.48   98.69  248.49  168.48  252.76  200.42  251.86  256.02   248.2
  280.39  244.78  398.31  236.95  462.64  236.67  589.65  230.93  660.95   229.1
  699.81  225.78  887.15   223.8 1053.05  224.93 1179.41   224.4 1256.69   222.4
 1382.48  221.35 1394.67  221.72 1415.53  222.05 1592.62  223.83  1626.8  225.48
 1690.93  230.72 1741.46  232.97 1828.52  234.17    1914  238.83  1948.4  238.66
 1965.49  240.01 2164.35  244.53  2325.5  244.23 2531.73  247.09 2606.94  246.13
#Mann= 3 , 0 , 0
    -.08     .12       0 1394.67    .055       0 1415.53     .12       0
Bank Sta=1394.67,1415.53
Exp/Cntr=.5,.3

Type RM Length L Ch R = 2 ,11475.16,,,
BEGIN DESCRIPTION:
SR 1001 (NCDOT # 99)
END DESCRIPTION:
Bridge Culvert--1,0,-1,-1, 0
Deck Dist Width WeirC Skew NumUp NumDn MinLoCord MaxHiCord MaxSubmerge Is_Ogee
79.07,40,2.6,0, 60, 60,224.68,,.95,0,0,0,,
       0   62.73  116.06  185.78  195.07  209.92  226.14  289.04   328.2  340.11
  360.23  396.02  472.55  551.15  614.26     665  694.54  721.57  750.06  799.47
  834.24  893.11  970.97 1009.54 1174.69 1378.44 1412.52 1569.37 1605.16 1638.71
 1671.11 1722.32 1751.42 1776.76  1789.6 1803.32 1807.17 1824.47 1827.94 1841.53
 1876.48 1927.53 1949.65 1994.08 2010.51 2026.94 2050.44 2079.16 2133.25 2169.25
 2187.73 2253.52 2301.53 2381.99 2436.07 2470.27 2487.37 2496.36 2525.43 2607.02
  245.18     245  244.47  244.21  243.64  243.52  242.79  240.69  238.99  238.18
  237.66  237.21   234.7   232.9  231.18  230.32  229.43  229.22   228.5  228.36
  227.32  226.47  225.91   225.1  224.68  224.89  225.15  224.93  225.58  226.63
  226.97  228.65  230.56  231.64  233.03  235.59  236.12  236.39  236.93  237.21
  239.28  240.66  240.64  242.21  242.53  243.26  243.65  244.45   244.7  244.01
  244.13  243.46  244.09  243.88  243.03   242.8  242.84  243.13  242.88  243.74
                                                                                
                                                                                
                                                                                
                                                                                
                                                                                
                                                                                
       0   62.73  116.06  185.78  195.07  209.92  226.14  289.04   328.2  340.11
  360.23  396.02  472.55  551.15  614.26     665  694.54  721.57  750.06  799.47
  834.24  893.11  970.97 1009.54 1174.69 1378.44 1412.52 1569.37 1605.16 1638.71
 1671.11 1722.32 1751.42 1776.76  1789.6 1803.32 1807.17 1824.47 1827.94 1841.53
 1876.48 1927.53 1949.65 1994.08 2010.51 2026.94 2050.44 2079.16 2133.25 2169.25
 2187.73 2253.52 2301.53 2381.99 2436.07 2470.27 2487.37 2496.36 2525.43 2607.02
  245.18     245  244.47  244.21  243.64  243.52  242.79  240.69  238.99  238.18
  237.66  237.21   234.7   232.9  231.18  230.32  229.43  229.22   228.5  228.36
  227.32  226.47  225.91   225.1  224.68  224.89  225.15  224.93  225.58  226.63
  226.97  228.65  230.56  231.64  233.03  235.59  236.12  236.39  236.93  237.21
  239.28  240.66  240.64  242.21  242.53  243.26  243.65  244.45   244.7  244.01
  244.13  243.46  244.09  243.88  243.03   242.8  242.84  243.13  242.88  243.74
                                                                                
                                                                                
                                                                                
                                                                                
                                                                                
                                                                                
Multiple Barrel Culv=3,6.58,9.75,40,.027,.7,1,34,1,216.69,216.67, 2,Culvert #1  , 0 ,79.07
 1399.73 1399.73 1410.48 1410.48
BC Design=,, 0 ,, 0 ,,,,,,

Type RM Length L Ch R = 1 ,11379.23,549.18,583.47,577.79
XS GIS Cut Line= 6
     1834865.925      399177.781     1834764.681      398763.167
     1834620.049      398411.227     1834234.361      397572.356
     1834075.265      397234.879     1833776.357      396829.907
#Sta/Elev= 30
     .08   244.4  266.18  241.71  271.93  240.85     296  239.78  431.39  235.47
  578.53  231.84  625.33  229.43  678.44  228.97  727.12  227.36  815.55   226.2
  980.84  222.33 1256.44  221.34 1394.18  221.49 1416.04   221.5  1555.3  222.28
 1674.71  224.15 1758.01  226.33 1855.95   226.8 1877.88  227.47 1900.12  229.63
 1929.14  229.79 1978.86  231.36 2049.18  234.86  2140.5  237.32 2195.55  240.32
 2274.33  241.77 2351.67  241.45 2415.08   242.1 2539.96  242.11  2607.1     246
#Mann= 3 , 0 , 0
     .08     .12       0 1394.18    .055       0 1416.04     .12       0
Bank Sta=1394.18,1416.04
Exp/Cntr=.5,.3

Type RM Length L Ch R = 1 ,10795.76,538.11,505.15,496.19
XS GIS Cut Line= 2
     1835364.223      399005.258     1834536.144      396662.977
#Sta/Elev= 30
       0  246.94  167.07  243.54  206.85  241.72   219.5  240.61  299.27  238.58
  409.39  234.31  430.97  232.79  469.38  231.74  524.12  228.53  564.35  227.67
  594.32  225.29  685.46  223.19  921.04  221.68 1383.78  221.81 1406.14  221.69
 1482.04  221.21 1731.34  221.79 1930.35  223.04 2009.95  223.87 2154.16  226.95
 2169.73  227.91 2196.03  230.92 2254.95  238.98 2286.88  242.32 2320.23  246.67
 2336.57  247.66 2363.06  250.73 2433.49  255.93  2449.5  255.12 2484.35  255.68
#Mann= 3 , 0 , 0
       0     .12       0 1383.78    .055       0 1406.14     .12       0
Bank Sta=1383.78,1406.14
Exp/Cntr=.3,.1

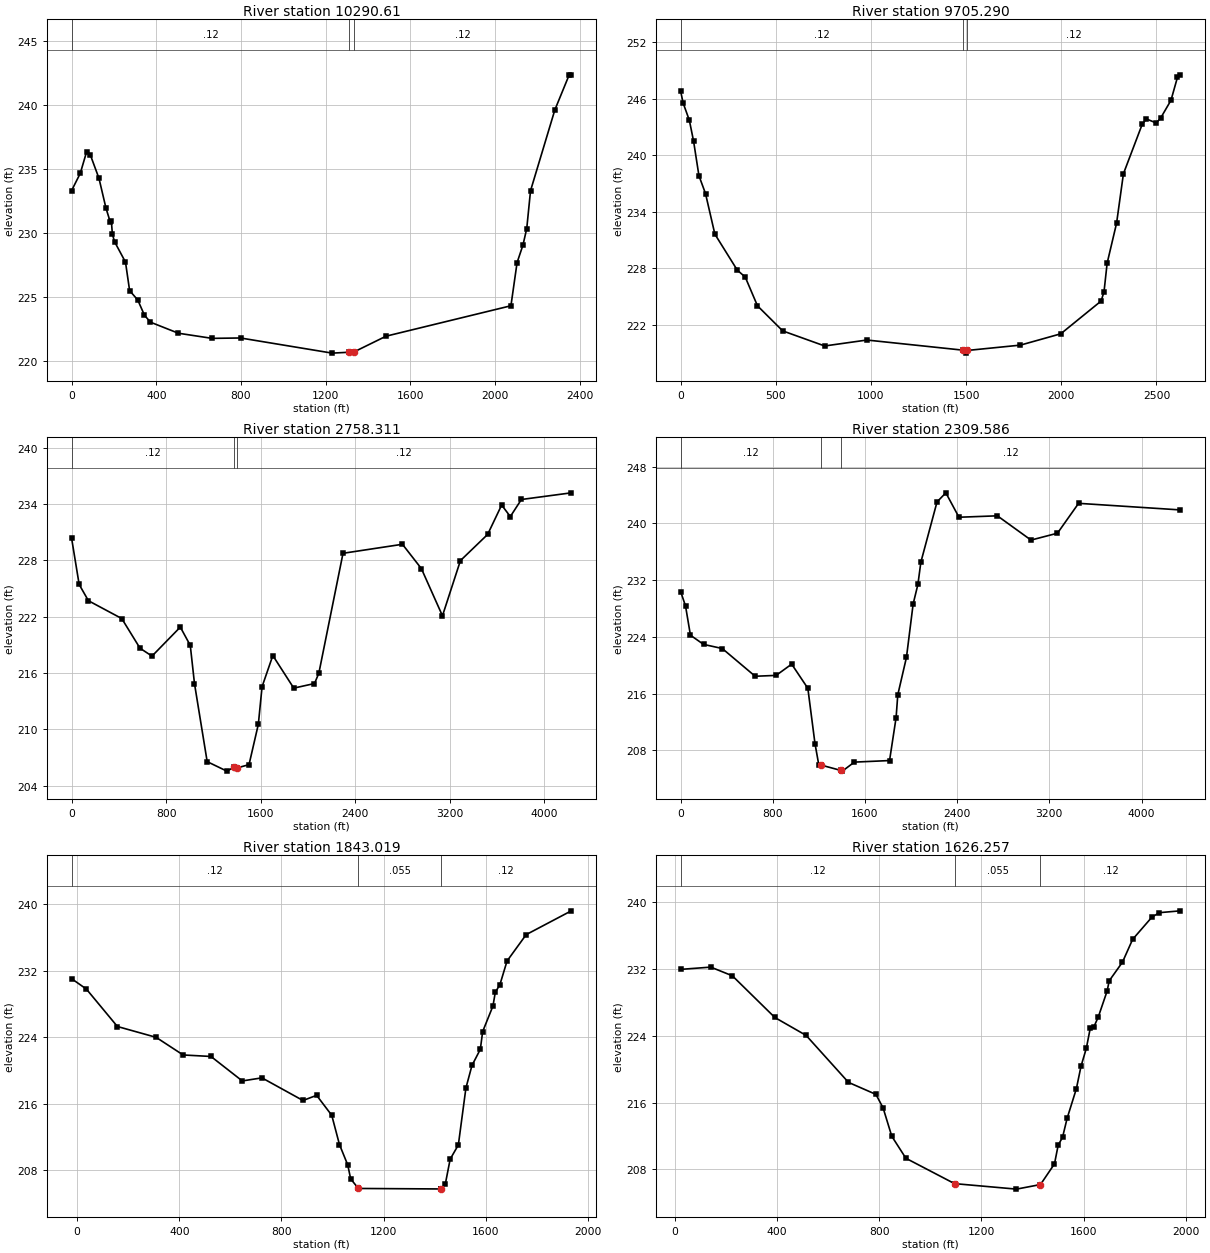
Type RM Length L Ch R = 1 ,10290.61,676.45,585.32,551.23
XS GIS Cut Line= 2
     1835837.411      398768.664     1834985.672       396568.34
#Sta/Elev= 30
       0   233.3   41.32  234.66   71.44  236.35   88.42  236.11  129.66  234.26
  162.54  231.95   182.6  230.88  187.93  230.95  192.83  229.92  203.11  229.33
  254.76  227.74  274.23  225.52  312.63  224.79   344.4   223.6  372.74  223.06
  504.47   222.2  663.38   221.8  797.73  221.83 1230.54  220.65 1311.84  220.72
 1333.08  220.74 1484.85  221.97 2074.41  224.34 2103.37   227.7 2131.02  229.06
    2149  230.35 2166.89   233.3 2281.76   239.6 2348.77   242.3 2359.43  242.33
#Mann= 3 , 0 , 0
       0     .12       0 1311.84    .055       0 1333.08     .12       0
Bank Sta=1311.84,1333.08
Exp/Cntr=.3,.1

Type RM Length L Ch R = 1 ,9705.290,996.58,999.69,914.5
XS GIS Cut Line= 4
     1836760.128      398697.686     1836031.242      397662.601
     1835827.945       397317.88     1835293.245      396521.021
#Sta/Elev= 30
       0  246.79      13  245.54   45.78   243.7   67.93  241.49   96.11  237.82
  130.57  235.93  179.76  231.62  297.53   227.8  339.45  227.06  403.69  224.01
  536.21  221.35  756.66  219.75  978.55  220.38 1480.95  219.31 1499.08  218.99
 1504.58  219.27 1785.07  219.84 1997.01  221.04 2209.07  224.52 2224.35   225.5
 2240.68  228.53 2290.32  232.78 2326.33  238.03 2424.99  243.28 2446.89  243.85
 2498.33  243.42 2521.25  243.92  2576.2  245.83  2610.4  248.28  2625.8  248.53
#Mann= 3 , 0 , 0
       0     .12       0 1480.95    .055       0 1504.58     .12       0
Bank Sta=1480.95,1504.58
Exp/Cntr=.3,.1

Type RM Length L Ch R = 1 ,2758.311,345.03,448.73,747
XS GIS Cut Line= 6
      1838047.76      394002.373     1837867.821      393015.026
     1837523.051      392445.633     1837047.686      392012.058
     1837145.578      391662.359     1837361.113       390126.27
#Sta/Elev= 30
       0  230.41   64.54  225.44  142.68  223.71  424.71  221.81  579.29  218.65
  680.54  217.81  920.05   220.9 1004.33  218.95  1039.9  214.88 1147.22  206.57
 1313.74  205.56 1377.98     206 1399.11   205.9 1501.13  206.25 1579.92  210.55
 1611.47  214.55 1702.45  217.87 1879.59   214.4 2054.91  214.89 2091.69  215.99
 2296.07  228.76 2798.68  229.72 2958.93  227.13 3137.16   222.1 3289.04  227.98
 3519.33  230.77 3637.78   233.9 3711.06  232.67 3804.65  234.49 4226.92   235.2
#Mann= 3 , 0 , 0
       0     .12       0 1377.98    .055       0 1399.11     .12       0
Bank Sta=1377.98,1399.11
Exp/Cntr=.3,.1

Type RM Length L Ch R = 1 ,2309.586,451.69,466.57,506.64
XS GIS Cut Line= 6
     1838149.906      394002.322     1838024.535      392821.746
     1838327.514      392100.863     1838667.061      391599.379
     1838565.671      390768.546     1838170.801      389959.109
#Sta/Elev= 30
       0  230.38   42.61  228.32   84.92  224.23  198.57  222.93  361.12  222.35
   646.8  218.44  828.58  218.56  963.63  220.15 1104.02  216.74 1165.83  208.96
 1199.31  205.92 1214.56  205.94 1388.06  205.18 1403.35  205.07 1507.54  206.34
  1813.1  206.56 1869.98  212.62 1884.44  215.81 1959.92  221.11 2017.94  228.63
 2059.17  231.38  2084.9  234.52  2225.2  243.01 2301.66  244.29 2415.62  240.85
 2748.92  241.05 3040.88  237.63 3270.41   238.6  3453.9  242.81  4337.7  241.88
#Mann= 3 , 0 , 0
       0     .12       0 1214.56    .055       0 1388.06     .12       0
Bank Sta=1214.56,1388.06
Exp/Cntr=.3,.1

Type RM Length L Ch R = 1 ,1843.019,209.48,216.76,212.41
XS GIS Cut Line= 5
       1838274.5       394016.52     1838363.304      393483.694
     1838394.647      393013.553      1838770.76       392485.95
      1838770.76      392188.194
#Sta/Elev= 30
  -22.02  231.04   36.07  229.79  157.64  225.29  309.19  223.99     415  221.87
  524.08  221.69  646.63  218.75  723.57  219.12   884.3   216.4   937.7  217.02
  996.99  214.62 1027.12  211.11 1059.54  208.66 1071.05  206.98 1101.33  205.83
 1424.24  205.77 1425.83  205.75 1441.92   206.4 1460.68  209.35  1492.7  211.06
 1522.34   217.9 1546.03  220.61 1578.77  222.55 1587.89  224.68 1628.29  227.76
 1637.28  229.39 1655.56  230.33 1683.38  233.16 1758.32  236.33 1935.04  239.19
#Mann= 3 , 0 , 0
  -22.02     .12       0 1101.33    .055       0 1424.24     .12       0
Bank Sta=1101.33,1424.24
Exp/Cntr=.3,.1

Type RM Length L Ch R = 1 ,1626.257,675.33,569.97,495.82
XS GIS Cut Line= 5
     1838459.824       394113.87     1838548.628      393581.044
     1838579.971      393110.903     1838956.084        392583.3
     1838956.084      392285.544
#Sta/Elev= 30
   22.02  231.97  139.97  232.24  224.47   231.2  390.82   226.2  513.47  224.05
  679.22  218.42  786.68  216.98  814.78  215.36  848.76  211.96  904.07  209.32
 1094.49  206.28 1337.15  205.62  1431.1  206.17 1485.93  208.65 1500.42   210.9
 1517.35  211.82 1535.39  214.11 1571.62  217.66 1589.91  220.37 1610.46  222.49
 1626.03  224.92 1640.16  225.08 1657.28  226.25 1692.02  229.37 1700.19   230.6
 1752.03  232.83 1791.94  235.57 1867.63  238.24 1896.93  238.77 1979.08  238.99
#Mann= 3 , 0 , 0
   22.02     .12       0 1094.49    .055       0  1431.1     .12       0
Bank Sta=1094.49,1431.1
Exp/Cntr=.3,.1