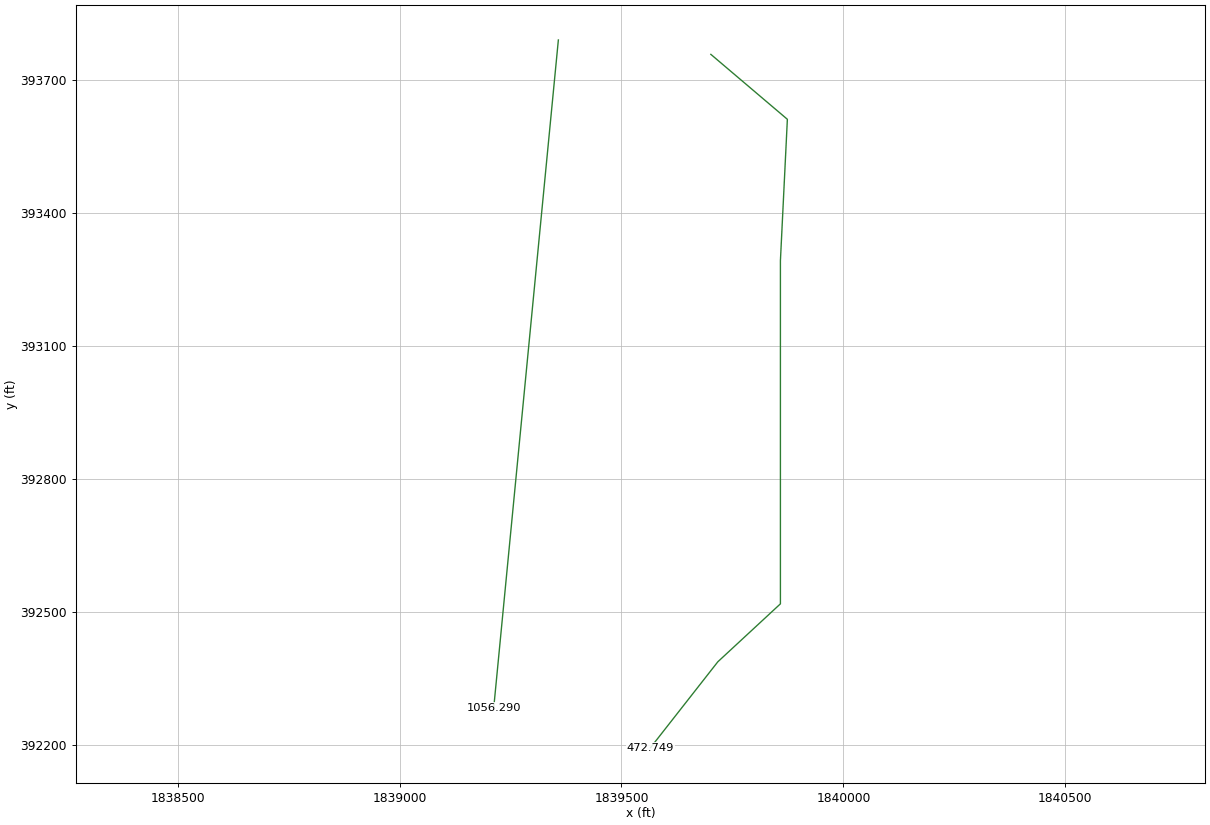
HEC-RAS study gum_limited.prj: Gum Swamp

--- gum_limited.g01 (geometry) --- (continued)

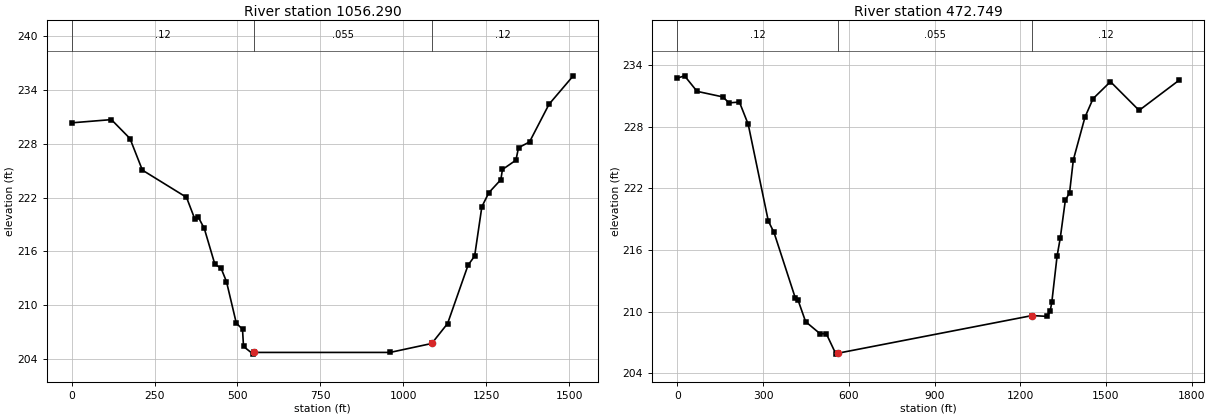
Type RM Length L Ch R = 1 ,1056.290,565.95,583.54,605.41
XS GIS Cut Line= 2
     1839357.748      393789.283     1839212.079      392284.032
#Sta/Elev= 30
       0  230.34  119.85   230.7  175.87  228.59  213.32  225.06  346.33  222.02
  371.86  219.55  382.34  219.78  399.97  218.54  431.91  214.54  450.48  214.11
  466.87  212.61  496.57  207.96   515.2  207.29  518.21  205.37  547.29  204.51
  550.47   204.7  960.06   204.7 1085.82   205.7 1133.51  207.93 1195.11  214.44
    1215  215.46 1236.78  220.97 1257.85  222.54 1293.99  223.99 1298.86  225.13
  1339.5  226.17 1347.26  227.56 1380.53  228.21 1439.38  232.42 1512.28  235.59
#Mann= 3 , 0 , 0
       0     .12       0  550.47    .055       0 1085.82     .12       0
Bank Sta=550.47,1085.82
Exp/Cntr=.3,.1

Type RM Length L Ch R = 1 ,472.749 ,234.25,472.75,336.3
XS GIS Cut Line= 6
     1839701.371      393756.804     1839873.756      393610.538
     1839858.085      393291.887     1839858.085      392518.766
     1839717.043      392388.171     1839565.553      392194.891
#Sta/Elev= 30
       0  232.72   24.81  232.94   68.61  231.43  158.91  230.89  180.45  230.31
  216.87  230.39  247.76  228.22  318.07  218.82  337.87  217.72   412.3  211.36
  421.81  211.16  448.58  209.04  499.42  207.86  520.88  207.88  554.83  205.88
  561.93  205.97 1241.51  209.63 1294.61  209.55 1304.88  210.08 1310.58  210.94
 1329.02  215.42 1340.07  217.16 1357.77  220.82 1372.75  221.59 1385.82  224.76
 1426.62  228.92 1454.92  230.72 1515.86  232.37 1616.14  229.58 1756.02  232.51
#Mann= 3 , 0 , 0
       0     .12       0  561.93    .055       0 1241.51     .12       0
Bank Sta=561.93,1241.51
Exp/Cntr=.3,.1

Chan Stop Cuts=-1
Chan Mod River=Gum Swamp
Chan Mod Reach=Reach 01
Chan Mod RS=56146.35,0,381.51,430.88,359.51,,,237.02,,,,,,237.02,,,,,,237.02,,,
Chan Mod RS=55715.47,0,602.68,802.38,587.97,,,,,,,,,,,,,,,,,,
Chan Mod RS=54913.09,0,403.79,499.25,384.19,,,,,,,,,,,,,,,,,,
Chan Mod RS=54413.84,0,649.56,884.73,623.49,,,,,,,,,,,,,,,,,,
Chan Mod RS=53529.10,0,701.43,950.8,678.49,,,,,,,,,,,,,,,,,,
Chan Mod RS=52578.30,0,757.77,773.92,737.85,,,,,,,,,,,,,,,,,,
Chan Mod RS=51804.38,0,144.8,147.06,148.22,,,,,,,,,,,,,,,,,,
Chan Mod RS=51657.32,0,276.96,425.37,285.74,,,,,,,,,,,,,,,,,,
Chan Mod RS=51231.95,0,328.89,345.87,386.51,,,,,,,,,,,,,,,,,,
Chan Mod RS=50886.07,0,408.69,544.35,585.92,,,,,,,,,,,,,,,,,,
Chan Mod RS=50341.72,0,960.52,887.71,761.47,,,,,,,,,,,,,,,,,,
Chan Mod RS=49454.01,0,417.49,432.71,448.53,,,,,,,,,,,,,,,,,,
Chan Mod RS=49021.30,0,448.7,507.06,494.18,,,,,,,,,,,,,,,,,,
Chan Mod RS=48514.24,0,491.98,530.75,498.95,,,,,,,,,,,,,,,,,,
Chan Mod RS=47983.48,0,604.09,833.02,405.68,,,,,,,,,,,,,,,,,,
Chan Mod RS=47150.46,0,418.16,702.26,775.76,,,,,,,,,,,,,,,,,,
Chan Mod RS=46448.20,0,219.62,230.38,192.73,,,,,,,,,,,,,,,,,,
Chan Mod RS=46217.82,0,221.29,193.51,178.78,,,,,,,,,,,,,,,,,,
Chan Mod RS=46024.32,0,1016.97,1005.4,786.15,,,,,,,,,,,,,,,,,,
Chan Mod RS=45018.92,0,517.35,928.06,885.9,,,,,,,,,,,,,,,,,,
Chan Mod RS=44090.86,0,341.65,247.46,149.74,,,,,,,,,,,,,,,,,,
Chan Mod RS=43843.40,0,491.61,459.01,347.32,,,,,,,,,,,,,,,,,,
Chan Mod RS=43384.39,0,348.12,413.2,288.36,,,,,,,,,,,,,,,,,,
Chan Mod RS=42971.19,0,569.17,672.78,666.05,,,,,,,,,,,,,,,,,,
Chan Mod RS=42298.41,0,704.41,813.8,756.26,,,,,,,,,,,,,,,,,,
Chan Mod RS=41484.61,0,865.6,1013.71,809.02,,,,,,,,,,,,,,,,,,
Chan Mod RS=40470.89,0,671.26,630.64,565.59,,,,,,,,,,,,,,,,,,
Chan Mod RS=39840.25,0,994.82,997.76,850.49,,,,,,,,,,,,,,,,,,
Chan Mod RS=38842.49,0,788.83,819.33,530.65,,,,,,,,,,,,,,,,,,
Chan Mod RS=38023.16,0,314.24,421.84,413.07,,,,,,,,,,,,,,,,,,
Chan Mod RS=37601.33,0,705.91,684.19,582.36,,,,,,,,,,,,,,,,,,
Chan Mod RS=36917.14,0,578.53,639.59,566.89,,,,,,,,,,,,,,,,,,
Chan Mod RS=36277.55,0,850.32,1033.81,985.41,,,,,,,,,,,,,,,,,,
Chan Mod RS=35243.74,0,452.94,613.65,447.78,,,,,,,,,,,,,,,,,,
Chan Mod RS=34630.08,0,543.01,683.16,529.06,,,,,,,,,,,,,,,,,,
Chan Mod RS=33946.92,0,675.12,909.1,658.82,,,,,,,,,,,,,,,,,,
Chan Mod RS=33037.82,0,730.74,1017.22,594.42,,,,,,,,,,,,,,,,,,
Chan Mod RS=32020.60,0,589.96,662.93,647.75,,,,,,,,,,,,,,,,,,
Chan Mod RS=31357.68,0,641.56,777.66,595.45,,,,,,,,,,,,,,,,,,
Chan Mod RS=30580.02,0,543,622.07,561.77,,,,,,,,,,,,,,,,,,
Chan Mod RS=29957.96,0,410.89,649.37,520.47,,,,,,,,,,,,,,,,,,
Chan Mod RS=29308.58,0,93.46,101.21,93.64999,,,,,,,,,,,,,,,,,,
Chan Mod RS=29207.37,0,364.28,405.44,265.64,,,,,,,,,,,,,,,,,,
Chan Mod RS=28801.93,0,593.01,636.93,458.33,,,,,,,,,,,,,,,,,,
Chan Mod RS=28165.00,0,926.43,1111.8,715.68,,,,,,,,,,,,,,,,,,
Chan Mod RS=27053.20,0,759.93,1088.01,1062.92,,,,,,,,,,,,,,,,,,
Chan Mod RS=25965.19,0,451.4,649.75,642.39,,,,,,,,,,,,,,,,,,
Chan Mod RS=25315.44,0,569.93,641.56,511.53,,,,,,,,,,,,,,,,,,
Chan Mod RS=24673.87,0,564.78,980.56,614.15,2259.46,10,205.95,2,2,,,,205.95,,,,,,205.95,,,
Chan Mod RS=23693.31,0,1099.67,1521.69,1076.24,2397.21,10,205.08,2,2,,,,205.08,,,,,,205.08,,,
Chan Mod RS=22171.62,0,714.83,1295.45,1218.69,2737.19,10,203.72,2,2,,,,203.72,,,,,,203.72,,,
Chan Mod RS=20876.17,0,486.66,636.39,524.82,2587.58,10,202.57,2,2,,,,202.57,,,,,,202.57,,,
Chan Mod RS=20239.78,0,723.46,1127.43,1097.5,2598.62,10,202,2,2,,,,202,,,,,,202,,,
Chan Mod RS=19112.35,0,609.04,672.05,671.65,2422,10,201,2,2,,,,201,,,,,,201,,,
Chan Mod RS=18440.30,0,1378.27,1443.74,20921.76,1914.97,10,200.4,2,2,,,,200.4,,,,,,200.4,,,
Chan Mod RS=16996.56,0,1886.59,1682.28,35351.56,2561.44,10,199.12,2,2,,,,199.12,,,,,,199.12,,,
Chan Mod RS=15314.28,0,654.18,667.29,665.24,1931.49,10,197.62,2,2,,,,197.62,,,,,,197.62,,,
Chan Mod RS=14646.99,0,433.77,440.9,455.4,1864.55,10,197.03,2,2,,,,197.03,,,,,,197.03,,,
Chan Mod RS=14206.08,0,380.12,362.17,364.26,1873.02,10,196.63,2,2,,,,196.63,,,,,,196.63,,,
Chan Mod RS=13843.92,0,887.58,822.28,773.49,1836.02,10,196.31,2,2,,,,196.31,,,,,,196.31,,,
Chan Mod RS=13021.64,0,190.54,157.69,202.48,,,195.58,,,,,,195.58,,,,,,195.58,,,
Chan Mod RS=12863.95,0,45.36,55.51,102.44,,,,,,,,,,,,,,,,,,
Chan Mod RS=12808.44,0,134.06,245.06,104.18,,,,,,,,,,,,,,,,,,
Chan Mod RS=12563.38,0,521.75,440.42,347.36,,,,,,,,,,,,,,,,,,
Chan Mod RS=12122.96,0,363.73,470.07,427.76,,,,,,,,,,,,,,,,,,
Chan Mod RS=11652.89,0,148.43,152.57,153.89,,,,,,,,,,,,,,,,,,
Chan Mod RS=11500.32,0,434.57,491.38,449.44,,,,,,,,,,,,,,,,,,
Chan Mod RS=11008.94,0,869.85,896.99,869.46,,,,,,,,,,,,,,,,,,
Chan Mod RS=10111.95,0,823.64,992.9,906.6,,,,,,,,,,,,,,,,,,
Chan Mod RS=9119.055,0,860.68,1133.1,779.41,,,,,,,,,,,,,,,,,,
Chan Mod RS=7985.959,0,339.1,302.69,253.05,,,,,,,,,,,,,,,,,,
Chan Mod RS=7683.269,0,501.34,794.21,684.96,,,,,,,,,,,,,,,,,,
Chan Mod RS=6889.063,0,354.2,353.13,346.76,,,,,,,,,,,,,,,,,,
Chan Mod RS=6535.935,0,560.23,575.49,549.27,,,,,,,,,,,,,,,,,,
Chan Mod RS=5960.443,0,850.85,942.54,512.8,,,,,,,,,,,,,,,,,,
Chan Mod RS=5017.899,0,155.01,145.27,168.41,,,,,,,,,,,,,,,,,,
Chan Mod RS=4872.627,0,209.01,480.58,327.38,,,,,,,,,,,,,,,,,,
Chan Mod RS=4392.048,0,356.38,355.95,352.7,,,,,,,,,,,,,,,,,,
Chan Mod RS=4036.102,0,277.88,382.29,385.9,,,,,,,,,,,,,,,,,,
Chan Mod RS=3653.810,0,243.77,282.63,250.97,,,,,,,,,,,,,,,,,,
Chan Mod RS=3371.178,0,296.18,662.32,619.58,,,,,,,,,,,,,,,,,,
Chan Mod RS=2708.859,0,378.78,472.05,394.36,,,,,,,,,,,,,,,,,,
Chan Mod RS=2236.808,0,588.49,829.15,587.99,,,,,,,,,,,,,,,,,,
Chan Mod RS=1407.654,0,442.54,629.71,412.68,,,,,,,,,,,,,,,,,,
Chan Mod RS=777.945 ,0,329.17,499.82,329.92,,,,,,,,,,,,,,,,,,
Chan Mod RS=278.122 ,0,238.2,277.84,233.66,,,,,,,,,,,,,,,,,,
Chan Mod RS=0.282   ,0,.58,.28,.58,,,,,,,,,,,,,,,,,,