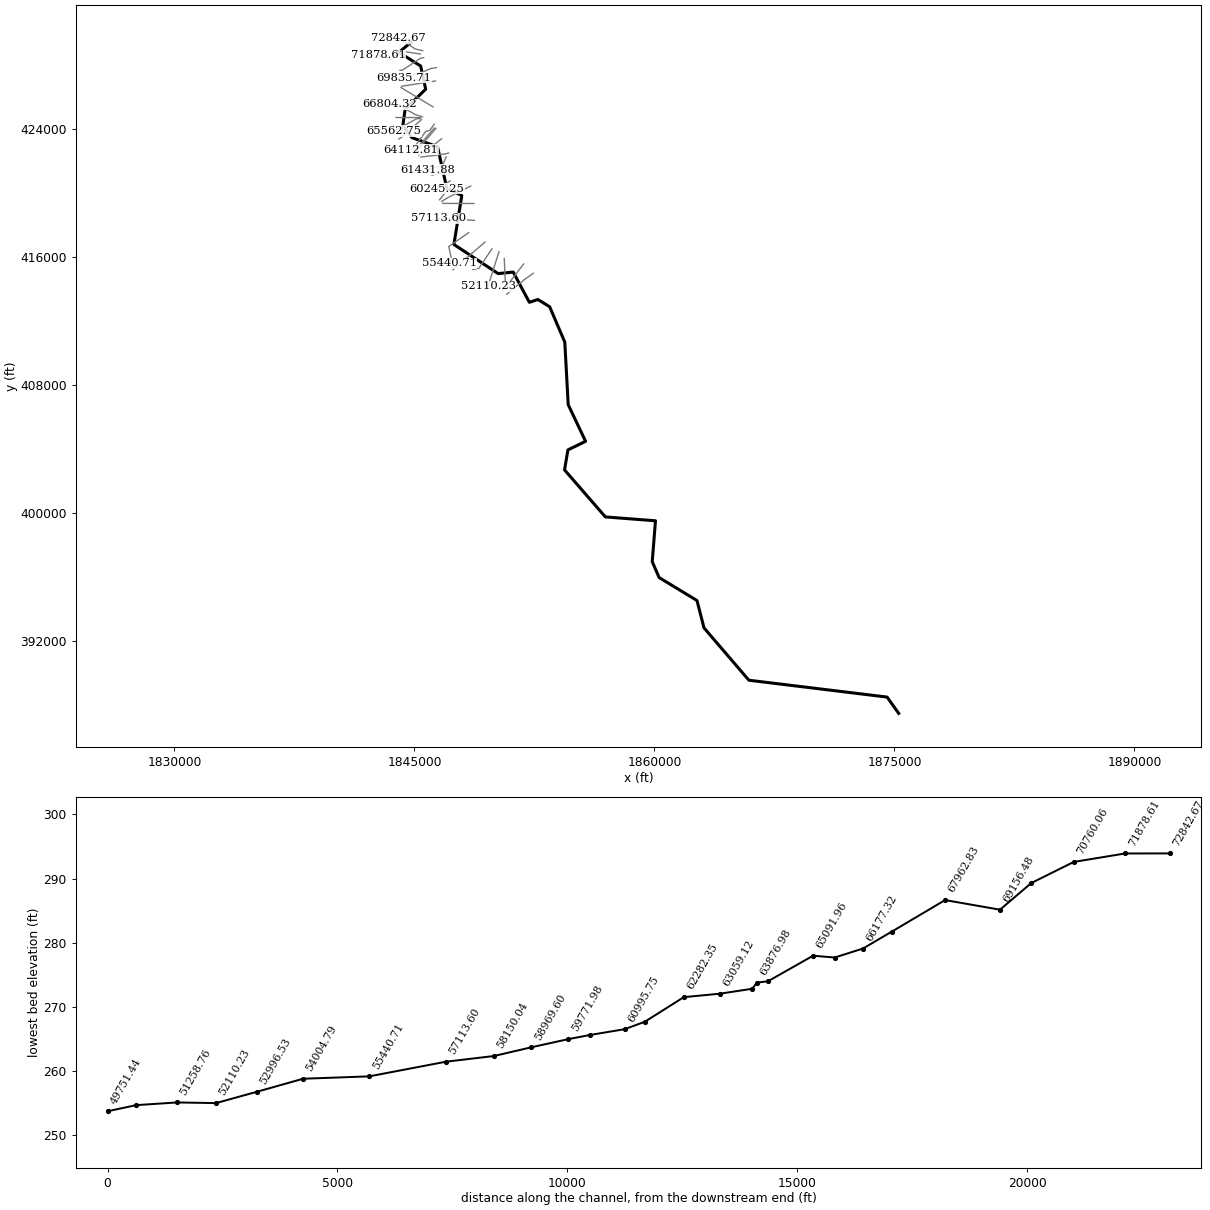
--- jordan.prj (project) ---

Proj Title=Jordan Creek
Current Plan=p01
Default Exp/Contr=.3,.1
English Units
Geom File=g01
Geom File=g02
Flow File=f01
Plan File=p01
Y Axis Title=Elevation
X Axis Title(PF)=Main Channel Distance
X Axis Title(XS)=Station
BEGIN DESCRIPTION:
Approximate Study of Jordan Creek
END DESCRIPTION:

--- jordan.p01 (plan) ---

Plan Title=Plan 01
Version=September 1998 Version 2.2
Short Identifier=Plan 01
Geom File=g02
Flow File=f01
Interactive Comp Mode
Subcritical Flow
K Sum by GR= 0
Std Step Tol= 0.01
Critical Tol= 0.01
Num of Std Step Trials= 20
Max Error Tol= 0.3
Flow Tol Ratio= 0.001
Log Output Level= 0
Friction Slope Method= 1
Parabolic Critical Depth
Global Vel Dist= 0 , 0 , 0
Global Log Level= 0
Encroach Param=-1 ,0,0, 2
Encroach River=Jordan_Creek
Encroach Reach=01
Encroach Node=72842.67
       4      .7
Encroach Node=71878.61
       4      .7
Encroach Node=70760.06
       4      .7
Encroach Node=69835.71
       4      .7
Encroach Node=69156.48
       4      .7
Encroach Node=67962.83
       4      .7
Encroach Node=66804.32
       4      .7
Encroach Node=66177.32
       4      .7
Encroach Node=65562.75
       4      .7
Encroach Node=65091.96
       4      .7
Encroach Node=64112.81
       4      .7
Encroach Node=63876.98
       4      .7
Encroach Node=63827.24
       4      .7
Encroach Node=63765.77
       4      .7
Encroach Node=63059.12
       4      .7
Encroach Node=62282.35
       4      .7
Encroach Node=61431.88
       4      .7
Encroach Node=60995.75
       4      .7
Encroach Node=60245.25
       4      .7
Encroach Node=59771.98
       4      .7
Encroach Node=58969.60
       4      .7
Encroach Node=58150.04
       4      .7
Encroach Node=57113.60
       4      .7
Encroach Node=55440.71
       4      .7
Encroach Node=54004.79
       4      .7
Encroach Node=52996.53
       4      .7
Encroach Node=52110.23
       4      .7
Encroach Node=51258.76
       4      .7
Encroach Node=50375.65
       4      .7
Encroach Node=47476.11
       4      .7
Encroach Node=47047.91
       4      .7
Encroach Node=45913.61
       4      .7
Encroach Node=45231.97
       4      .7
Encroach Node=44463.49
       4      .7
Encroach Node=43009.18
       4      .7
Encroach Node=42612.88
       4      .7
Encroach Node=42275.41
       4      .7
Encroach Node=41861.69
       4      .7
Encroach Node=41619.45
       1 1245.55 1301.45
Encroach Node=41577.14
       1 1245.55 1301.45
Encroach Node=41514.55
       1 1245.55 1301.45
Encroach Node=41218.63
       4      .7
Encroach Node=40463.49
       4      .7
Encroach Node=39323.89
       4      .7
Encroach Node=38027.30
       4      .7
Encroach Node=37309.02
       4      .7
Encroach Node=36641.37
       4      .7
Encroach Node=34436.63
       4      .7
Encroach Node=33007.95
       4      .7
Encroach Node=31816.96
       4      .7
Encroach Node=30342.03
       4      .7
Encroach Node=28539.33
       4      .7
Encroach Node=26309.64
       4      .7
Encroach Node=23754.68
       4      .7
Encroach Node=22987.75
       4      .7
Encroach Node=22318.81
       4      .7
Encroach Node=21597.68
       4      .7
Encroach Node=21216.33
       4      .7
Encroach Node=20861.60
       1 1325.61 1359.39
Encroach Node=20779.95
       1 1325.61 1359.39
Encroach Node=20688.83
       1 1325.61 1359.39
Encroach Node=20422.82
       4      .7
Encroach Node=20035.74
       4      .7
Encroach Node=19596.85
       4      .7
Encroach Node=19266.55
       4      .7
Encroach Node=19179.93
       4      .7
Encroach Node=19107.85
       4      .7
Encroach Node=18901.57
       4      .7
Encroach Node=16596.64
       4      .7
Encroach Node=14777.63
       4      .7
Encroach Node=13662.91
       4      .7
Encroach Node=11737.43
       4      .7
Encroach Node=10680.33
       4      .7
Encroach Node=10301.78
       4      .7
Encroach Node=9990.368
       1 1639.56 1675.84
Encroach Node=9947.97
       1 1639.56 1675.84
Encroach Node=9916.393
       1 1639.56 1675.84
Encroach Node=9367.406
       4      .7
Encroach Node=8927.381
       4      .7
Encroach Node=7739.446
       4      .7
Encroach Node=7128.706
       4      .7
Encroach Node=6402.531
       1 1485.04 1719.61
Encroach Node=6315.12
       1 1485.04 1719.61
Encroach Node=6219.050
       1 1485.04 1719.61
Encroach Node=5644.292
       4      .7
Encroach Node=4172.550
       4      .7
Encroach Node=3391.567
       1 1856.33 2111.33
Encroach Node=3311.65
       1 1856.33 2111.33
Encroach Node=3210.163
       1 1856.33 2111.33
Encroach Node=2294.386
       4      .7
Encroach Node=1686.803
       4      .7

--- jordan.f01 (steady flow) ---

Flow Title=Jordan Flow Data
Version=September 1998 Version 2.2
Number of Profiles= 2
Profile Names=100yr,floodway
River Rch & RM=Jordan_Creek,01              ,72842.67
     562     562
River Rch & RM=Jordan_Creek,01              ,59771.98
     694     694
River Rch & RM=Jordan_Creek,01              ,47047.91
     906     906
River Rch & RM=Jordan_Creek,01              ,20422.82
    1110    1110
River Rch & RM=Jordan_Creek,01              ,4172.550
    1116    1116
Boundary for River Rch & Prof#=Jordan_Creek,01              , 1
Up Type= 0
Dn Type= 3
Dn Slope=.00123
Boundary for River Rch & Prof#=Jordan_Creek,01              , 2
Up Type= 0
Dn Type= 3
Dn Slope=.00123
DSS Import GetInterval= 0
DSS Import GetPeak= 0
DSS Import FillOption= 0

--- jordan.g02 (geometry) ---

Geom Title=Modified Geometry
Version=September 1998 Version 2.2

River Reach=Jordan_Creek    ,01
Reach XY= 30
     1844812.557       429469.35     1844030.155      428818.102
     1845386.922      427962.208      1845701.24      426514.989
     1844416.833       425261.11     1844276.634      424262.755
      1844835.17      423487.137     1846440.678      422915.033
     1847021.234      420317.891     1847957.996      419866.829
     1847465.038      416808.449     1850229.395      414986.638
     1851171.274      415083.093      1852180.03      413192.008
      1852710.84      413369.044     1853449.173      412916.415
       1854395.5      410704.419     1854609.294      406794.468
     1855694.708      404504.245     1854591.204       403966.06
     1854379.548      402717.834      1856932.08      399778.172
     1860063.499      399537.572     1859861.178      396980.698
      1860291.87      395987.327     1862658.073      394552.844
      1863095.72      392845.243      1865901.53      389571.544
     1874540.507      388517.831     1875265.063      387499.555

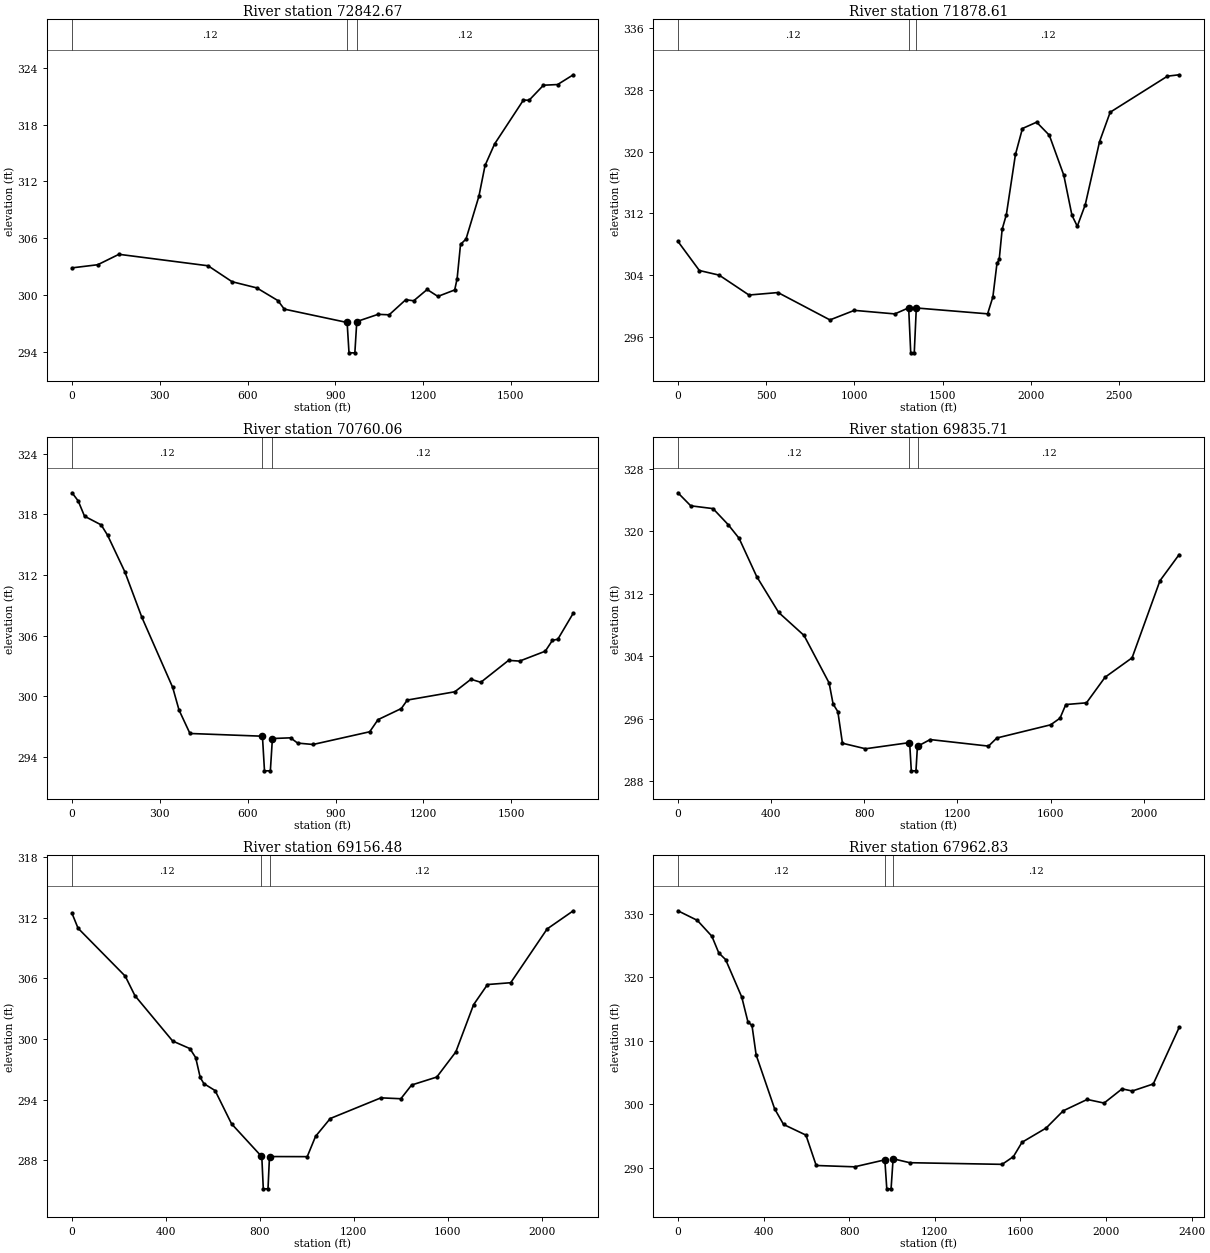
Type RM Length L Ch R = 1 ,72842.67,619.43,964.06,978.73
XS GIS Cut Line= 4
     1845509.903      428919.146      1845035.66       429032.77
     1844336.273      429508.906     1844003.305      429691.734
#Sta/Elev= 30
       0  302.89   87.85  303.22  160.36  304.32  465.08  303.11  547.06  301.43
   631.4  300.78  703.73  299.44  725.64  298.54  940.44  297.13  946.85  293.93
  966.85  293.93  973.46  297.23 1046.34  297.99  1084.1  297.94 1140.82  299.53
  1168.1  299.42 1213.95  300.61 1250.72  299.88 1308.15  300.56 1316.47  301.75
 1328.07  305.36 1346.89  305.93 1390.93  310.44 1411.97  313.69 1444.49  315.95
 1543.23  320.59 1562.39  320.56 1611.65  322.15 1659.95  322.22  1713.6  323.25
#Mann= 3 , 0 , 0
       0     .12       0  940.44     .07       0  973.46     .12       0
Bank Sta=940.44,973.46
Exp/Cntr=.3,.1

Type RM Length L Ch R = 1 ,71878.61,983.71,1118.55,1113.35
XS GIS Cut Line= 6
     1845373.303      428710.156     1844932.844      428777.919
     1844408.602      428854.587     1843740.226      428565.971
     1843591.254      428366.681     1842742.888      428629.234
#Sta/Elev= 30
       0  308.38   121.6   304.6  233.86     304  402.68  301.42  567.17  301.74
  861.52  298.19  999.64  299.43 1229.16  298.97 1307.62  299.76 1319.29  293.92
 1339.29  293.92 1350.92  299.74 1754.95  298.98 1784.79  301.17 1807.93  305.51
 1820.69  306.04  1837.4  309.95 1861.24  311.85 1912.65  319.65  1952.3  323.02
 2032.59  323.84 2104.53  322.15 2186.68  316.96 2232.99  311.75 2263.14  310.34
 2308.31  313.14 2389.34  321.32 2449.43  325.13 2774.09  329.81 2840.37  329.99
#Mann= 3 , 0 , 0
       0     .12       0 1307.62     .07       0 1350.92     .12       0
Bank Sta=1307.62,1350.92
Exp/Cntr=.3,.1

Type RM Length L Ch R = 1 ,70760.06,858.19,924.35,734.94
XS GIS Cut Line= 4
     1845576.592      428486.538     1845373.303       428445.88
     1844241.661      427700.487     1844092.582      427693.711
#Sta/Elev= 30
       0  320.14    20.9  319.34   42.64  317.82   99.45  316.96  121.25  315.94
  180.19  312.32  238.37  307.81   343.7  300.86  365.35  298.62  402.61   296.3
  650.15  296.03  657.17   292.6  677.17   292.6  684.18   295.8  746.18  295.87
  770.18  295.35  822.94  295.21 1016.45  296.47 1044.85  297.67 1124.33  298.77
 1144.82  299.61 1307.03  300.43 1362.15  301.67 1395.85  301.37 1490.55  303.54
 1528.29  303.47 1615.92  304.45 1640.55  305.53 1658.72  305.63 1711.62  308.22
#Mann= 3 , 0 , 0
       0     .12       0  650.15     .07       0  684.18     .12       0
Bank Sta=650.15,684.18
Exp/Cntr=.3,.1

Type RM Length L Ch R = 1 ,69835.71,713.19,679.23,662.76
XS GIS Cut Line= 4
     1846373.096      427863.609      1845987.68        427795.9
     1845669.971      427650.067     1844326.221      427217.775
#Sta/Elev= 30
       0  324.95   55.06  323.28  150.82  322.92  215.37  320.88  262.57  319.12
  338.29  314.21  432.56  309.61  541.57  306.66  649.38  300.56   666.4  297.87
  686.79  296.89  706.54  292.84  805.54  292.13  992.29  292.91  995.23  292.84
 1002.31   289.3 1022.31   289.3 1028.72  292.51 1032.34   292.5 1083.26  293.31
 1333.68  292.47 1369.52  293.51  1600.5   295.2  1640.8  296.05  1665.7   297.8
 1754.53  298.02 1834.23   301.3 1950.34  303.79 2069.94  313.67 2152.47  317.03
#Mann= 3 , 0 , 0
       0     .12       0  992.29     .07       0 1032.34     .12       0
Bank Sta=992.29,1032.34
Exp/Cntr=.3,.1

Type RM Length L Ch R = 1 ,69156.48,1252.03,1193.66,991.24
XS GIS Cut Line= 2
     1846315.499      427028.126     1844206.194      426697.974
#Sta/Elev= 30
       0  312.45   25.65  310.98  226.57  306.23  267.78   304.3  428.58   299.8
  501.93  299.05  526.58  298.16  545.91  296.19  561.43  295.58  609.35  294.89
  679.25   291.6  805.97  288.39  808.15  288.39  814.63  285.15  834.63  285.15
  841.03  288.35  843.28  288.35 1001.74  288.34 1037.19  290.35 1099.81  292.12
 1315.63  294.17 1400.52  294.08 1446.31  295.44 1553.55  296.23 1634.63  298.72
 1710.26   303.4 1769.58   305.4 1868.47  305.58 2023.57  310.91 2134.99  312.71
#Mann= 3 , 0 , 0
       0     .12       0  805.97     .07       0  843.28     .12       0
Bank Sta=805.97,843.28
Exp/Cntr=.3,.1

Type RM Length L Ch R = 1 ,67962.83,1134.32,1158.5,1125.45
XS GIS Cut Line= 2
     1846164.763      425405.275     1844159.555      426613.609
#Sta/Elev= 30
       0  330.48   90.65  328.97  158.77  326.46  190.97  323.83   222.8  322.79
   298.2  316.88  327.24  312.94  346.03   312.4  365.37  307.76  451.54  299.28
  493.44   296.8  597.97  295.12  645.94  290.33  825.08  290.12  966.47  291.22
  975.62  286.65  995.62  286.65  1005.1  291.39 1082.65  290.77 1514.39  290.51
 1567.04  291.73 1607.21  293.99 1719.73  296.23 1799.74  298.95 1911.59  300.74
 1990.57  300.17 2074.49  302.41 2122.02  302.07 2220.24  303.18 2341.14  312.09
#Mann= 3 , 0 , 0
       0     .12       0  966.47     .07       0  1005.1     .12       0
Bank Sta=966.47,1005.1
Exp/Cntr=.3,.1

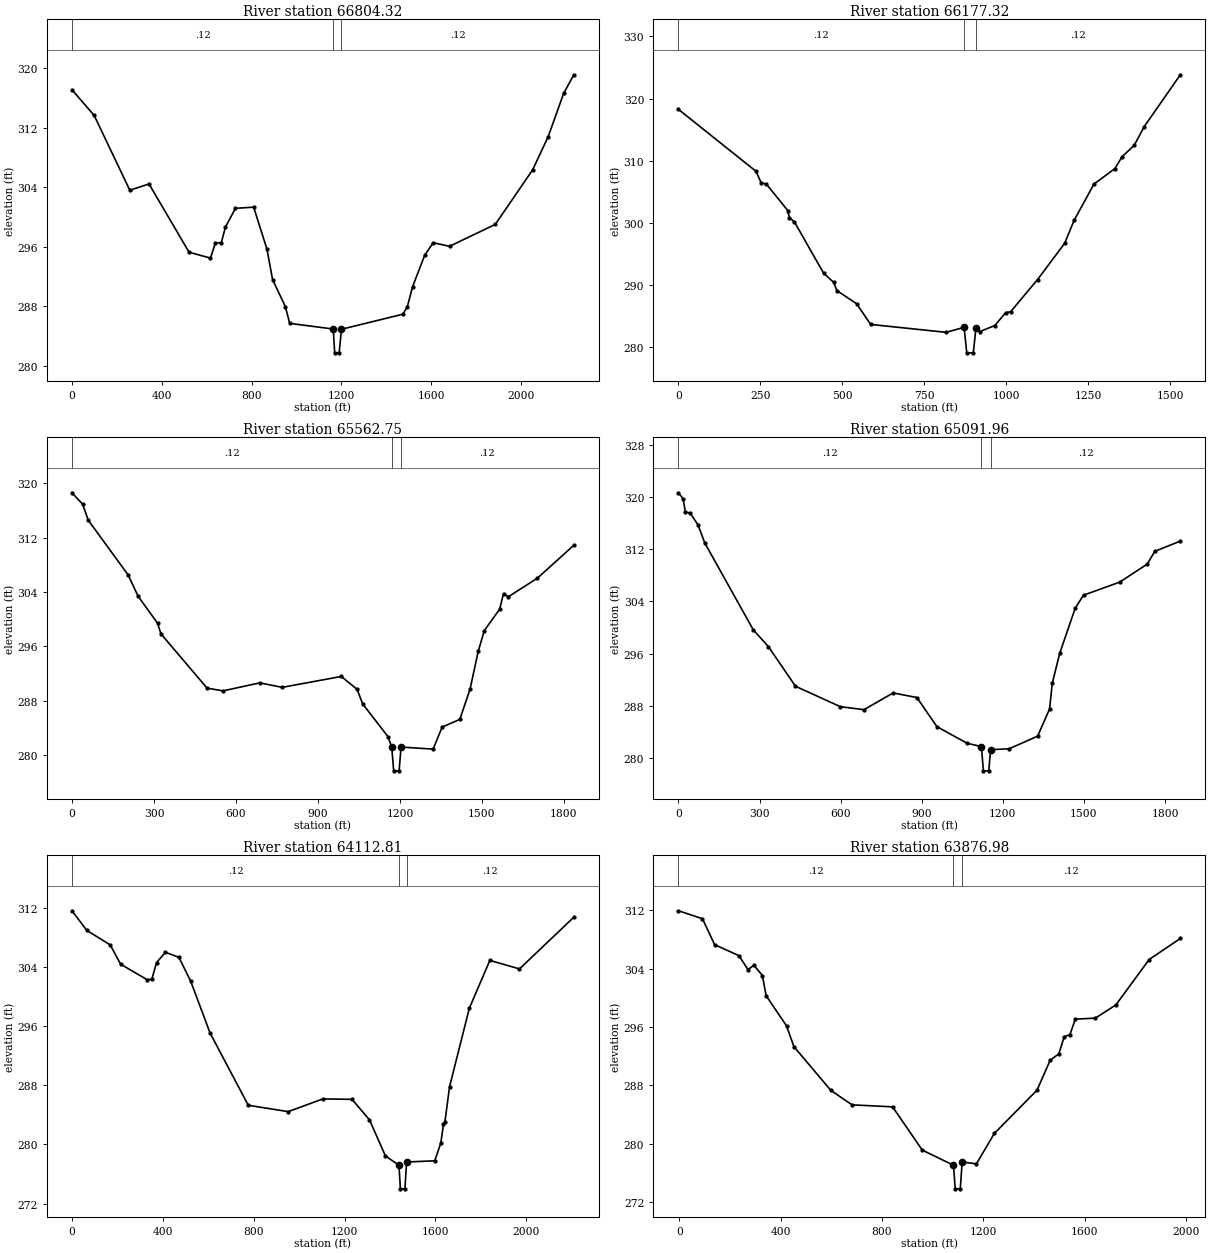
Type RM Length L Ch R = 1 ,66804.32,532.94,627,733.63
XS GIS Cut Line= 4
     1845499.459       424784.52     1845062.737      424922.183
     1843994.664      425534.544     1843448.761      425563.026
#Sta/Elev= 30
       0  317.09   99.03  313.64  257.86  303.58  343.27  304.43  521.87  295.25
  617.19  294.46  638.95   296.5  665.59  296.54  683.74  298.63  728.38  301.15
  809.45  301.31  868.95  295.64  893.78  291.58  950.64  287.95  970.07  285.69
 1164.06  284.93 1170.46  281.73 1190.46  281.73 1200.74   284.9 1474.13  286.92
 1494.44  287.95 1517.28   290.6 1571.57  294.85 1609.42  296.53 1682.01  296.05
 1885.87  298.99 2052.28  306.32 2121.74  310.79 2190.43  316.59 2235.71   319.1
#Mann= 3 , 0 , 0
       0     .12       0 1164.06     .07       0 1200.74     .12       0
Bank Sta=1164.06,1200.74
Exp/Cntr=.3,.1

Type RM Length L Ch R = 1 ,66177.32,567.08,614.58,660.73
XS GIS Cut Line= 2
     1845378.305      424738.609     1843847.055      424743.817
#Sta/Elev= 30
       0  318.26  236.35  308.31   252.4  306.45  268.39  306.23  333.38  301.99
  338.64  300.82  353.79  300.16  442.78  291.91  473.48  290.43  483.46   289.1
  543.28     287  586.51  283.66   816.5  282.39  871.47  283.19  879.67  279.09
  899.67  279.09  907.64  283.07  919.03   282.5  965.17  283.48  998.45  285.56
 1013.54  285.71 1095.63  290.88 1178.47  296.72 1206.99  300.39 1267.73  306.24
 1331.51  308.73 1353.46  310.63  1390.9  312.51 1420.85  315.47 1531.26  323.83
#Mann= 3 , 0 , 0
       0     .12       0  871.47     .07       0  907.64     .12       0
Bank Sta=871.47,907.64
Exp/Cntr=.3,.1

Type RM Length L Ch R = 1 ,65562.75,438.46,470.78,478.01
XS GIS Cut Line= 3
     1845367.888        424670.9     1845149.138        424670.9
     1843727.263      423900.067
#Sta/Elev= 30
       0  318.62   38.83  316.95   59.96  314.57   205.5  306.53  242.17  303.38
  313.22  299.42  325.59  297.86  494.43  289.86   552.9  289.46  687.08  290.64
   769.3  289.98  985.41  291.58 1043.74  289.67 1063.12  287.58 1156.48  282.71
 1170.03   281.2 1177.06  277.69 1197.06  277.69 1204.06  281.19 1321.39  280.89
 1354.66  284.14 1419.17  285.26 1456.61  289.73 1486.57   295.3 1508.83  298.34
 1564.71  301.48 1578.96  303.79 1596.74  303.32 1702.94  306.05 1836.13  310.89
#Mann= 3 , 0 , 0
       0     .12       0 1170.03     .07       0 1204.06     .12       0
Bank Sta=1170.03,1204.06
Exp/Cntr=.3,.1

Type RM Length L Ch R = 1 ,65091.96,931.33,979.16,955.29
XS GIS Cut Line= 4
     1845435.596        424608.4     1844742.888       424014.65
     1844315.805      423603.192     1844029.346      423400.067
#Sta/Elev= 30
       0  320.71   17.01  319.81   25.36  317.76   43.08   317.6   72.51  315.76
   97.14  313.01   276.6  299.65  332.83  297.06  432.89  290.97  598.94  287.83
  686.24  287.37  794.09  289.94  882.04  289.24  956.07  284.76 1067.35  282.22
 1120.64  281.69 1128.07  277.97 1148.07  277.97 1154.59  281.23 1223.27  281.36
 1328.57   283.3 1372.78  287.47 1382.81  291.42 1410.41  296.04 1467.85  302.99
 1498.37  304.97 1632.09  306.97 1734.18  309.75 1762.04  311.71 1856.56  313.28
#Mann= 3 , 0 , 0
       0     .12       0 1120.64     .07       0 1154.59     .12       0
Bank Sta=1120.64,1154.59
Exp/Cntr=.3,.1

Type RM Length L Ch R = 1 ,64112.81,255.48,235.83,222.18
XS GIS Cut Line= 5
      1846237.68      424332.359     1845966.846      423946.942
     1845694.088      423864.985     1844999.271      422893.182
     1844792.299      422737.621
#Sta/Elev= 30
       0  311.59   65.67  308.93  168.36  306.98   214.2  304.37   332.1  302.25
  351.87  302.34  372.36  304.58  411.53  305.98  471.06  305.29  522.99  302.05
  608.24  295.05  776.31  285.29  952.29  284.43 1104.73  286.15 1233.14  286.09
 1309.93  283.32 1379.99  278.45 1439.64  277.18 1446.01  273.99 1466.01  273.99
 1473.28  277.62 1597.18  277.78  1623.8  280.17 1635.75  282.71 1641.93     283
 1662.27  287.77 1749.51  298.41 1839.88  304.88 1970.36  303.73 2209.42  310.72
#Mann= 3 , 0 , 0
       0     .12       0 1439.64     .07       0 1473.28     .12       0
Bank Sta=1439.64,1473.28
Exp/Cntr=.5,.3

Type RM Length L Ch R = 1 ,63876.98,121.73,111.21,116.47
XS GIS Cut Line= 2
     1846237.454      424084.171     1844944.293      422584.812
#Sta/Elev= 30
   -2.97  311.96   91.76  310.87  139.51  307.31  235.47   305.8  271.24  303.89
  294.75  304.47  328.12  303.07  342.77  300.31  423.33  296.16  452.55   293.3
  598.33  287.29  681.95  285.31  841.71  285.04  958.85   279.1 1082.06  277.02
 1088.89  273.78 1108.89  273.78 1116.27  277.47 1172.56  277.21 1243.04  281.38
 1411.66  287.33  1463.6  291.45 1497.53  292.31 1518.83  294.66 1541.46  294.95
 1562.71  297.08  1641.7  297.22 1722.67  299.03 1854.05  305.27 1977.02  308.16
#Mann= 3 , 0 , 0
   -2.97     .12       0 1082.06     .07       0 1116.27     .12       0
Bank Sta=1082.06,1116.27
Exp/Cntr=.5,.3

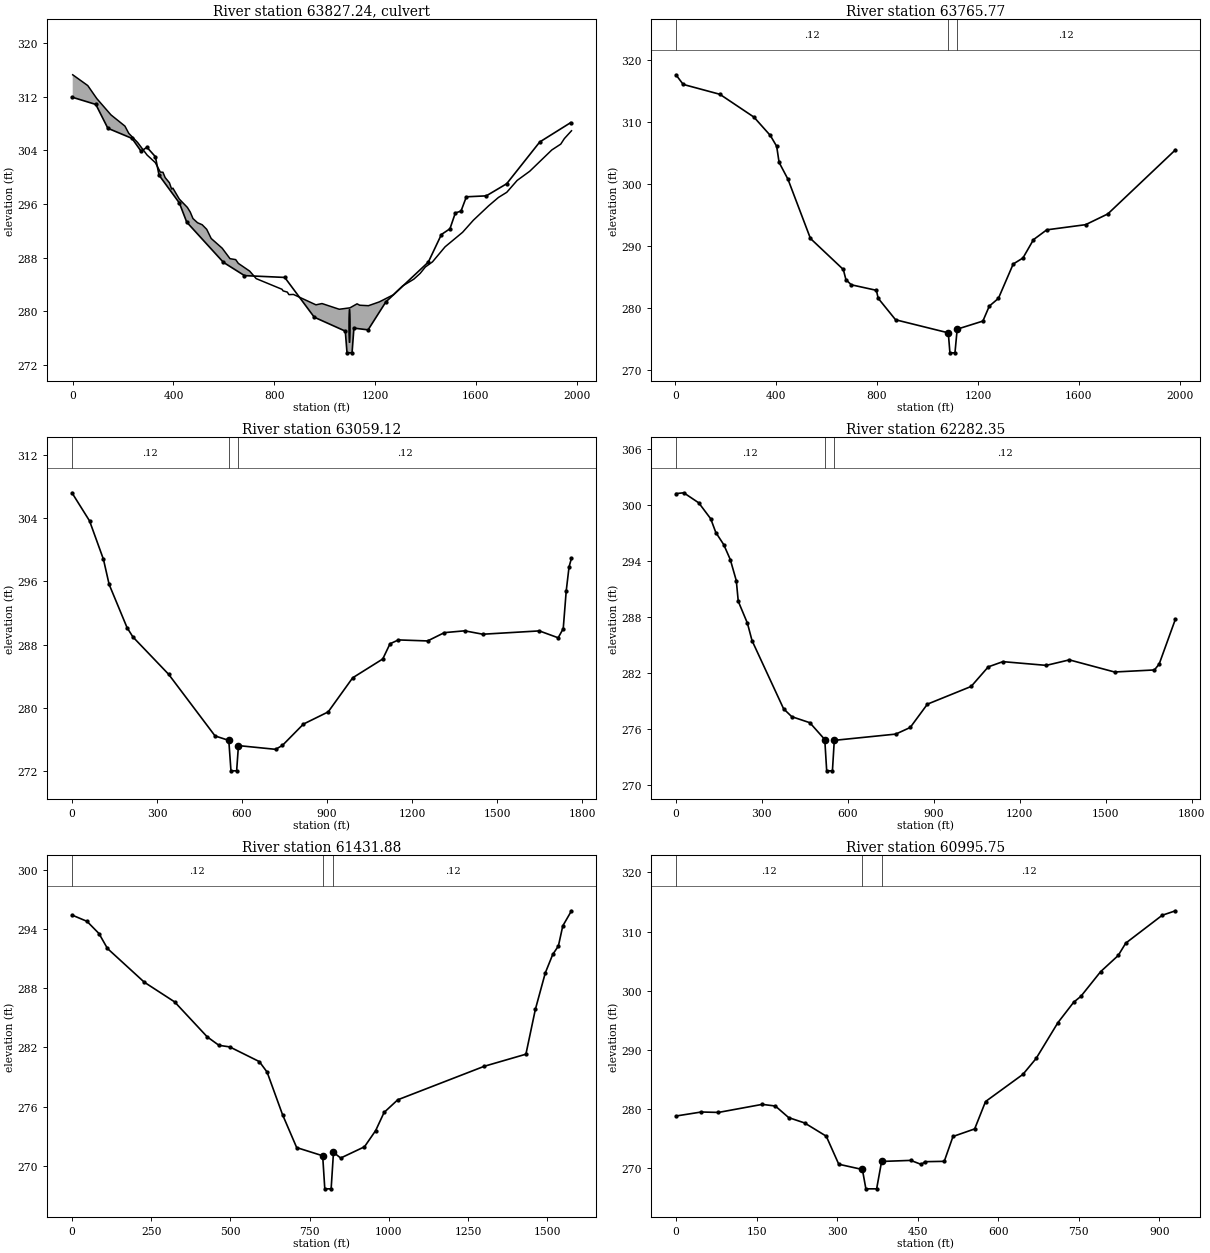
Type RM Length L Ch R = 2 ,63827.24,,,
BEGIN DESCRIPTION:
SR 1341 (NCDOT 82 2050)
END DESCRIPTION:
Bridge Culvert--1,0,-1,-1, 0
Deck Dist Width WeirC Skew NumUp NumDn MinLoCord MaxHiCord MaxSubmerge Is_Ogee
36.99,25.5,2.6,0, 60, 60,280.29,,.95,0,0,0,,
       0   59.78   95.78  151.93  207.23  222.65  257.72   295.4  327.76  347.84
  358.29  366.97  384.05  392.53  397.77   423.3   455.1  466.49  477.46  495.39
  513.88  532.02  549.66  593.51  624.49  646.99  657.39  702.58  728.47  830.78
  835.12  851.89   858.3  876.28   965.5  989.64 1057.91  1100.6 1128.73 1139.29
 1174.01 1217.23  1272.8 1310.08 1353.96 1379.44 1399.81 1428.29 1478.13 1547.68
 1590.36 1650.98  1689.9 1722.98 1764.42 1814.08 1901.99 1937.43 1951.59 1979.99
   315.3  313.69  311.74  309.31  307.64  306.55  305.19  303.31  302.19  300.77
  300.74  299.95  299.17  298.24  298.37  296.73   295.5  294.81  293.83  293.21
  292.91  292.22  290.86   289.4  287.84   287.7  287.14  285.98  284.86  283.27
  283.03  282.85  282.47   282.5  280.95  281.14  280.29   280.5   281.1  280.89
  280.82  281.39  282.45  283.78  284.78  285.65   286.6  287.37  289.61  291.78
  293.58  295.73  296.98  297.75  299.53  300.89  304.08  304.95  305.77  306.94
                                                                                
                                                                                
                                                                                
                                                                                
                                                                                
                                                                                
       0   59.78   95.78  151.93  207.23  222.65  257.72   295.4  327.76  347.84
  358.29  366.97  384.05  392.53  397.77   423.3   455.1  466.49  477.46  495.39
  513.88  532.02  549.66  593.51  624.49  646.99  657.39  702.58  728.47  830.78
  835.12  851.89   858.3  876.28   965.5  989.64 1057.91  1100.6 1128.73 1139.29
 1174.01 1217.23  1272.8 1310.08 1353.96 1379.44 1399.81 1428.29 1478.13 1547.68
 1590.36 1650.98  1689.9 1722.98 1764.42 1814.08 1901.99 1937.43 1951.59 1979.99
   315.3  313.69  311.74  309.31  307.64  306.55  305.19  303.31  302.19  300.77
  300.74  299.95  299.17  298.24  298.37  296.73   295.5  294.81  293.83  293.21
  292.91  292.22  290.86   289.4  287.84   287.7  287.14  285.98  284.86  283.27
  283.03  282.85  282.47   282.5  280.95  281.14  280.29   280.5   281.1  280.89
  280.82  281.39  282.45  283.78  284.78  285.65   286.6  287.37  289.61  291.78
  293.58  295.73  296.98  297.75  299.53  300.89  304.08  304.95  305.77  306.94
                                                                                
                                                                                
                                                                                
                                                                                
                                                                                
                                                                                
Culvert=1,5,,25.5,.027,.7,1,2,2,275.29,1098.89,275.29,1098.89,Culvert #1  , 0 ,36.99
BC Design=,, 0 ,, 0 ,,,,,,

Type RM Length L Ch R = 1 ,63765.77,694.36,706.65,677.38
XS GIS Cut Line= 2
      1846343.37      424065.837      1845050.21      422566.478
#Sta/Elev= 30
    2.97  317.55   31.72     316  177.08  314.41  312.07  310.74  377.11  307.78
  402.22  306.04  411.79  303.45  446.89  300.75  536.07  291.21  666.36  286.22
  676.77  284.58  697.81  283.76  797.39  282.87  804.52  281.59  873.52  278.13
 1080.08  276.05 1082.47  276.02 1088.89  272.81 1108.89  272.81  1117.7  276.62
 1219.52  277.92 1244.99  280.33 1281.06  281.57  1339.7   287.1 1378.31  288.07
 1420.03  291.02 1472.71   292.6 1626.65  293.43 1714.69  295.16 1982.95  305.48
#Mann= 3 , 0 , 0
    2.97     .12       0 1080.08     .07       0  1117.7     .12       0
Bank Sta=1080.08,1117.7
Exp/Cntr=.5,.3

Type RM Length L Ch R = 1 ,63059.12,793.72,776.78,673.81
XS GIS Cut Line= 3
     1846695.094      423419.454     1845828.322      422720.379
     1845263.721      422400.067
#Sta/Elev= 30
       0  307.19   62.04  303.64  111.11  298.78  131.24   295.6  194.33  290.15
  215.17  288.96  341.01  284.25     505  276.45  553.42  275.89  561.11  272.04
  581.11  272.04  587.48  275.23  718.49  274.76  742.48  275.25  816.78  277.95
  904.11  279.49  990.56   283.8 1096.68  286.18 1122.23   288.1 1151.93  288.59
 1254.85  288.46 1314.05  289.51 1385.72  289.74 1449.58  289.31 1649.22  289.73
 1715.59  288.86 1733.54  290.01 1744.09  294.79 1754.08  297.82 1762.69  298.93
#Mann= 3 , 0 , 0
       0     .12       0  553.42     .07       0  587.48     .12       0
Bank Sta=553.42,587.48
Exp/Cntr=.3,.1

Type RM Length L Ch R = 1 ,62282.35,782.43,850.47,741.08
XS GIS Cut Line= 4
     1847134.264      422521.971     1846912.979      422468.327
     1846138.966      422357.206     1845409.555      422275.067
#Sta/Elev= 30
       0  301.24   27.13  301.33   79.63  300.25  121.41  298.54  139.16  297.07
  166.79  295.77  189.66  294.17  210.69   291.9  217.52  289.69  249.51  287.34
  265.64  285.47  375.83  278.16   404.2  277.32  467.41  276.67  519.47  274.87
  526.18  271.51  546.18  271.51  552.72  274.78  767.22  275.45  817.74  276.16
  877.67  278.66 1030.37  280.56 1090.12  282.66 1141.26  283.22 1292.62  282.82
 1373.13  283.41 1531.02  282.11 1670.16  282.33 1686.67  282.96 1743.66   287.8
#Mann= 3 , 0 , 0
       0     .12       0  519.47     .07       0  552.72     .12       0
Bank Sta=519.47,552.72
Exp/Cntr=.3,.1

Type RM Length L Ch R = 1 ,61431.88,432.17,436.13,424.8
XS GIS Cut Line= 3
     1846977.263      422280.275     1846759.021      421747.166
     1845794.109      421483.568
#Sta/Elev= 30
       0   295.4   47.44  294.76   85.34  293.52     112  292.01  228.43  288.59
  323.97   286.6  426.75  283.06   463.8   282.2  497.79  282.04  591.26  280.55
  615.73  279.49  664.43  275.18  709.11  271.84  791.16  271.01  797.86  267.66
  817.86  267.66  825.25  271.36  847.97  270.78  923.05  271.92  958.48  273.57
  984.93   275.4    1028  276.68 1301.38  280.08 1432.47   281.3 1462.21  285.83
 1493.67  289.54 1517.17  291.41 1534.92  292.26 1548.86   294.3 1576.32  295.83
#Mann= 3 , 0 , 0
       0     .12       0  791.16     .07       0  825.25     .12       0
Bank Sta=791.16,825.25
Exp/Cntr=.3,.1

Type RM Length L Ch R = 1 ,60995.75,720.64,750.49,783.07
XS GIS Cut Line= 2
     1846997.698      421354.911     1846091.846      421144.859
#Sta/Elev= 30
       0  278.82   47.19   279.5   79.18  279.43  160.65  280.79  185.04  280.51
  209.88  278.55  239.52  277.65  279.79  275.41  303.09  270.67  347.05  269.78
  353.58  266.51  373.58  266.51  382.84  271.14  437.09  271.32  456.79  270.63
  463.47   271.1  499.45  271.16   515.7  275.36  556.06  276.64  576.31  281.27
  645.96  285.87  670.45  288.55   710.9  294.59  740.47  298.07  753.73  299.05
  790.47  303.22  823.24  305.96  837.28  308.05  905.16  312.76  929.89  313.52
#Mann= 3 , 0 , 0
       0     .12       0  347.05     .07       0  382.84     .12       0
Bank Sta=347.05,382.84
Exp/Cntr=.3,.1

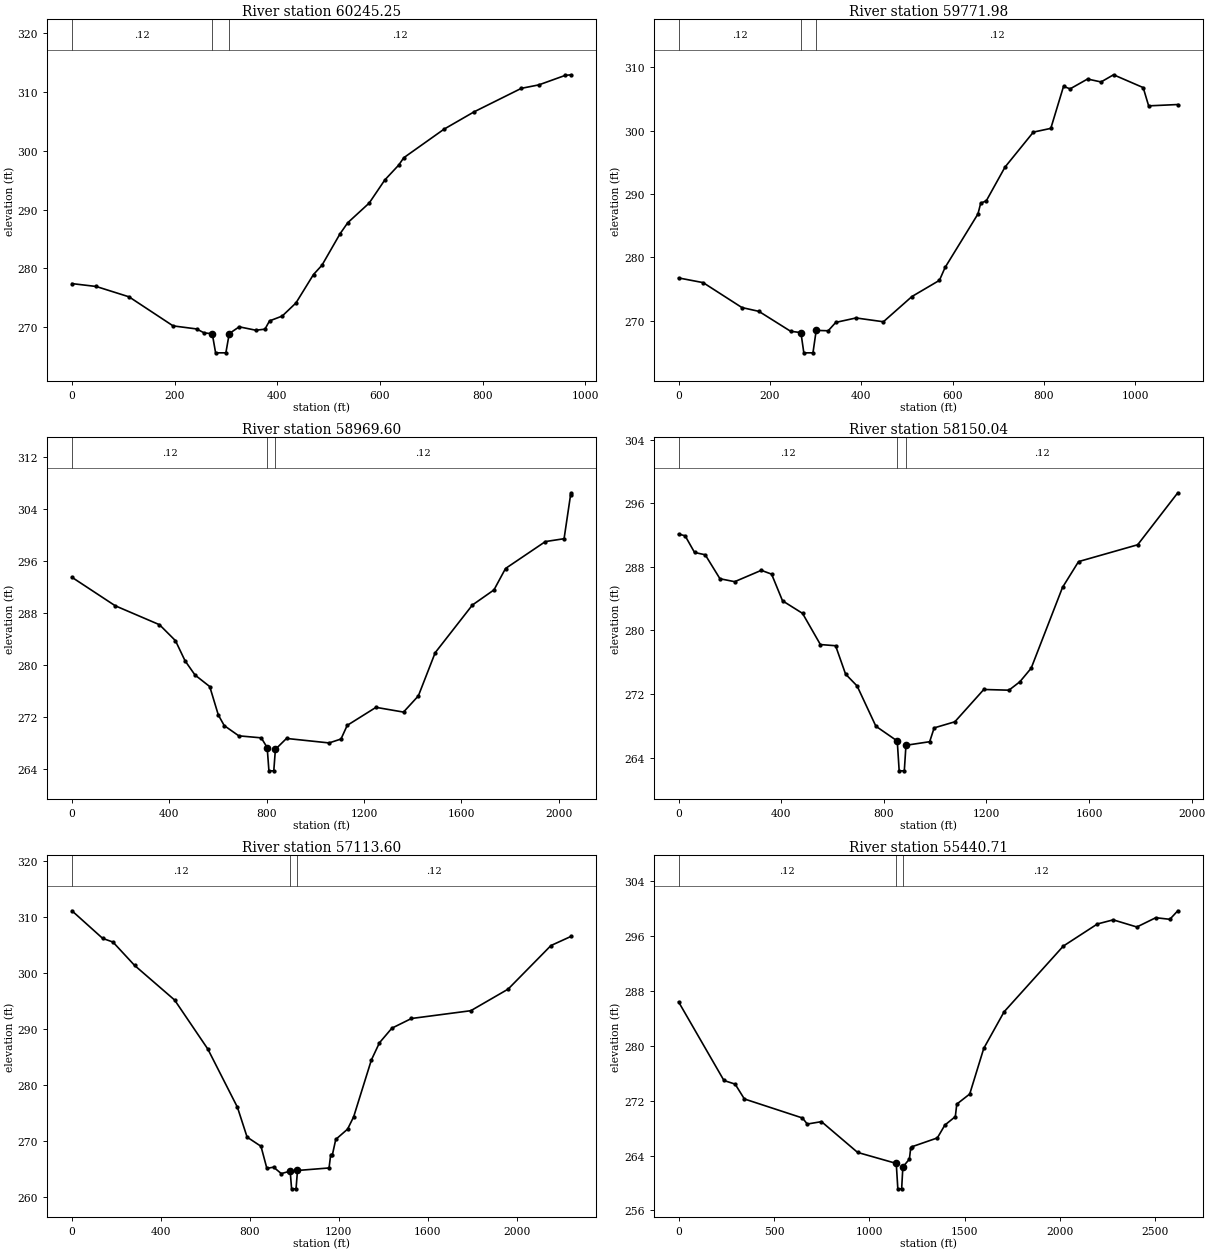
Type RM Length L Ch R = 1 ,60245.25,408.21,473.27,450.47
XS GIS Cut Line= 2
      1847226.82      420774.502     1846383.513      420290.692
#Sta/Elev= 30
       0   277.4   47.28  276.91  111.12  275.15  197.01   270.2  242.81  269.68
  257.42  269.01  273.32  268.86  279.82  265.61  299.82  265.61  306.39  268.89
  325.83  270.04  358.18  269.46  375.94  269.64  384.84  271.05  409.51  271.87
  436.29   274.1   470.5  278.95  486.99  280.53  522.23  285.89  537.25  287.77
  578.92  291.11  609.39  295.05  636.43  297.58  646.27  298.83  724.78   303.7
  783.51  306.66  875.29  310.65  909.41  311.24  960.53  312.85  972.23  312.96
#Mann= 3 , 0 , 0
       0     .12       0  273.32     .07       0  306.39     .12       0
Bank Sta=273.32,306.39
Exp/Cntr=.3,.1

Type RM Length L Ch R = 1 ,59771.98,850.63,802.38,739.07
XS GIS Cut Line= 2
     1847263.816      420441.656     1846565.308      419600.595
#Sta/Elev= 30
       0  276.77    53.7  276.03  138.67   272.1  175.84   271.5   245.3  268.36
  267.88  268.15  274.26  264.96  294.26  264.96  301.35   268.5  327.61  268.44
  344.23  269.76  388.59  270.46  448.53  269.86  511.06  273.84  571.25  276.39
  583.63  278.42  655.58  286.85  661.69  288.56  673.84  288.92  714.84  294.24
  776.99  299.76   815.2  300.35  843.06  306.97   857.5  306.58  895.65  308.13
  925.21  307.67  952.61   308.8 1017.53  306.78 1029.48   303.9  1093.3  304.11
#Mann= 3 , 0 , 0
       0     .12       0  267.88     .07       0  301.35     .12       0
Bank Sta=267.88,301.35
Exp/Cntr=.3,.1

Type RM Length L Ch R = 1 ,58969.60,839.79,819.56,748.85
XS GIS Cut Line= 3
      1848518.93      420462.567     1847128.305      419759.442
      1846706.43      419504.234
#Sta/Elev= 30
       0  293.44  178.03  289.06  359.77  286.15  425.35   283.7  464.95   280.6
  505.75  278.42  566.35  276.64  601.61  272.27  625.95  270.64  685.76  269.07
  777.99  268.76  802.35  267.27  809.51  263.69  829.51  263.69  836.11  266.99
  881.78  268.67 1056.76  267.98 1105.68  268.58 1131.27  270.68 1249.51  273.45
 1362.63  272.72 1423.62  275.21 1492.79  281.85 1645.77  289.18 1734.38   291.5
 1781.75  294.79 1945.65  298.93 2022.47  299.37 2050.46  306.43 2051.34  306.13
#Mann= 3 , 0 , 0
       0     .12       0  802.35     .07       0  836.11     .12       0
Bank Sta=802.35,836.11
Exp/Cntr=.3,.1

Type RM Length L Ch R = 1 ,58150.04,1016.17,1036.44,1002.52
XS GIS Cut Line= 2
      1848713.18      419368.595     1846767.373      419376.079
#Sta/Elev= 30
       0  292.15    25.4  291.93   62.12  289.83  103.71  289.54  161.17  286.52
  218.53  286.15  322.34  287.58  362.47   287.1  405.07  283.74  483.03  282.16
  552.68  278.23  611.93  278.08  650.78  274.51  695.81  273.01     769  267.94
  852.27  266.08  859.78  262.32  879.78  262.32  886.23  265.54  978.67  265.99
  996.11  267.73 1076.83   268.5 1189.66  272.57 1287.63  272.48 1330.24  273.54
 1374.32  275.25 1496.49  285.43 1558.98  288.68 1789.44   290.8 1945.82  297.35
#Mann= 3 , 0 , 0
       0     .12       0  852.27     .07       0  886.23     .12       0
Bank Sta=852.27,886.23
Exp/Cntr=.3,.1

Type RM Length L Ch R = 1 ,57113.60,1520.55,1672.9,1644.62
XS GIS Cut Line= 2
     1848746.349      418313.702     1846505.437      418448.078
#Sta/Elev= 30
       0  311.11  138.14  306.18  184.58  305.52  281.56  301.36  461.77  295.17
  611.14  286.41   744.2  276.02  787.78  270.68   850.2  269.04  876.65   265.1
  907.09  265.31  941.55  264.16  981.53  264.61  987.88  261.44 1007.88  261.44
 1014.43  264.72 1156.32  265.17 1163.79  267.55 1171.01  267.46 1186.46  270.27
 1239.55   272.1 1266.93   274.3 1346.69  284.46 1382.99  287.53 1438.94  290.14
 1527.06  291.87 1793.89  293.26 1961.44  297.11 2154.34   304.9 2244.94  306.54
#Mann= 3 , 0 , 0
       0     .12       0  981.53     .07       0 1014.43     .12       0
Bank Sta=981.53,1014.43
Exp/Cntr=.3,.1

Type RM Length L Ch R = 1 ,55440.71,1346.35,1435.92,1360
XS GIS Cut Line= 4
     1848398.858      417550.013     1847142.778      416682.985
     1847300.054      415952.123     1847169.971      415634.442
#Sta/Elev= 30
       0  286.35  237.65  274.92  296.36  274.39  344.84  272.23  649.52  269.46
  674.45  268.58  749.05  268.93  938.54  264.45 1141.07  262.85 1149.39  259.15
 1169.39  259.15  1175.9  262.41 1177.71   262.4 1209.94  263.48 1217.05  265.12
 1221.59  265.26 1356.52  266.56 1395.94  268.43 1450.78  269.66 1458.45  271.48
 1526.26  272.95 1599.97   279.6 1706.37  284.91 2016.95  294.48 2195.61   297.7
 2278.55   298.3 2402.53  297.26 2501.58  298.61 2575.48  298.38 2617.14  299.62
#Mann= 3 , 0 , 0
       0     .12       0 1141.07     .07       0 1177.71     .12       0
Bank Sta=1141.07,1177.71
Exp/Cntr=.3,.1

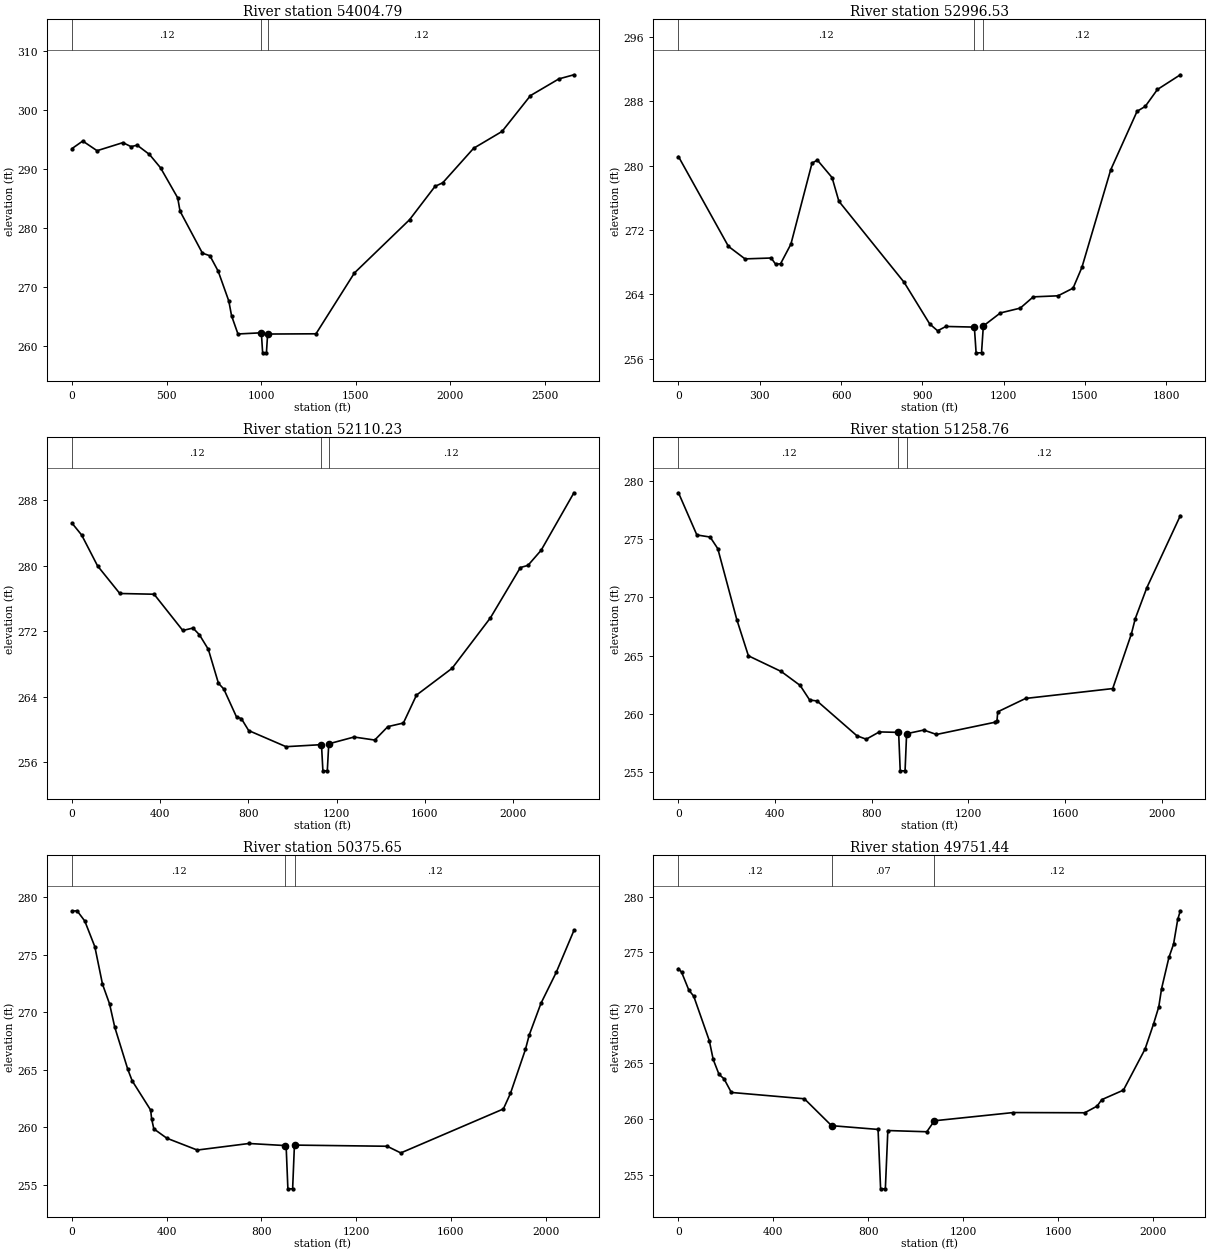
Type RM Length L Ch R = 1 ,54004.79,980.06,1008.26,979.92
XS GIS Cut Line= 2
     1849409.181      416958.787     1847403.502      415222.528
#Sta/Elev= 30
       0  293.44    56.4  294.71  132.15  293.07   268.7  294.44  311.87  293.76
  344.05  294.01  409.17  292.43  467.45  290.18  558.34  285.07  570.76  282.81
  689.04  275.69  728.64  275.25  772.26  272.64  828.54  267.57  842.98  265.08
  876.83  261.98 1000.56  262.18 1007.35  258.78 1027.35  258.78 1033.72  261.97
 1289.37  262.01 1492.46  272.33  1783.9  281.36 1918.57  287.02 1959.51  287.63
 2122.53  293.48 2272.94  296.34 2423.21  302.42 2573.15  305.25  2652.8  305.95
#Mann= 3 , 0 , 0
       0     .12       0 1000.56     .07       0 1033.72     .12       0
Bank Sta=1000.56,1033.72
Exp/Cntr=.3,.1

Type RM Length L Ch R = 1 ,52996.53,762.99,886.3,835.66
XS GIS Cut Line= 3
      1849843.97      416537.662     1849023.351      415318.965
     1848649.138      415238.609
#Sta/Elev= 30
       0  281.14   184.3  269.98  245.54  268.42  342.01  268.53  358.68  267.75
  376.79  267.82  414.86  270.25  492.89  280.33  512.65   280.7  566.81  278.53
   591.9  275.59  832.69  265.51  927.18  260.33  956.29  259.48  986.91  260.02
 1091.94  259.94 1098.34  256.74 1118.34  256.74 1125.03  260.08 1187.88   261.7
 1261.27   262.3 1309.25   263.7 1400.61  263.83 1456.17  264.78 1488.74  267.36
 1595.07  279.49 1692.39  286.77 1722.59  287.38 1767.38  289.48 1851.97  291.31
#Mann= 3 , 0 , 0
       0     .12       0 1091.94     .07       0 1125.03     .12       0
Bank Sta=1091.94,1125.03
Exp/Cntr=.3,.1

Type RM Length L Ch R = 1 ,52110.23,794.84,851.47,829.46
XS GIS Cut Line= 2
     1850284.794      416360.077     1849596.278      414189.753
#Sta/Elev= 30
       0  285.22   43.48  283.78  115.67  280.01   216.5  276.64  372.12  276.55
   502.4  272.12  548.64  272.42  577.76   271.6   618.2  269.82  664.15  265.67
  688.24  264.98  746.41  261.54  767.79  261.37  801.25   259.9   970.7  257.93
 1131.61  258.18 1138.01  254.98 1158.01  254.98 1164.62  258.28 1279.43  259.11
 1373.17  258.74 1432.71  260.38 1503.21  260.82 1562.63  264.23 1724.39  267.51
 1898.17  273.67 2033.98  279.81 2068.32  280.07 2128.19  281.92 2276.92  288.94
#Mann= 3 , 0 , 0
       0     .12       0 1131.61     .07       0 1164.62     .12       0
Bank Sta=1131.61,1164.62
Exp/Cntr=.3,.1

Type RM Length L Ch R = 1 ,51258.76,852.49,883.11,516.38
XS GIS Cut Line= 3
     1850610.076      415928.713      1850695.11      414121.734
     1850530.307      413910.598
#Sta/Elev= 30
       0  279.01   76.09  275.38  131.04   275.2  162.73   274.2  241.33   268.1
  289.38  264.98  425.32  263.63  503.49  262.43  542.78  261.18  573.55  261.09
  738.36   258.1  776.95   257.8  831.05  258.43  910.45  258.39  911.08  258.39
   917.7  255.08   937.7  255.08  944.11  258.28  944.95  258.28 1015.18  258.59
 1067.64  258.21 1311.49  259.27 1318.15   259.4 1321.26  260.16 1436.41  261.31
 1797.02  262.16 1874.22  266.86 1890.38  268.18  1938.2  270.84 2076.82  277.04
#Mann= 3 , 0 , 0
       0     .12       0  910.45     .07       0  944.95     .12       0
Bank Sta=910.45,944.95
Exp/Cntr=.3,.1

Type RM Length L Ch R = 1 ,50375.65,640.09,624.21,522.64
XS GIS Cut Line= 3
     1851823.617      415590.171     1850697.742      414120.155
     1850537.152      413905.332
#Sta/Elev= 30
       0  278.79   21.11  278.82    53.7  277.93   96.14   275.7  128.53  272.44
  158.35  270.73  180.13  268.72  235.43  265.04  254.05  264.04  332.06   261.5
   335.9  260.76  345.34  259.87  400.15  259.06  528.83  258.03  747.08   258.6
   900.5  258.42  904.35  258.31  911.65  254.66  931.65  254.66  939.05  258.36
  942.79  258.46 1331.01  258.36 1388.56  257.78 1821.86   261.6 1851.86  262.96
    1915  266.77 1930.94  268.02 1980.64  270.78 2044.96  273.46 2119.85  277.11
#Mann= 3 , 0 , 0
       0     .12       0   900.5     .07       0  942.79     .12       0
Bank Sta=900.5,942.79
Exp/Cntr=.3,.1

Type RM Length L Ch R = 1 ,49751.44,543.46,507.47,439.45
XS GIS Cut Line= 3
     1852427.784      415006.838     1851865.284      414611.005
     1850766.326      413699.546
#Sta/Elev= 30
       0  273.54    13.1  273.22   43.61  271.61   64.23  271.06  129.86  267.06
  146.42  265.36  170.85  264.02  191.97  263.62  222.82  262.39  530.73  261.82
  645.25   259.4   841.4  259.06  852.09  253.71  872.09  253.71  882.59  258.96
 1046.84  258.85 1078.94  259.84 1411.36  260.58 1712.61  260.56 1764.79  261.16
 1784.24  261.74 1875.72   262.6 1966.94   266.3 2002.53  268.55 2024.71   270.1
 2036.46  271.73 2067.52  274.55 2087.07  275.75 2104.62  277.97 2115.56  278.75
#Mann= 3 , 0 , 0
       0     .12       0  645.25     .07       0 1078.94     .12       0
Bank Sta=645.25,1078.94
Exp/Cntr=.3,.1