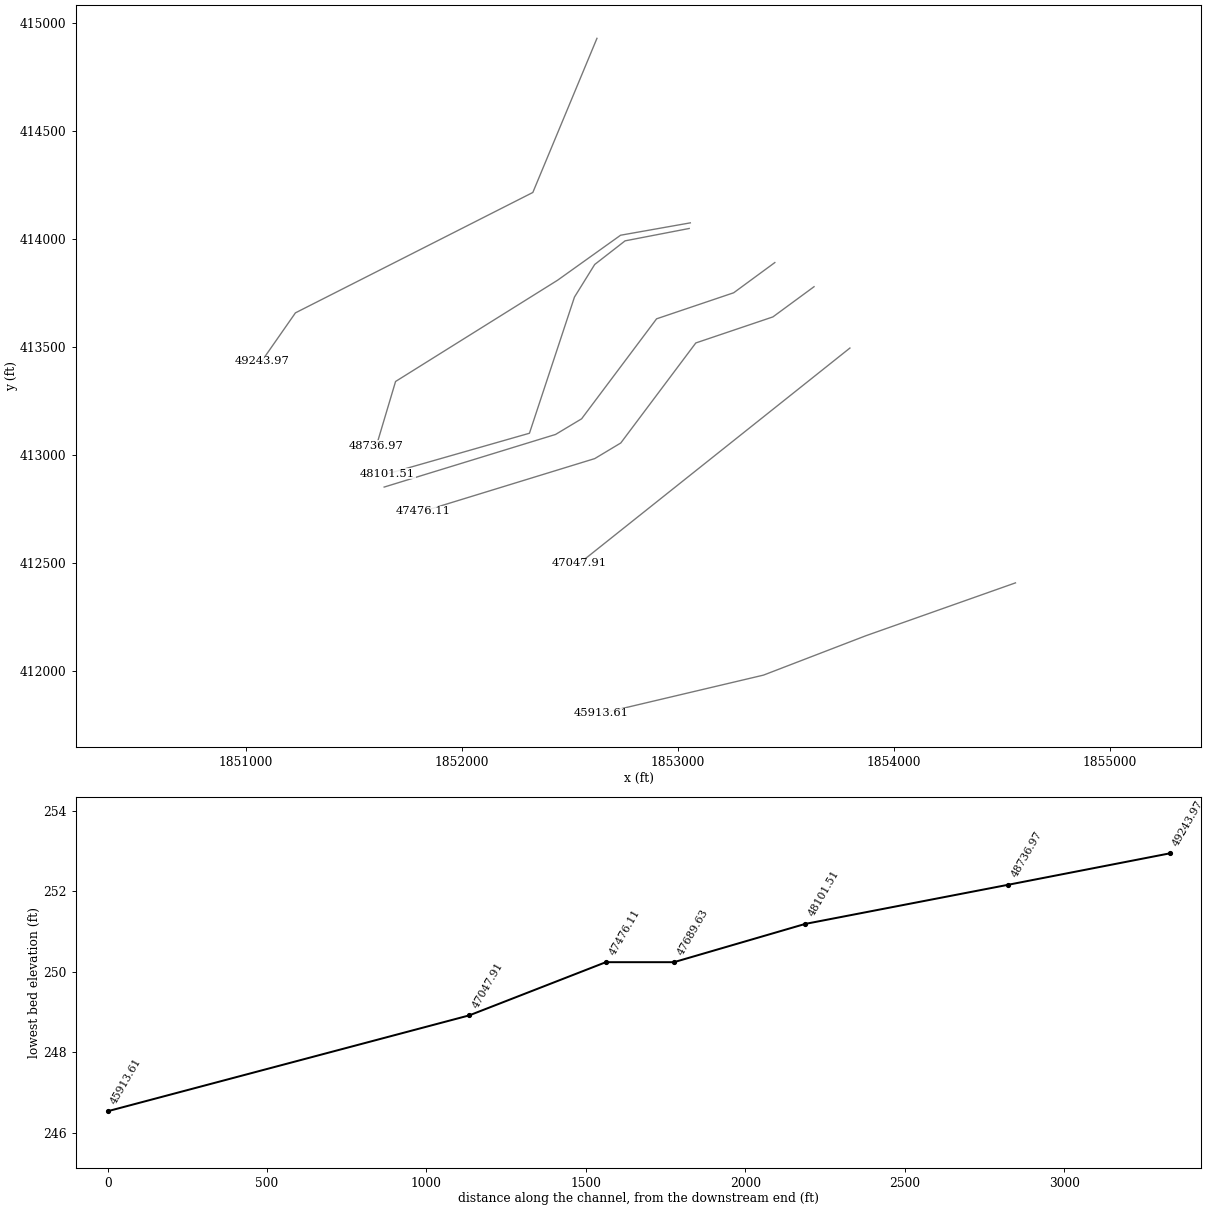
HEC-RAS study jordan.prj: Jordan Creek

--- jordan.g02 (geometry) --- (continued)

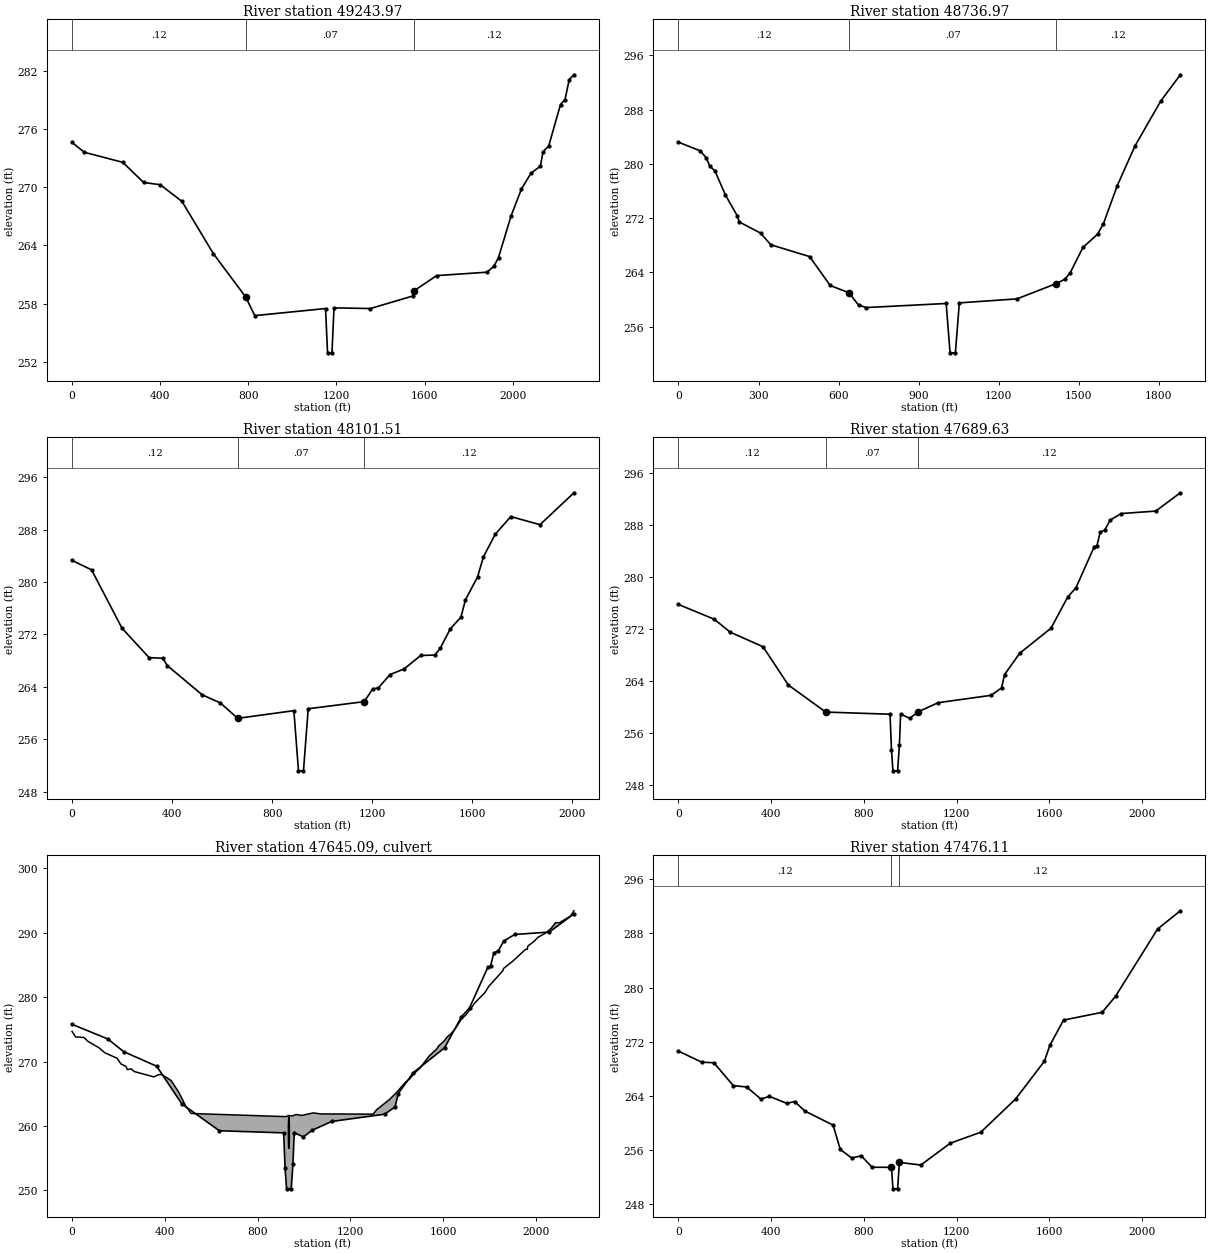
Type RM Length L Ch R = 1 ,49243.97,438.4,507,484.56
XS GIS Cut Line= 4
     1852625.701      414928.713     1852328.826      414215.171
     1851229.867       413657.88     1851073.617      413433.921
#Sta/Elev= 30
       0  274.59   55.78  273.58  230.12  272.55  324.52  270.48  400.43  270.24
  499.15  268.52  641.37  263.15  788.11  258.69  829.33  256.77 1150.64   257.5
 1159.75  252.94 1179.75  252.94 1189.02  257.57 1354.14   257.5 1548.11   258.8
 1551.39  259.31 1654.88  260.89 1883.65  261.24 1914.72  261.85 1935.75  262.75
 1992.31     267 2039.59  269.79 2082.57  271.41 2126.03  272.16 2137.87  273.65
 2163.32  274.21  2217.3   278.5 2237.61  279.01 2256.84  281.06  2278.1  281.56
#Mann= 3 , 0 , 0
       0     .12       0  788.11     .07       0 1551.39     .12       0
Bank Sta=788.11,1551.39
Exp/Cntr=.3,.1

Type RM Length L Ch R = 1 ,48736.97,272.65,635.45,608.5
XS GIS Cut Line= 5
     1853057.992      414074.546     1852735.076      414017.255
     1852443.409      413808.921     1851693.409      413340.171
     1851604.867      413043.296
#Sta/Elev= 30
       0  283.19   81.97  281.91  104.18  280.88  117.01  279.68  136.67  278.96
  175.94  275.41  220.17  272.35  227.79  271.44  307.61   269.8  346.02  268.08
  491.35  266.34  568.58  262.08  639.39     261   674.7  259.19  703.71  258.83
 1003.22  259.43 1017.75  252.16 1037.75  252.16 1052.47  259.52 1268.68  260.11
 1416.11  262.37 1448.17     263 1467.88  263.95 1515.64  267.68 1570.83  269.66
  1592.7  271.21 1643.85  276.74 1709.95  282.58 1807.09  289.24 1880.62  293.12
#Mann= 3 , 0 , 0
       0     .12       0  639.39     .07       0 1416.11     .12       0
Bank Sta=639.39,1416.11
Exp/Cntr=.3,.1

Type RM Length L Ch R = 1 ,48101.51,336.98,411.89,180.76
XS GIS Cut Line= 6
     1853052.784      414048.505     1852755.909      413991.213
     1852615.284      413881.838     1852521.534      413730.796
     1852313.201      413100.588     1851656.951      412913.088
#Sta/Elev= 30
       0  283.29   78.06  281.85  199.53  272.96  308.06  268.46  362.58  268.37
  380.98  267.24  520.23  262.79  593.42  261.54  662.23   259.2  886.97  260.37
  905.32  251.19  925.32  251.19  944.27  260.66 1168.41  261.75 1202.19  263.69
 1224.36  263.82 1271.42  265.88 1327.62  266.73 1393.97  268.79 1450.31  268.85
  1471.8  269.86 1512.25  272.83 1555.21  274.66 1572.82  277.26 1621.62  280.79
 1644.92  283.85 1692.62   287.3 1754.33  289.98 1871.11  288.74 2006.77  293.61
#Mann= 3 , 0 , 0
       0     .12       0  662.23     .07       0 1168.41     .12       0
Bank Sta=662.23,1168.41
Exp/Cntr=.5,.3

Type RM Length L Ch R = 1 ,47689.63,216.42,213.52,361.74
XS GIS Cut Line= 6
     1853449.157      413890.694     1853258.659      413750.835
     1852901.776      413630.267      1852554.54      413167.284
     1852433.971      413094.943     1851640.632      412851.395
#Sta/Elev= 30
       0  275.78  154.79   273.5  222.51  271.54  364.99  269.28  473.65  263.42
  635.41  259.26  912.79  258.93  918.93  253.42  925.28  250.24  945.28  250.24
  953.11  254.15  958.22  258.96  997.82   258.3 1034.65  259.31 1120.09   260.7
  1348.7  261.83 1393.71  262.97 1406.66  265.01 1471.95  268.28 1607.26  272.14
 1679.51  276.94 1714.53  278.33 1793.66  284.64 1805.38  284.81 1819.36  286.86
 1838.81   287.2 1862.47  288.72 1909.65  289.73 2058.95  290.11 2164.99  292.92
#Mann= 3 , 0 , 0
       0     .12       0  635.41     .07       0 1034.65     .12       0
Bank Sta=635.41,1034.65
Exp/Cntr=.5,.3

Type RM Length L Ch R = 2 ,47645.09,,,
BEGIN DESCRIPTION:
SR 1334 DAM
END DESCRIPTION:
Bridge Culvert--1,0,-1,-1, 0
Deck Dist Width WeirC Skew NumUp NumDn MinLoCord MaxHiCord MaxSubmerge Is_Ogee
34,110,2.6,0, 60, 60,261.45,,.95,0,0,0,,
       0   15.17   50.82   68.91  117.41  141.11  194.29   210.7  232.61   238.5
  255.27  268.08  353.11  373.74  387.45  427.22  461.47  490.61  513.83  922.74
   934.1  951.74  966.26  990.83 1040.09 1074.26 1299.14 1313.03 1368.25 1402.67
 1437.45 1458.07 1472.13 1500.25 1540.75  1573.3 1580.66 1608.72 1616.46 1636.03
 1654.48 1681.22  1698.4 1738.94 1781.74 1797.49 1859.53 1861.02 1899.73 1955.69
 1963.75 1966.12 1994.68 2008.96 2045.77  2066.8 2085.95  2102.5 2150.68 2164.99
  274.68  273.82  273.75  273.13  272.11  271.37  270.51  269.64  269.25  268.75
  268.87  268.45  267.62  267.97  267.98  267.06  265.17  263.06  261.94  261.45
  261.62  261.57  261.78  261.64  262.03  261.87  261.84   262.5  264.07  265.31
  266.77  267.35  268.04  268.96  270.87  271.95  272.39  273.33  273.76  274.36
  275.18  276.68  277.22  279.17  280.74  281.67  284.15  284.44  285.54   287.4
  287.42  287.92  288.71  289.27  290.01  290.69  291.57  291.55   292.6  293.41
                                                                                
                                                                                
                                                                                
                                                                                
                                                                                
                                                                                
       0   15.17   50.82   68.91  117.41  141.11  194.29   210.7  232.61   238.5
  255.27  268.08  353.11  373.74  387.45  427.22  461.47  490.61  513.83  922.74
   934.1  951.74  966.26  990.83 1040.09 1074.26 1299.14 1313.03 1368.25 1402.67
 1437.45 1458.07 1472.13 1500.25 1540.75  1573.3 1580.66 1608.72 1616.46 1636.03
 1654.48 1681.22  1698.4 1738.94 1781.74 1797.49 1859.53 1861.02 1899.73 1955.69
 1963.75 1966.12 1994.68 2008.96 2045.77  2066.8 2085.95  2102.5 2150.68 2164.99
  274.68  273.82  273.75  273.13  272.11  271.37  270.51  269.64  269.25  268.75
  268.87  268.45  267.62  267.97  267.98  267.06  265.17  263.06  261.94  261.45
  261.62  261.57  261.78  261.64  262.03  261.87  261.84   262.5  264.07  265.31
  266.77  267.35  268.04  268.96  270.87  271.95  272.39  273.33  273.76  274.36
  275.18  276.68  277.22  279.17  280.74  281.67  284.15  284.44  285.54   287.4
  287.42  287.92  288.71  289.27  290.01  290.69  291.57  291.55   292.6  293.41
                                                                                
                                                                                
                                                                                
                                                                                
                                                                                
                                                                                
Culvert=1,5,,110,.027,.7,1,2,2,256.45,935.28,256.45,935.28,Culvert #1  , 0 ,34
BC Design=,, 0 ,, 0 ,,,,,,

Type RM Length L Ch R = 1 ,47476.11,441.63,428.2,381.81
XS GIS Cut Line= 6
     1853630.658      413778.925      1853440.16      413639.065
     1853083.278      413518.497     1852736.041      413055.515
     1852615.473      412983.174     1851822.133      412739.626
#Sta/Elev= 30
       0   270.6  100.05  268.97  152.68  268.88  236.33   265.5  294.05   265.3
  355.41  263.52   392.6  263.91  467.69  262.87  500.64  263.15  546.07  261.73
  667.15  259.66  697.91  256.07  747.04   254.8  788.52  255.12  835.52  253.43
  918.93  253.42  925.28  250.24  945.28  250.24  953.11  254.15 1045.36  253.76
 1172.73  256.99 1304.11  258.61 1454.18  263.52 1578.81  269.12 1602.04  271.45
 1661.18  275.19 1828.06  276.34 1885.81  278.73 2067.06  288.66 2164.99  291.35
#Mann= 3 , 0 , 0
       0     .12       0  918.93     .07       0  953.11     .12       0
Bank Sta=918.93,953.11
Exp/Cntr=.5,.3

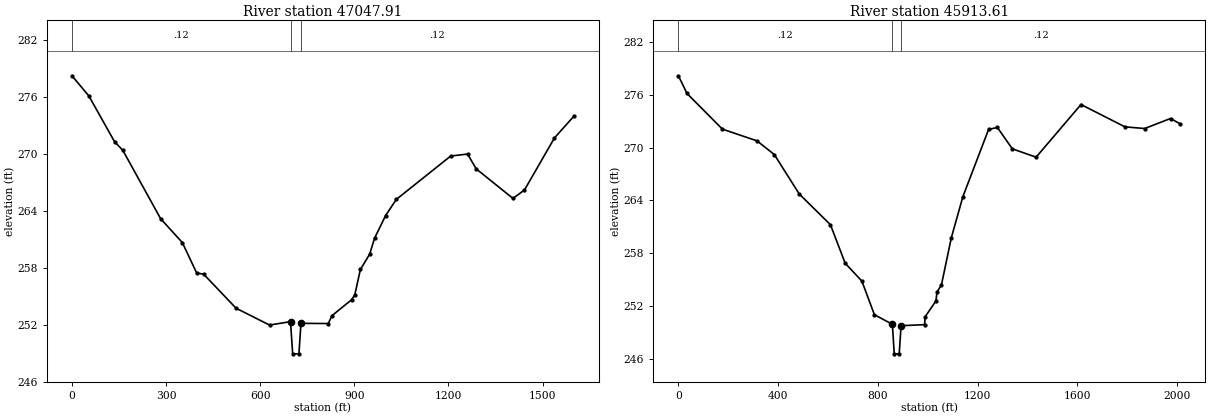
Type RM Length L Ch R = 1 ,47047.91,1122.74,1134.31,1079.26
XS GIS Cut Line= 2
     1853796.782      413495.015     1852545.222      412498.748
#Sta/Elev= 30
       0  278.19   54.07  276.06  135.71  271.25  162.07  270.35  282.72  263.14
  351.66  260.64  397.82  257.41  419.36  257.32  523.14  253.72  629.83  251.95
  696.66  252.31  703.45  248.92  723.45  248.92  729.87  252.13  817.04  252.11
  828.72  252.94  891.09  254.61  901.44  255.12  919.32   257.8  948.74   259.4
  964.36  261.08   999.7  263.48 1033.64  265.17 1207.03  269.74  1260.9  269.95
 1288.53  268.39 1405.64  265.28 1442.35  266.17 1537.91  271.65 1599.67  273.93
#Mann= 3 , 0 , 0
       0     .12       0  696.66     .07       0  729.87     .12       0
Bank Sta=696.66,729.87
Exp/Cntr=.3,.1

Type RM Length L Ch R = 1 ,45913.61,705.66,681.64,637.91
XS GIS Cut Line= 4
     1854563.201       412407.88     1853870.492      412163.088
     1853396.534      411980.796     1852646.534      411803.713
#Sta/Elev= 30
       0  278.17   34.31  276.16  176.47   272.1  314.94  270.77  384.72  269.21
  484.75  264.72  609.73  261.23  668.81  256.85  735.92  254.81  786.07  250.99
  858.21   249.9  865.62  246.54  885.62  246.54  893.03  249.74  987.56  249.86
  989.38  250.75  1032.7  252.55 1037.48  253.59 1055.04  254.39  1094.6  259.74
 1140.96  264.42 1244.18  272.07  1279.3  272.29 1339.35  269.86 1434.66  268.91
 1614.73   274.9 1791.05  272.36 1869.93  272.17 1973.83  273.31 2013.12  272.69
#Mann= 3 , 0 , 0
       0     .12       0  858.21     .07       0  893.03     .12       0
Bank Sta=858.21,893.03
Exp/Cntr=.3,.1