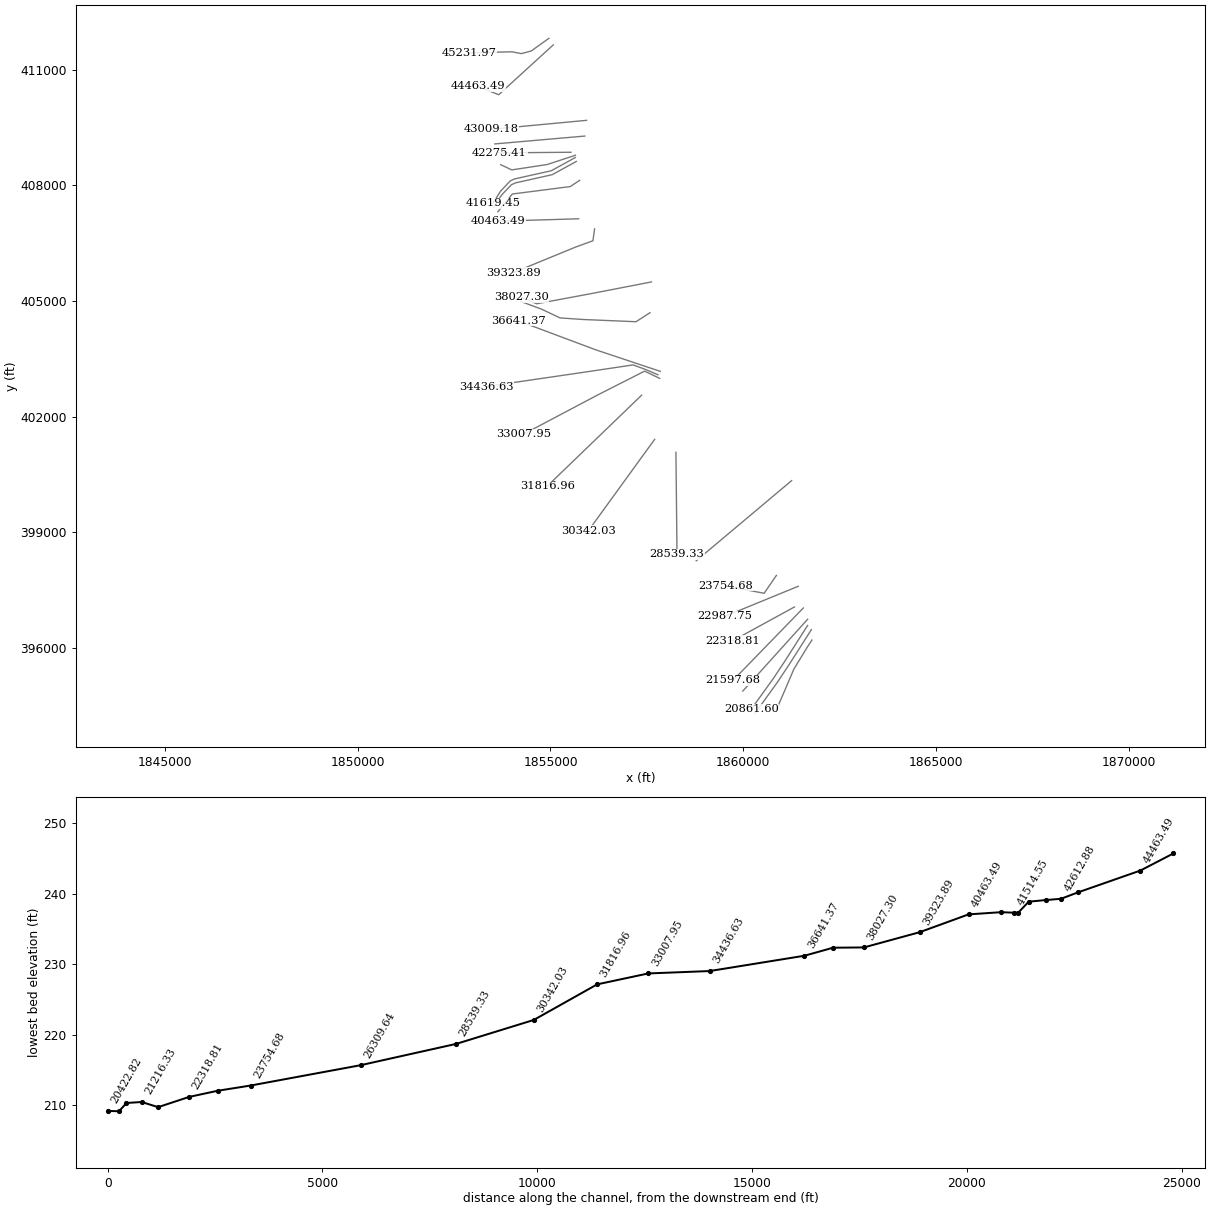
HEC-RAS study jordan.prj: Jordan Creek

--- jordan.g02 (geometry) --- (continued)

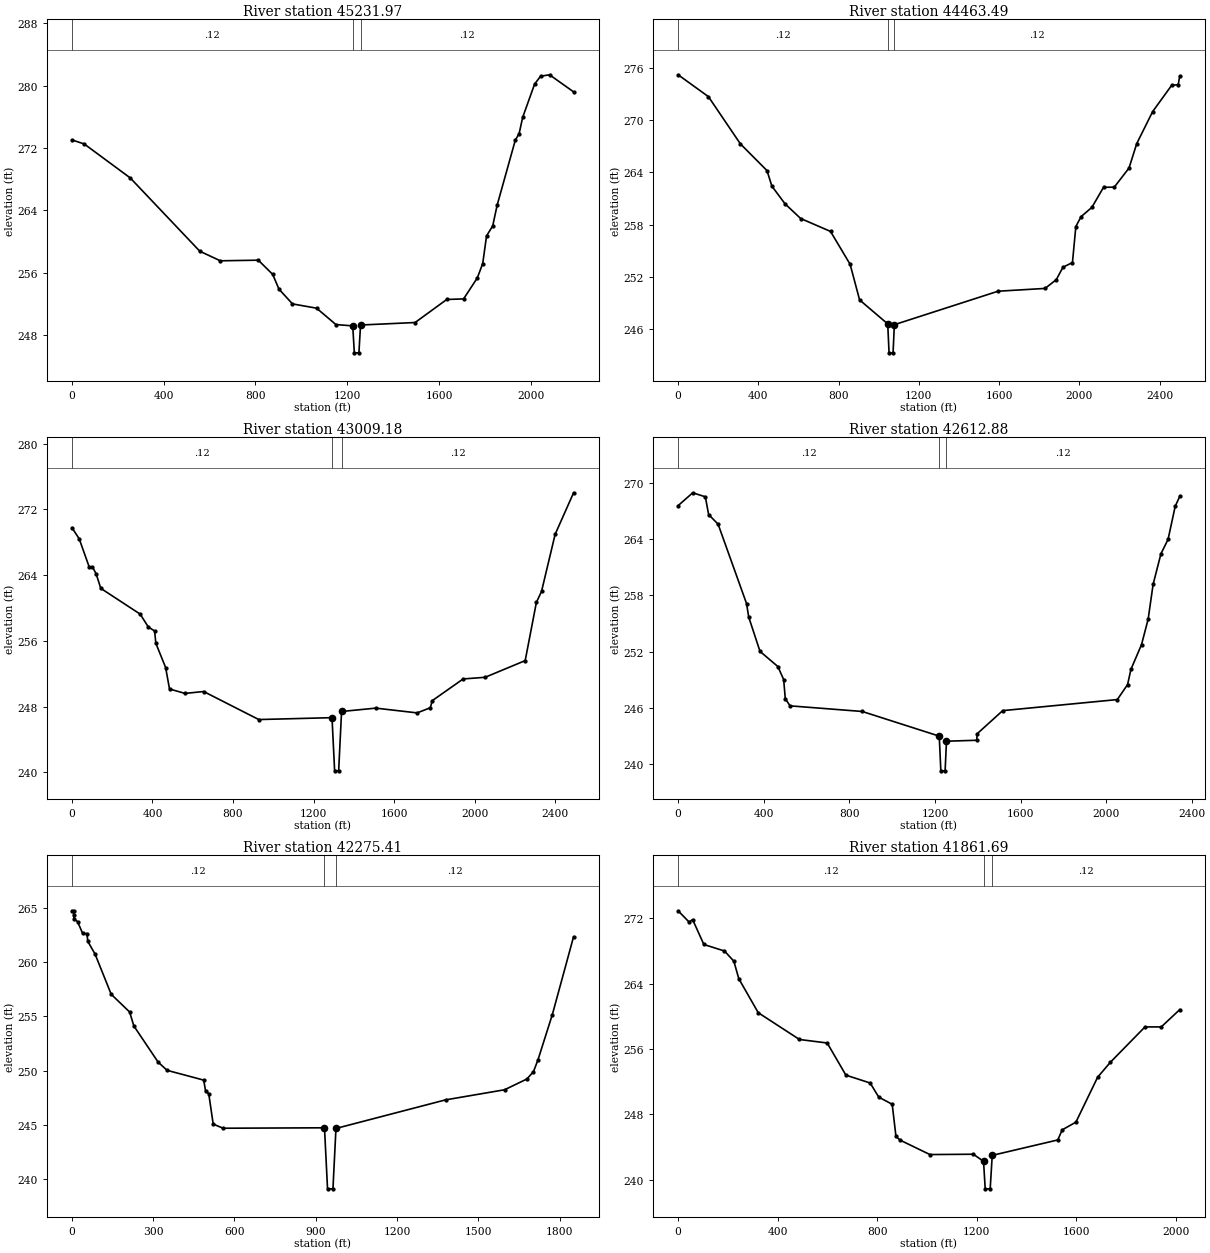
Type RM Length L Ch R = 1 ,45231.97,638.19,768.47,859.39
XS GIS Cut Line= 5
     1854959.034      411808.921     1854500.701      411480.796
     1854245.492      411413.088     1853995.492      411459.963
     1852891.326      411433.921
#Sta/Elev= 30
       0  273.04   53.12  272.53  253.93  268.17  557.25  258.76  646.77  257.53
  812.29  257.61  875.02  255.79   902.5  253.89  961.22     252 1066.31  251.45
 1150.57  249.35 1223.95  249.18 1230.87  245.72 1250.87  245.72    1258  249.29
 1495.77  249.61 1633.81  252.57 1707.12  252.64 1766.88  255.33 1790.51  257.18
 1807.27  260.73 1834.01     262 1853.34  264.66 1932.43     273 1949.18  273.85
 1964.84  275.95 2016.62   280.2 2042.46  281.21 2081.72   281.4 2186.55  279.21
#Mann= 3 , 0 , 0
       0     .12       0 1223.95     .07       0    1258     .12       0
Bank Sta=1223.95,1258
Exp/Cntr=.3,.1

Type RM Length L Ch R = 1 ,44463.49,1469.72,1454.31,1352.06
XS GIS Cut Line= 3
      1855072.47      411639.273     1853655.435       410346.54
     1853115.284       410564.13
#Sta/Elev= 30
       0  275.19  151.14  272.68  310.19  267.27  442.91   264.2   467.5  262.41
  532.71  260.39   610.9   258.7  759.65  257.22  857.32  253.45  904.61  249.36
  1044.8  246.61 1051.44  243.29 1071.44  243.29  1077.9  246.52 1594.81  250.36
 1829.07  250.68  1884.9  251.68 1918.23  253.11 1965.62  253.65 1982.49  257.78
 2008.43  258.91 2062.51  259.98 2120.46  262.28 2174.12   262.3 2247.53  264.49
 2286.11   267.3 2365.43  270.97 2459.81  273.97 2492.77  274.06 2500.44  275.05
#Mann= 3 , 0 , 0
       0     .12       0  1044.8     .07       0  1077.9     .12       0
Bank Sta=1044.8,1077.9
Exp/Cntr=.3,.1

Type RM Length L Ch R = 1 ,43009.18,395.96,396.3,397.06
XS GIS Cut Line= 2
     1855936.546      409683.018     1853456.811      409449.701
#Sta/Elev= 30
       0  269.77   36.11  268.42    86.3  264.95  101.42  265.02  119.94  264.17
  143.33  262.39  338.63  259.26  379.01   257.7  410.52   257.2  416.61  255.71
   465.2  252.76  484.47  250.15  561.36  249.61  653.98  249.84  927.71  246.43
 1291.32  246.66 1304.27  240.19 1324.27  240.19 1338.72  247.41 1508.54  247.82
 1714.02  247.24 1779.64  247.87  1788.6  248.72 1942.44  251.37 2051.34  251.57
 2250.43   253.6  2306.1  260.69 2331.44  262.01 2399.21  268.97 2490.69  274.02
#Mann= 3 , 0 , 0
       0     .12       0 1291.32     .07       0 1338.72     .12       0
Bank Sta=1291.32,1338.72
Exp/Cntr=.3,.1

Type RM Length L Ch R = 1 ,42612.88,339.86,337.46,318.32
XS GIS Cut Line= 2
     1855889.721      409275.085      1853554.72      409070.773
#Sta/Elev= 30
       0  267.56   68.38  268.93  127.18   268.5  142.59  266.61  186.84  265.58
  319.85  257.11  329.88  255.68  382.57  252.02  466.14   250.4  493.27  249.01
   500.7  246.98  523.04  246.21  860.34  245.61 1220.19  242.98 1227.59  239.28
 1247.59  239.28 1253.91  242.44 1395.48  242.54 1397.09  243.23 1516.66   245.7
 2052.24  246.88 2100.14  248.48 2115.66  250.09 2165.29  252.74 2196.32  255.46
  2219.4  259.16 2255.92  262.42 2289.28  263.96 2322.59  267.48 2343.92  268.55
#Mann= 3 , 0 , 0
       0     .12       0 1220.19     .07       0 1253.91     .12       0
Bank Sta=1220.19,1253.91
Exp/Cntr=.3,.1

Type RM Length L Ch R = 1 ,42275.41,386.27,413.73,418.36
XS GIS Cut Line= 2
     1855530.206      408855.117     1853678.434      408839.855
#Sta/Elev= 30
       0  264.71    6.33  264.68    6.45  264.29    7.37  263.95   20.83  263.71
    39.4  262.63   55.44   262.6    58.6  261.89   85.27  260.73  144.96  257.02
  212.97  255.39  228.48  254.11  318.05  250.78   351.3  250.02  486.48  249.12
  493.51  248.09  504.96  247.88  521.51  245.07  557.98  244.69  932.32  244.73
  943.56  239.11  963.56  239.11  974.68  244.67 1379.11   247.3 1596.98  248.23
  1679.4  249.22 1703.82   249.9 1720.47  250.99 1773.53  255.16 1851.84  262.32
#Mann= 3 , 0 , 0
       0     .12       0  932.32     .07       0  974.68     .12       0
Bank Sta=932.32,974.68
Exp/Cntr=.3,.1

Type RM Length L Ch R = 1 ,41861.69,240.36,242.24,261.37
XS GIS Cut Line= 4
     1855646.534      408777.671     1854917.367      408538.088
     1853995.492      408397.463     1853709.034      408532.879
#Sta/Elev= 30
       0  272.94   44.11  271.56   58.35  271.86  103.51  268.81  186.46  268.01
  224.13  266.76  243.95  264.62  322.19  260.45  487.89  257.17  599.44  256.74
  674.66   252.8  772.02  251.84  806.71  250.11  860.76  249.23  875.87   245.3
  893.01  244.83 1012.44  243.07 1187.13  243.11 1228.01  242.24 1234.74  238.87
 1254.74  238.87 1262.94  242.97 1526.42  244.86 1544.39   246.1 1599.38  247.04
 1686.59  252.54    1738  254.38 1877.11  258.71 1942.55  258.71 2016.91  260.83
#Mann= 3 , 0 , 0
       0     .12       0 1228.01     .07       0 1262.94     .12       0
Bank Sta=1228.01,1262.94
Exp/Cntr=.5,.3

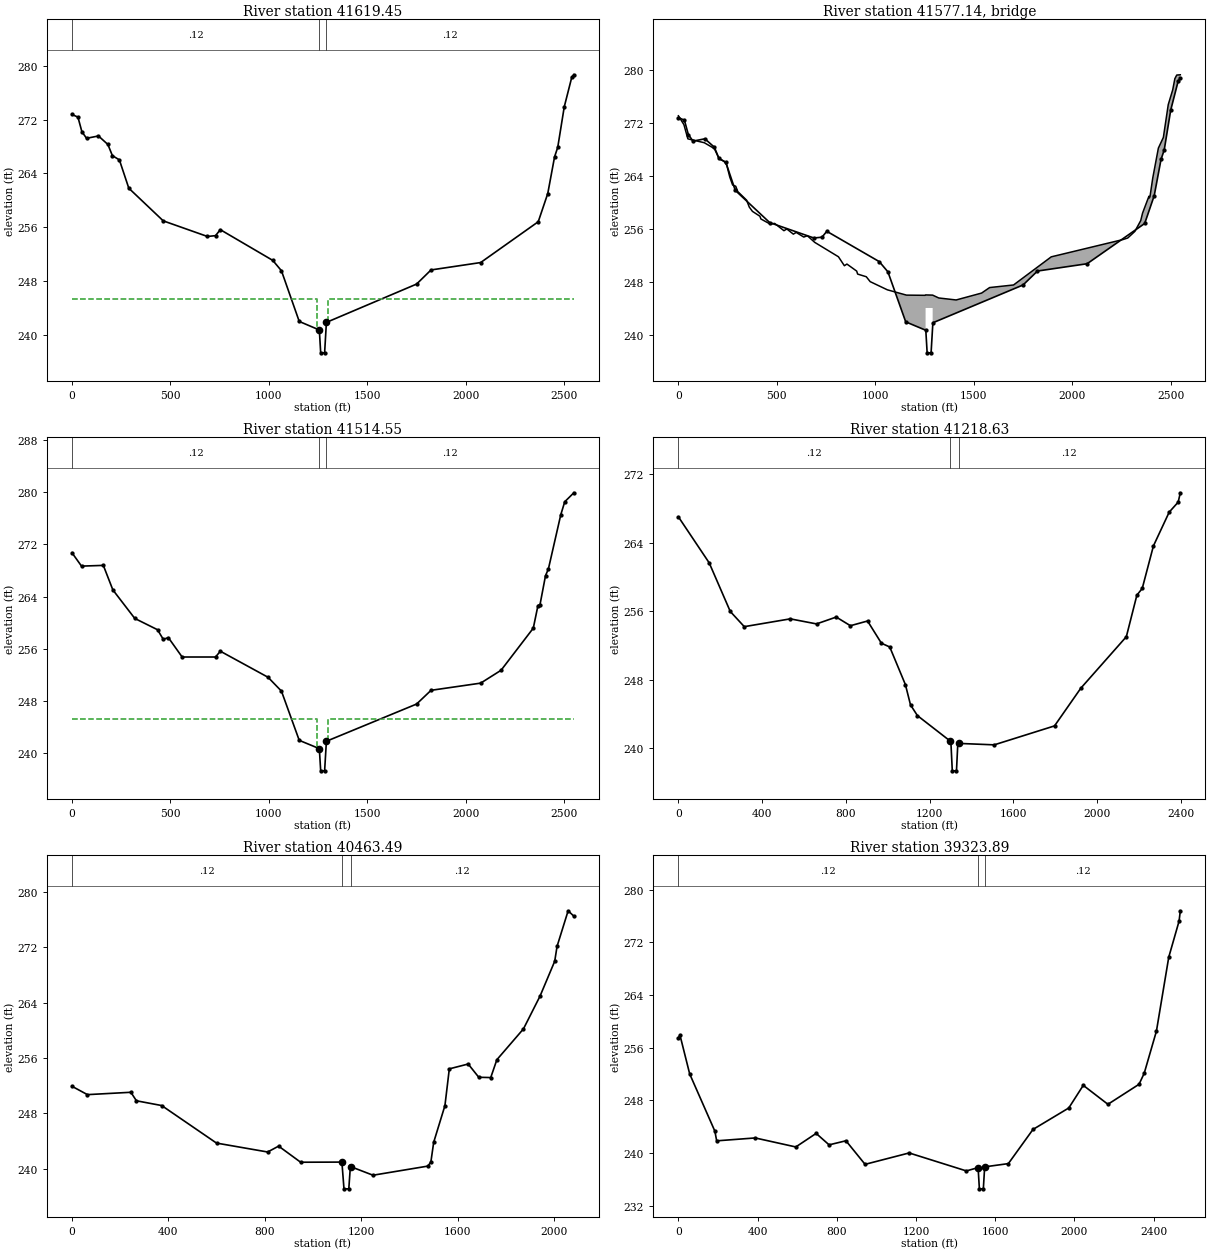
Type RM Length L Ch R = 1 ,41619.45,105.22,104.89,106.17
XS GIS Cut Line= 6
     1855643.839      408718.536     1855019.165      408375.405
     1854064.069      408162.293     1853955.492      408111.258
     1853705.492      407845.633     1853507.575      407533.133
#Sta/Elev= 30
       0  272.77   30.46  272.37   50.51   270.2    74.3  269.22  134.65  269.57
  182.62   268.3  205.46  266.64     241  266.01   288.8   261.8   463.8  256.94
  688.14  254.62  729.39  254.74  753.77  255.63 1020.25  251.06  1064.2  249.52
 1154.62  241.98 1256.74  240.71 1263.54  237.31 1283.54  237.31  1292.6  241.84
 1750.84  247.54 1824.09  249.64 2076.22  250.74 2368.74  256.81 2417.03     261
 2451.66  266.46 2467.87  267.89 2500.88   273.9 2538.94  278.29 2549.64  278.67
#Mann= 3 , 0 , 0
       0     .12       0 1256.74     .07       0  1292.6     .12       0
#XS Ineff= 2 , 0
       0 1245.55  245.28 1301.45       0  245.28
Bank Sta=1256.74,1292.6
Exp/Cntr=.5,.3

Type RM Length L Ch R = 3 ,41577.14,,,
BEGIN DESCRIPTION:
SR 1324 (NCDOT # 11)
END DESCRIPTION:
Bridge Culvert--1,0,-1,-1, 0
Deck Dist Width WeirC Skew NumUp NumDn MinLoCord MaxHiCord MaxSubmerge Is_Ogee
29.66,25.3,2.6,0, 60, 60,245.28,,.95,0,0,0,,
       0   27.97   47.98  131.42  182.43  207.49   231.7  245.73  260.95   275.3
  291.13   301.7  346.44  359.99  376.13  413.98  418.89  466.02  488.69  536.06
  550.81  583.85  598.25  636.85  655.05  692.48  812.91  843.06  856.03  905.59
  910.41   954.3  974.16 1061.24 1158.46 1253.24 1255.55 1291.45 1322.45 1410.84
 1540.21 1580.86 1702.46 1893.92 2257.61 2282.58 2318.87 2348.58 2357.77 2390.16
 2392.24 2395.69 2409.66 2438.13 2463.51 2488.32 2510.88 2521.88 2531.42 2549.64
  273.04   271.7  269.56  268.98   268.1  266.53  266.19  265.59   263.8  262.61
  262.42  261.61  260.32  259.28  258.63   257.9  257.49  256.72  256.82  255.72
  255.98   255.2  255.46  254.76  254.96  253.96  251.79  250.44  250.69  249.63
  249.18  248.78  248.04  246.81  246.01  245.98  246.04  246.01  245.58  245.28
  246.32  247.15  247.54  251.78  254.38  254.62  255.62  257.25  258.37  260.91
  260.65  260.88  263.67  268.17  269.78  274.73  276.94  278.63  279.18  279.22
                                                                                
                                                                                
                                                                                
                                                  244.07  244.07
                                                                                
                                                                                
       0   27.97   47.98  131.42  182.43  207.49   231.7  245.73  260.95   275.3
  291.13   301.7  346.44  359.99  376.13  413.98  418.89  466.02  488.69  536.06
  550.81  583.85  598.25  636.85  655.05  692.48  812.91  843.06  856.03  905.59
  910.41   954.3  974.16 1061.24 1158.46 1253.24 1255.55 1291.45 1322.45 1410.84
 1540.21 1580.86 1702.46 1893.92 2257.61 2282.58 2318.87 2348.58 2357.77 2390.16
 2392.24 2395.69 2409.66 2438.13 2463.51 2488.32 2510.88 2521.88 2531.42 2549.64
  273.04   271.7  269.56  268.98   268.1  266.53  266.19  265.59   263.8  262.61
  262.42  261.61  260.32  259.28  258.63   257.9  257.49  256.72  256.82  255.72
  255.98   255.2  255.46  254.76  254.96  253.96  251.79  250.44  250.69  249.63
  249.18  248.78  248.04  246.81  246.01  245.98  246.04  246.01  245.58  245.28
  246.32  247.15  247.54  251.78  254.38  254.62  255.62  257.25  258.37  260.91
  260.65  260.88  263.67  268.17  269.78  274.73  276.94  278.63  279.18  279.22
                                                                                
                                                                                
                                                                                
                                                  244.07  244.07
                                                                                
                                                                                
BR Coef=-1 , 1 , 0 ,, 0 ,,,.8,0,1.2,0,
WSPro=,,,, 1 ,,,, 0 ,,,, 0 ,,,,-1 ,-1 ,-1 , 0 , 0 , 0 , 0 , 0
BC Design=,, 0 ,, 0 ,,,,,,

Type RM Length L Ch R = 1 ,41514.55,299.99,295.92,273.79
XS GIS Cut Line= 6
     1855669.725      408616.894     1855045.051      408273.763
     1854089.955       408060.65     1853981.378      408009.615
     1853731.378       407743.99     1853533.461       407431.49
#Sta/Elev= 30
       0  270.71    48.6  268.66  159.42  268.77  207.77  265.02  319.12  260.65
  434.63  258.92  463.86  257.45  489.74  257.71  559.83  254.74  729.39  254.74
  753.77  255.63  996.09  251.64  1064.2  249.52 1154.62  241.98 1256.74  240.71
 1263.54  237.31 1283.54  237.31  1292.6  241.84 1750.84  247.54 1824.09  249.64
 2076.22  250.74 2179.84  252.71 2343.59  259.16 2367.28  262.62 2377.67  262.75
 2405.75  267.21 2420.31  268.22 2483.23  276.53 2503.45  278.52 2549.64  279.89
#Mann= 3 , 0 , 0
       0     .12       0 1256.74     .07       0  1292.6     .12       0
#XS Ineff= 2 , 0
       0 1245.55  245.28 1301.45       0  245.28
Bank Sta=1256.74,1292.6
Exp/Cntr=.5,.3

Type RM Length L Ch R = 1 ,41218.63,758.34,755.13,734.23
XS GIS Cut Line= 4
     1855755.909      408126.629     1855511.117      407965.171
     1854011.117      407772.463     1853636.117      407314.129
#Sta/Elev= 30
       0  266.99  147.03  261.63  247.77  255.96   314.7  254.19  534.32   255.1
  659.85  254.51  753.96  255.31  821.73   254.3  903.59  254.85  969.75  252.26
  1009.6  251.82 1084.42  247.43 1108.77  245.07  1141.8  243.82 1298.51  240.85
 1301.51  240.83 1308.41  237.38 1328.41  237.38 1334.86   240.6 1338.31  240.58
 1508.68  240.41 1796.81  242.62 1922.22  247.01 2139.92  253.02  2190.2  257.86
 2215.89  258.65 2269.37  263.61 2344.55  267.54 2387.53  268.71 2397.77   269.8
#Mann= 3 , 0 , 0
       0     .12       0 1298.51     .07       0 1338.31     .12       0
Bank Sta=1298.51,1338.31
Exp/Cntr=.3,.1

Type RM Length L Ch R = 1 ,40463.49,1055.21,1139.6,1136.71
XS GIS Cut Line= 2
     1855730.044      407129.885     1853649.682      407068.092
#Sta/Elev= 30
       0  251.91   64.16   250.7  244.31  251.04  267.34  249.81  372.17  249.12
  599.45  243.69  811.52   242.4  857.06  243.25  948.32  240.92  1119.4  240.94
 1128.06  237.07 1148.06  237.07 1154.54  240.31 1156.72  240.27 1248.47  239.04
  1475.9  240.36 1488.39  240.95 1500.07  243.81 1546.65  249.11 1564.86  254.43
 1643.11  255.13 1686.97  253.21 1736.63  253.17 1762.02  255.75 1872.25  260.21
 1940.83  264.94 2001.92     270 2011.61  272.15 2057.57   277.3 2081.28  276.52
#Mann= 3 , 0 , 0
       0     .12       0  1119.4     .07       0 1156.72     .12       0
Bank Sta=1119.4,1156.72
Exp/Cntr=.3,.1

Type RM Length L Ch R = 1 ,39323.89,1234.54,1296.59,1178.82
XS GIS Cut Line= 4
     1856143.506      406867.261     1856100.165      406559.393
     1855664.511      406401.868     1854035.869      405733.579
#Sta/Elev= 30
       0  257.48    7.71   257.9   56.94  251.99   184.2  243.29  193.21  241.83
  387.84  242.27  592.76   240.9  695.56  242.96  760.91  241.22  846.04  241.84
  942.62  238.26 1165.18  239.99  1454.2  237.26 1510.45  237.74 1513.43  237.75
 1519.85  234.54 1539.85  234.54 1546.53  237.88 1549.25  237.89 1666.14  238.37
 1790.52  243.56 1971.26  246.82 2044.49  250.26 2168.95  247.38  2326.1  250.42
 2352.33   252.1 2413.93  258.49 2476.21  269.73  2528.3   275.2 2534.59  276.77
#Mann= 3 , 0 , 0
       0     .12       0 1510.45     .07       0 1549.25     .12       0
Bank Sta=1510.45,1549.25
Exp/Cntr=.3,.1

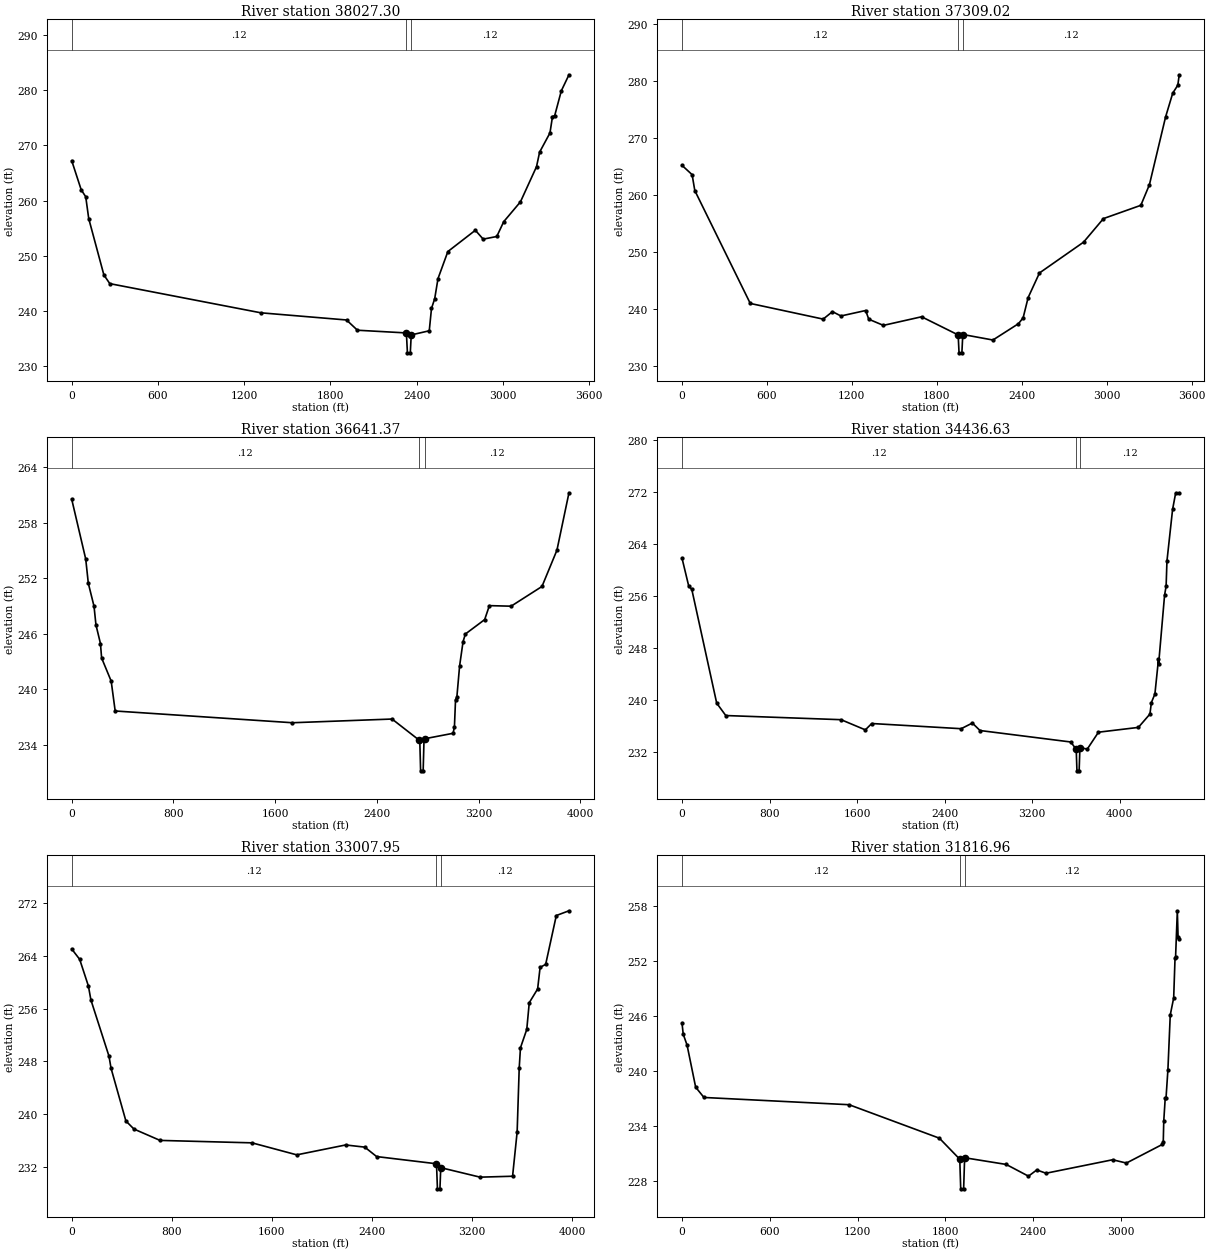
Type RM Length L Ch R = 1 ,38027.30,656.94,718.28,502.28
XS GIS Cut Line= 4
     1857617.465      405492.261     1856059.125      405190.589
     1854643.127      404926.585     1854242.465      405091.219
#Sta/Elev= 30
       0  267.23   65.99  261.95   97.47  260.69  118.38  256.73  223.87  246.51
  265.05  244.93 1316.42  239.64 1912.58  238.34 1988.63  236.48 2329.23  235.99
 2336.45  232.38 2356.45  232.38 2362.94  235.63 2488.42  236.38 2503.99  240.43
 2526.32   242.2 2549.33  245.85 2617.92  250.75 2809.25  254.61 2863.72     253
 2958.31  253.48 3006.75  256.17 3122.95  259.76 3234.88  266.14  3256.5  268.78
  3328.5  272.26  3346.1  275.23 3361.41  275.39 3407.55   279.9 3460.84  282.81
#Mann= 3 , 0 , 0
       0     .12       0 2329.23     .07       0 2362.94     .12       0
Bank Sta=2329.23,2362.94
Exp/Cntr=.3,.1

Type RM Length L Ch R = 1 ,37309.02,637.89,667.65,527.26
XS GIS Cut Line= 6
     1857581.006      404695.386     1857216.423      404461.011
     1855857.048      404518.303     1855247.673      404559.969
     1854763.298      404789.136      1854226.84      404987.053
#Sta/Elev= 30
       0  265.25   71.66  263.61   90.62  260.82  482.42  241.01  997.26  238.26
 1063.14  239.57 1122.87  238.81 1297.65  239.77 1319.39  238.24 1422.84  237.16
 1692.55  238.67 1946.27  235.54 1950.76  235.54 1957.16  232.34 1977.16  232.34
 1983.56  235.54 1988.05  235.54 2196.44  234.59 2376.59  237.45  2409.8  238.48
 2445.22  242.04  2525.3  246.36 2836.51  251.76  2977.1   255.9 3241.25  258.23
 3301.79  261.84 3416.09  273.74 3466.63  277.92 3502.59  279.32 3512.45  281.14
#Mann= 3 , 0 , 0
       0     .12       0 1946.27     .07       0 1988.05     .12       0
Bank Sta=1946.27,1988.05
Exp/Cntr=.3,.1

Type RM Length L Ch R = 1 ,36641.37,1548.57,2204.74,1735.22
XS GIS Cut Line= 3
     1857846.631      403174.553      1856170.23      403733.664
     1854164.099      404485.051
#Sta/Elev= 30
       0  260.56  110.19  254.09  130.42  251.48  175.37  248.99  190.55  246.98
  225.97  244.96  235.03   243.4  310.31   240.9  341.66  237.67 1735.32   236.4
 2518.47   236.8 2730.35  234.53 2736.49  234.47 2743.02   231.2 2763.02   231.2
 2769.83  234.61 2775.68  234.67 2998.66  235.26 3008.96  235.99  3017.6   238.9
 3027.93  239.17 3049.55  242.54  3076.6  245.16 3094.76  245.99 3246.59  247.55
 3283.64  249.06 3454.48     249 3697.03  251.13 3814.69  255.05  3909.4  261.26
#Mann= 3 , 0 , 0
       0     .12       0 2730.35     .07       0 2775.68     .12       0
Bank Sta=2730.35,2775.68
Exp/Cntr=.3,.1

Type RM Length L Ch R = 1 ,34436.63,1301.38,1428.67,1326.39
XS GIS Cut Line= 5
     1857784.131      403086.011     1857482.048      403216.219
     1857142.704      403341.383     1855945.069      403162.486
      1853330.45      402779.859
#Sta/Elev= 30
       0  261.86   61.75  257.53   89.66  257.03   317.4  239.47  400.22  237.56
 1454.04  236.92 1675.62  235.35 1734.11  236.33 2551.46  235.53  2653.6   236.4
 2723.32  235.25 3552.81  233.48 3602.68  232.35 3609.32  229.03 3629.32  229.03
 3636.52  232.63 3703.42  232.38 3806.04  234.99 4170.65  235.73 4276.37  237.79
 4289.48  239.56 4321.72  240.88 4354.43  246.23 4355.67  245.49 4410.04  256.11
 4424.22  257.53 4431.89   261.4 4483.34  269.35 4511.04  271.85 4544.03  271.92
#Mann= 3 , 0 , 0
       0     .12       0 3602.68     .07       0 3636.52     .12       0
Bank Sta=3602.68,3636.52
Exp/Cntr=.3,.1

Type RM Length L Ch R = 1 ,33007.95,1153.81,1191,1247.61
XS GIS Cut Line= 4
     1857831.006      402992.261     1857440.381      403179.761
     1856235.895      402568.317     1854298.055      401543.839
#Sta/Elev= 30
       0  265.04   63.66  263.47  133.39  259.43   153.4  257.32   298.1  248.79
   314.4  246.97  433.29  238.97  497.77  237.75   706.2  236.03 1441.68  235.66
 1799.58  233.84 2190.61  235.34 2343.32  235.01 2438.01  233.58 2916.74  232.49
 2924.34  228.69 2944.34  228.69 2950.76   231.9 3265.32  230.46 3525.12   230.6
  3561.6  237.31 3578.11  246.97  3588.2  250.07 3638.45  252.84  3658.5   256.9
 3725.41  258.98 3745.14  262.25 3789.71  262.71 3874.77  270.11 3976.07  270.83
#Mann= 3 , 0 , 0
       0     .12       0 2916.74     .07       0 2950.76     .12       0
Bank Sta=2916.74,2950.76
Exp/Cntr=.3,.1

Type RM Length L Ch R = 1 ,31816.96,1402.44,1474.93,1440.1
XS GIS Cut Line= 2
     1857361.978      402555.277     1854915.704      400197.701
#Sta/Elev= 30
       0  245.24    8.68  243.99   34.78  242.81   93.54  238.22  150.17   237.1
 1141.85  236.31 1758.79  232.66 1897.99  230.37 1904.45  227.14 1924.45  227.14
 1931.24  230.53 2215.26   229.8 2367.46  228.52 2424.05   229.2 2487.12  228.84
 2942.42  230.31 3036.45  229.95 3283.03  231.99 3288.31  232.23 3291.69  234.52
 3301.69  237.01 3307.06  237.02 3320.05   240.1 3336.07  246.09 3359.49  247.95
 3368.68  252.25 3372.61  252.46 3384.45  257.45 3389.65  254.55 3397.42  254.38
#Mann= 3 , 0 , 0
       0     .12       0 1897.99     .07       0 1931.24     .12       0
Bank Sta=1897.99,1931.24
Exp/Cntr=.3,.1

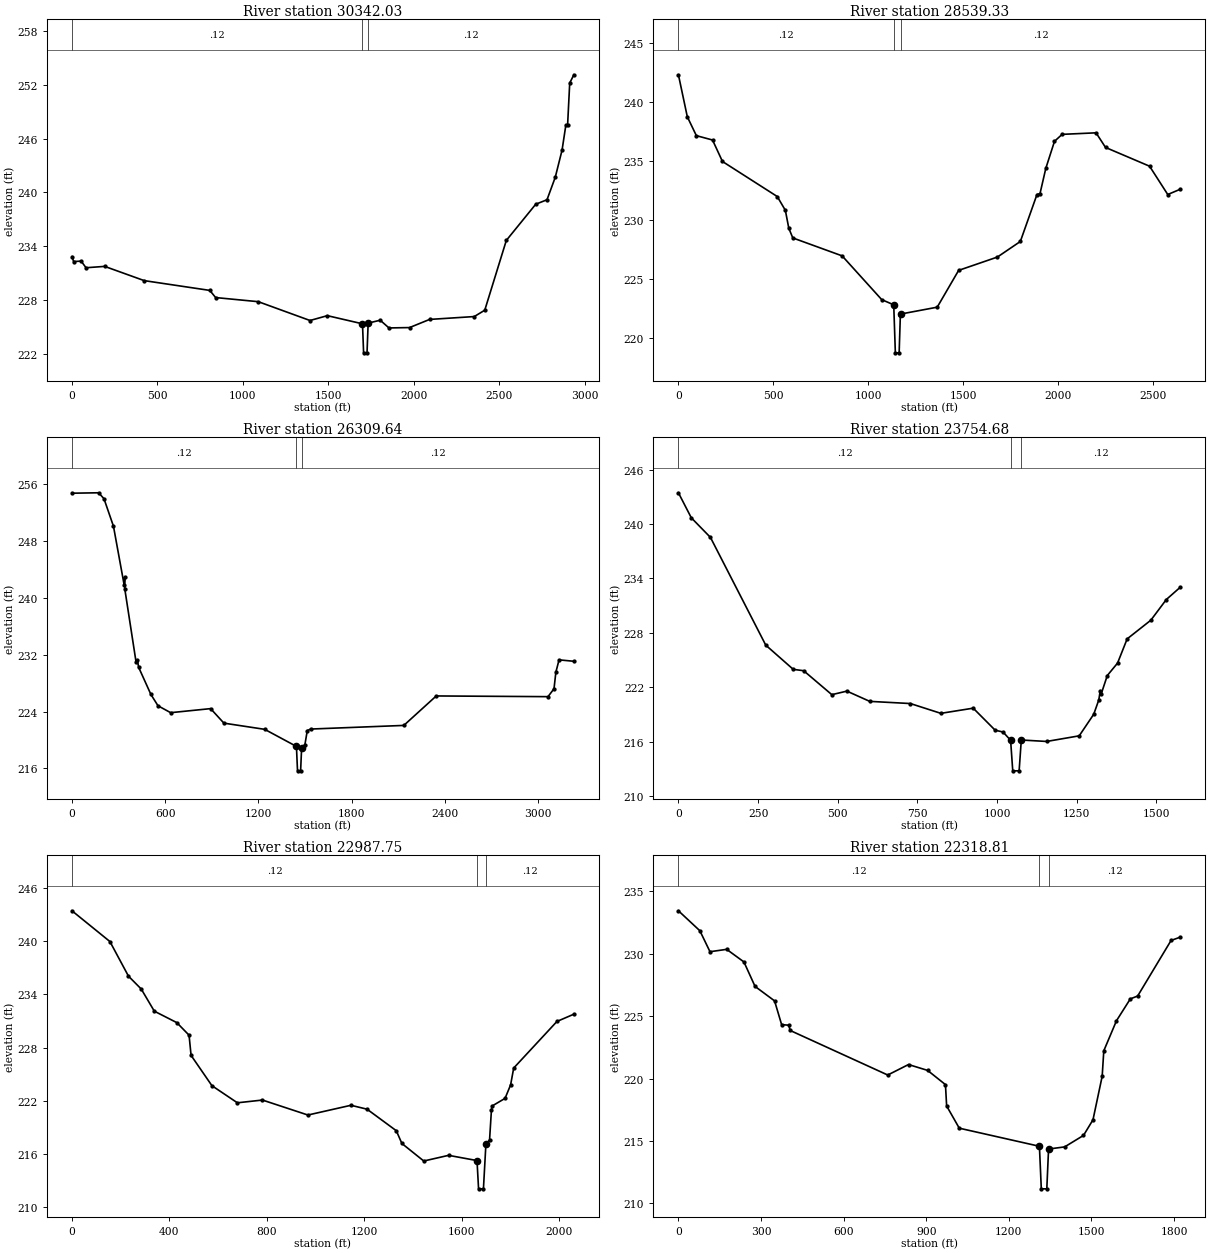
Type RM Length L Ch R = 1 ,30342.03,1689.44,1802.7,1883.99
XS GIS Cut Line= 2
      1857700.58      401410.734     1855977.087      399033.784
#Sta/Elev= 30
       0  232.83     9.9  232.28   53.79  232.33   82.24  231.59  191.43  231.74
  422.99  230.15  806.27  229.06  840.59  228.26  1090.1   227.8 1392.57   225.7
 1494.02  226.24 1699.62  225.33 1706.11  222.09 1726.11  222.09 1732.76  225.41
 1803.27  225.73  1854.5  224.87 1974.83  224.91  2092.2  225.82 2353.51  226.14
 2414.87  226.85 2540.98  234.64 2713.05  238.68 2779.01  239.18 2827.31  241.69
 2867.06  244.72 2889.45  247.54 2899.37  247.49 2911.83  252.21 2936.04  253.13
#Mann= 3 , 0 , 0
       0     .12       0 1699.62     .07       0 1732.76     .12       0
Bank Sta=1699.62,1732.76
Exp/Cntr=.3,.1

Type RM Length L Ch R = 1 ,28539.33,2048.74,2229.69,1968.02
XS GIS Cut Line= 2
     1858252.397      401074.821     1858280.523      398429.336
#Sta/Elev= 30
       0  242.27   46.89  238.71   94.59  237.11  179.91  236.74  232.22  234.92
     521  231.95  563.73  230.78  581.87  229.26  602.92  228.44  862.94  226.92
 1071.67  223.21 1134.98  222.77  1143.5   218.7  1163.5   218.7 1169.93  221.91
 1172.02  221.99 1364.18  222.57 1477.07  225.69 1681.46  226.82 1802.35  228.14
 1890.02  232.12 1906.05   232.2  1936.6  234.34 1982.38  236.63 2022.56  237.22
 2201.45  237.35 2251.42  236.11 2483.56  234.52 2579.41  232.12 2645.63  232.57
#Mann= 3 , 0 , 0
       0     .12       0 1134.98     .07       0 1172.02     .12       0
Bank Sta=1134.98,1172.02
Exp/Cntr=.3,.1

Type RM Length L Ch R = 1 ,26309.64,2020.86,2554.96,1924.11
XS GIS Cut Line= 2
     1861251.975      400340.486     1858778.923      398263.094
#Sta/Elev= 30
       0  254.67  171.55  254.73  206.06   253.9  267.14  250.03  335.76  241.81
  339.37  242.85  340.32  241.18  412.72  230.93  421.07   231.2  429.23  230.21
  508.12   226.4  553.73  224.81  635.18  223.84  892.32  224.41  977.81  222.37
 1240.31   221.5 1444.61   219.1 1451.48  215.67 1471.48  215.67 1478.01  218.93
 1499.03  219.34 1514.31  221.32 1535.92  221.54 2135.56  222.05  2344.3  226.19
 3063.43  226.09 3102.07   227.2 3114.06  229.53 3134.52  231.26 3229.79  231.06
#Mann= 3 , 0 , 0
       0     .12       0 1444.61     .07       0 1478.01     .12       0
Bank Sta=1444.61,1478.01
Exp/Cntr=.3,.1

Type RM Length L Ch R = 1 ,23754.68,495.45,766.93,611.58
XS GIS Cut Line= 3
     1860857.048      397882.886      1860539.34      397419.344
     1859544.548      397612.053
#Sta/Elev= 30
       0  243.45   40.47  240.69  100.51  238.53  274.13  226.65  360.44  223.98
  393.07  223.83  481.49  221.19  528.77  221.58   600.5  220.45  728.05  220.21
  823.67  219.13  925.24   219.7  994.13  217.27  1018.9  217.07  1042.6  216.16
 1049.35  212.79 1069.35  212.79 1076.15  216.19 1155.61  216.03 1257.93  216.65
 1303.52  219.03  1319.4  220.61 1323.98  221.64 1326.39  221.21 1346.12   223.3
 1378.25  224.67 1408.39  227.34 1482.75   229.4 1531.36  231.68 1575.26  233.04
#Mann= 3 , 0 , 0
       0     .12       0  1042.6     .07       0 1076.15     .12       0
Bank Sta=1042.6,1076.15
Exp/Cntr=.3,.1

Type RM Length L Ch R = 1 ,22987.75,599.82,668.94,619.75
XS GIS Cut Line= 2
     1861424.756      397601.636     1859518.506      396820.386
#Sta/Elev= 30
       0  243.43  155.76  239.96  232.05  236.05   284.4   234.6  338.08   232.1
  430.29  230.81  480.71  229.39  488.97  227.11  574.58  223.69  679.06  221.76
  782.02  222.07  968.53  220.38 1145.23  221.48 1211.18  221.04 1331.28  218.61
 1354.26  217.17 1444.06  215.19 1545.91  215.83 1662.63  215.24 1669.01  212.05
 1689.01  212.05 1699.06  217.07 1714.15  217.57 1721.93  220.99 1725.31  221.41
 1777.72  222.26 1800.52  223.78 1813.18  225.68 1990.71  230.94 2060.13  231.76
#Mann= 3 , 0 , 0
       0     .12       0 1662.63     .07       0 1699.06     .12       0
Bank Sta=1662.63,1699.06
Exp/Cntr=.3,.1

Type RM Length L Ch R = 1 ,22318.81,589.84,721.13,658.69
XS GIS Cut Line= 2
     1861325.798      397065.178      1859726.84      396190.178
#Sta/Elev= 30
       0  233.45   77.89  231.85  114.66  230.17  175.28  230.36  237.93  229.35
  278.29  227.39  349.22  226.23  374.78  224.33  400.79  224.28  405.84  223.86
   760.2  220.29  835.62  221.13  904.97  220.66   969.8  219.52  974.06  217.81
 1019.96  216.03 1311.03  214.58 1317.85  211.17 1337.85  211.17 1344.24  214.36
 1402.59  214.53 1471.08  215.45 1505.53   216.7 1538.95  220.19 1544.79  222.23
 1590.87  224.64 1641.12  226.39 1667.78  226.62 1789.06  231.07 1822.72  231.34
#Mann= 3 , 0 , 0
       0     .12       0 1311.03     .07       0 1344.24     .12       0
Bank Sta=1311.03,1344.24
Exp/Cntr=.3,.1

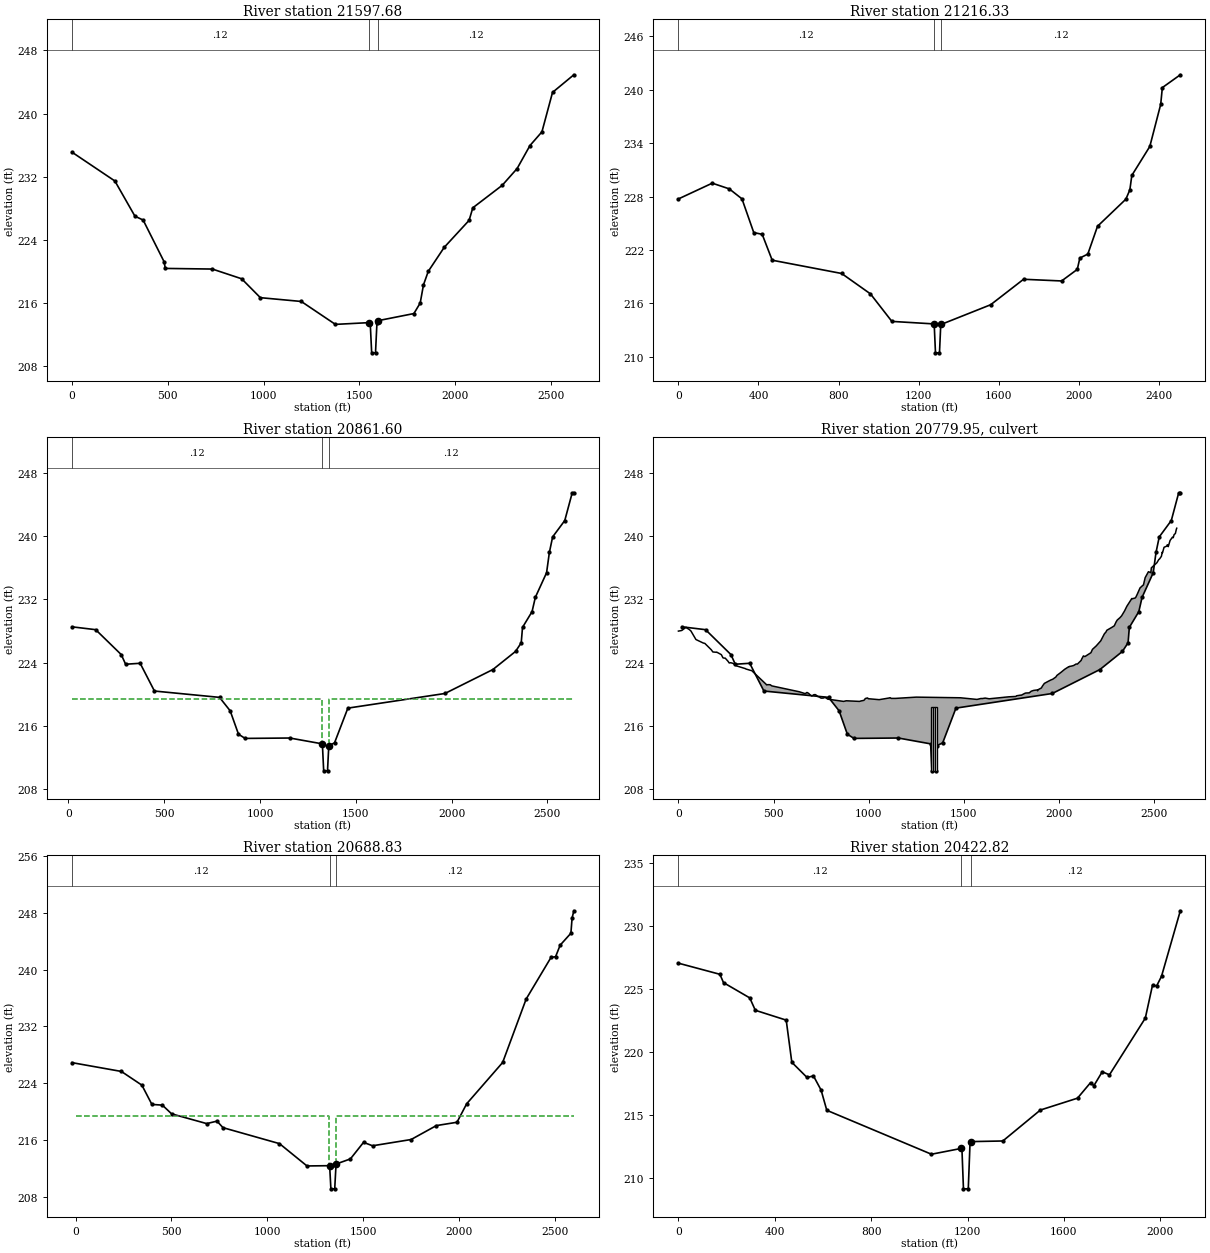
Type RM Length L Ch R = 1 ,21597.68,356.74,381.35,391.7
XS GIS Cut Line= 2
     1861555.986      397039.143     1859730.344      395159.805
#Sta/Elev= 30
       0  235.11  224.17  231.46  328.76  227.01  371.63  226.52  480.93  221.25
  487.39   220.4  733.03  220.32  885.88  219.09  983.56   216.7 1197.19  216.22
 1375.27  213.32 1549.25  213.54 1557.41  213.33 1564.63  209.72 1584.63  209.72
 1592.28  213.55    1600   213.8 1785.07  214.69 1817.95  216.02 1835.07  218.32
  1860.1  220.03 1943.48  223.07 2073.21  226.48 2092.65  228.07 2245.92  230.91
 2323.99  233.04 2391.09  235.95 2453.42  237.68 2508.73  242.67 2620.09   244.9
#Mann= 3 , 0 , 0
       0     .12       0 1549.25     .07       0    1600     .12       0
Bank Sta=1549.25,1600
Exp/Cntr=.3,.1

Type RM Length L Ch R = 1 ,21216.33,337.09,354.73,360.32
XS GIS Cut Line= 2
     1861667.328      396746.496     1859987.729      394885.319
#Sta/Elev= 30
       0  227.73  169.06   229.5  254.01  228.86  317.43  227.74  376.39  223.95
  418.42  223.76  468.42  220.85  815.27  219.36  959.23  217.07 1066.15  213.98
 1274.63   213.7 1277.54   213.7 1284.03  210.45 1304.03  210.45 1310.44  213.65
 1313.43  213.65 1559.61  215.85 1723.97  218.71 1914.01  218.52 1992.35  219.82
 2005.07  221.09 2044.99  221.54 2093.38  224.66 2234.89   227.7 2254.94  228.75
 2264.79  230.37 2354.61  233.62 2409.01  238.35  2417.2  240.23    2507  241.67
#Mann= 3 , 0 , 0
       0     .12       0 1274.63     .07       0 1313.43     .12       0
Bank Sta=1274.63,1313.43
Exp/Cntr=.5,.3

Type RM Length L Ch R = 1 ,20861.60,163.2,172.77,156.81
XS GIS Cut Line= 4
     1861666.332      396585.059     1861084.307      395671.693
     1860780.515      395213.962     1860203.932      394413.273
#Sta/Elev= 30
    18.8  228.52  142.54  228.16  275.99  225.01  298.83  223.79  374.67  223.91
  449.28   220.4  788.85   219.6  844.48   217.9  887.89  214.94  922.62  214.41
 1155.51  214.46 1325.61  213.72 1332.42  210.31 1352.42  210.31  1359.1  213.51
 1388.88  213.84 1458.61  218.24 1965.03  220.09 2215.41  223.12 2333.62  225.41
 2363.31   226.5 2370.01  228.45 2419.75  230.44 2436.95  232.25 2495.56  235.36
 2510.09  237.92 2527.15  239.89 2590.49  241.96 2629.06  245.44  2637.9  245.47
#Mann= 3 , 0 , 0
    18.8     .12       0 1325.61     .07       0  1359.1     .12       0
#XS Ineff= 2 , 0
       0 1323.92  219.34 1360.92       0  219.34
Bank Sta=1325.61,1359.1
Exp/Cntr=.5,.3

Type RM Length L Ch R = 2 ,20779.95,,,
BEGIN DESCRIPTION:
NC 144 / SR 1319 (NCDOT # 106)
END DESCRIPTION:
Bridge Culvert--1,0,-1,-1, 0
Deck Dist Width WeirC Skew NumUp NumDn MinLoCord MaxHiCord MaxSubmerge Is_Ogee
59.15,45,2.6,0,193,193,219.34,,.95,0,0,0,,
       0   17.56   17.65   17.79    40.3   41.79   57.64   64.97   65.86   72.08
   90.27   91.89   94.11  129.77  139.06  149.19  161.34  164.48  173.02  179.53
  181.08  196.04  199.49  200.03  201.42  225.32  225.58  225.69   234.2  239.26
  246.38  249.02   260.9  266.92  275.16  284.12  290.19  300.78  306.77  352.57
   353.9  354.48  379.55  384.52  431.89  460.83  463.29  470.71  482.07  487.56
  491.27  635.16  663.36  666.44  675.68  684.12  691.51  701.01  712.18  716.93
  719.04   724.7  732.51   741.9  746.38  752.28  762.87  769.98  781.61  783.62
  867.93  871.39  882.18  951.74  959.88   974.3   978.8  981.92  993.98  997.99
 1055.14 1109.23 1112.14 1119.12  1135.8 1140.98 1249.69 1458.41 1469.56 1481.59
  1569.3 1579.02 1590.37 1596.53 1612.22 1633.34 1702.61 1726.31 1736.21 1774.04
 1777.16 1797.81 1802.66 1820.75 1825.53 1843.86 1854.43 1867.06 1885.67 1887.91
 1890.44 1907.61 1913.55 1923.44 1936.76 1945.96 1960.05 1966.44 1983.51 1989.48
 2012.04 2030.05 2050.23 2052.67  2054.9 2064.65 2077.15 2090.18 2097.03 2116.51
 2119.29 2128.51 2136.46 2168.15 2176.06 2179.27  2192.5 2195.21 2195.43 2195.58
 2217.45 2219.69 2227.18 2238.81 2247.26 2251.42 2279.92 2290.82 2300.55 2306.42
 2320.71 2329.26 2343.57 2343.98 2344.76 2356.82 2382.92 2384.97  2400.2 2404.45
 2412.45 2425.01 2426.15  2439.2 2444.29 2444.88 2453.13  2464.6 2465.19 2465.73
 2470.27 2482.88 2485.58 2502.35 2505.17 2514.65 2524.44 2529.13 2538.58  2542.8
 2544.27 2552.43 2565.34 2569.84  2574.4 2584.11 2588.64 2596.36 2600.66  2605.2
 2611.96 2616.98  2619.1
  227.98  228.06  228.06  228.06  228.47  228.41  228.17     228  227.99  227.73
  226.96  226.92  226.89  226.48  226.42  226.18  225.89  225.81  225.61  225.41
  225.34  225.31  225.28  225.29  225.32  225.01     225     225   224.6  224.57
  224.56  224.48  224.16  223.95  223.98  223.92  223.86  223.65  223.57  223.23
  223.19  223.19  223.01     223  221.92  221.26  221.18  221.21   221.2   221.1
  221.05  220.31  220.09  220.07  220.22  220.11  219.93  219.77  219.94  219.95
  219.95  219.87  219.71  219.64  219.54   219.5  219.52   219.6  219.44  219.38
  219.09  219.11  219.17  219.09  219.15  219.22  219.32  219.45  219.53  219.43
  219.31  219.53  219.56  219.47  219.46  219.47  219.63  219.56  219.56  219.55
  219.34   219.4  219.46  219.45  219.51  219.42  219.59  219.64  219.67  219.72
   219.8  219.88  219.88  220.11  220.15  220.17  220.38  220.48  220.54  220.43
  220.57  220.79  221.04  221.37  221.55  221.66  221.83  221.88  222.17  222.38
  222.79  223.15  223.46  223.45  223.51  223.55  223.63  223.82  223.81  224.27
  224.43  224.84  224.76  225.25  225.67  225.74  226.04  226.09  226.09   226.1
  226.69  226.75  227.11  227.64  227.87  228.08  228.48  228.65  229.15  229.38
  229.68  229.91  230.46  230.48  230.53  231.12   232.1  232.07  232.16  232.28
  232.69   233.4  233.44  233.73  233.82  233.89  234.74  235.26   235.3  235.32
  235.49  235.37  235.98  236.35  236.41  236.62  237.02  237.11  237.44  237.96
  237.88  238.58  238.71   238.9  238.66  239.44  239.59  239.85  239.79  240.18
  240.32  240.85  240.99
                                                                                
                                                                                
                                                                                
                                                                                
                                                                                
                                                                                
                                                                                
                                                                                
                                                                                
                                                                                
                                                                                
                                                                                
                                                                                
                                                                                
                                                                                
                                                                                
                                                                                
                                                                                
                                                                                
                        
       0   17.56   17.65   17.79    40.3   41.79   57.64   64.97   65.86   72.08
   90.27   91.89   94.11  129.77  139.06  149.19  161.34  164.48  173.02  179.53
  181.08  196.04  199.49  200.03  201.42  225.32  225.58  225.69   234.2  239.26
  246.38  249.02   260.9  266.92  275.16  284.12  290.19  300.78  306.77  352.57
   353.9  354.48  379.55  384.52  431.89  460.83  463.29  470.71  482.07  487.56
  491.27  635.16  663.36  666.44  675.68  684.12  691.51  701.01  712.18  716.93
  719.04   724.7  732.51   741.9  746.38  752.28  762.87  769.98  781.61  783.62
  867.93  871.39  882.18  951.74  959.88   974.3   978.8  981.92  993.98  997.99
 1055.14 1109.23 1112.14 1119.12  1135.8 1140.98 1249.69 1458.41 1469.56 1481.59
  1569.3 1579.02 1590.37 1596.53 1612.22 1633.34 1702.61 1726.31 1736.21 1774.04
 1777.16 1797.81 1802.66 1820.75 1825.53 1843.86 1854.43 1867.06 1885.67 1887.91
 1890.44 1907.61 1913.55 1923.44 1936.76 1945.96 1960.05 1966.44 1983.51 1989.48
 2012.04 2030.05 2050.23 2052.67  2054.9 2064.65 2077.15 2090.18 2097.03 2116.51
 2119.29 2128.51 2136.46 2168.15 2176.06 2179.27  2192.5 2195.21 2195.43 2195.58
 2217.45 2219.69 2227.18 2238.81 2247.26 2251.42 2279.92 2290.82 2300.55 2306.42
 2320.71 2329.26 2343.57 2343.98 2344.76 2356.82 2382.92 2384.97  2400.2 2404.45
 2412.45 2425.01 2426.15  2439.2 2444.29 2444.88 2453.13  2464.6 2465.19 2465.73
 2470.27 2482.88 2485.58 2502.35 2505.17 2514.65 2524.44 2529.13 2538.58  2542.8
 2544.27 2552.43 2565.34 2569.84  2574.4 2584.11 2588.64 2596.36 2600.66  2605.2
 2611.96 2616.98  2619.1
  227.98  228.06  228.06  228.06  228.47  228.41  228.17     228  227.99  227.73
  226.96  226.92  226.89  226.48  226.42  226.18  225.89  225.81  225.61  225.41
  225.34  225.31  225.28  225.29  225.32  225.01     225     225   224.6  224.57
  224.56  224.48  224.16  223.95  223.98  223.92  223.86  223.65  223.57  223.23
  223.19  223.19  223.01     223  221.92  221.26  221.18  221.21   221.2   221.1
  221.05  220.31  220.09  220.07  220.22  220.11  219.93  219.77  219.94  219.95
  219.95  219.87  219.71  219.64  219.54   219.5  219.52   219.6  219.44  219.38
  219.09  219.11  219.17  219.09  219.15  219.22  219.32  219.45  219.53  219.43
  219.31  219.53  219.56  219.47  219.46  219.47  219.63  219.56  219.56  219.55
  219.34   219.4  219.46  219.45  219.51  219.42  219.59  219.64  219.67  219.72
   219.8  219.88  219.88  220.11  220.15  220.17  220.38  220.48  220.54  220.43
  220.57  220.79  221.04  221.37  221.55  221.66  221.83  221.88  222.17  222.38
  222.79  223.15  223.46  223.45  223.51  223.55  223.63  223.82  223.81  224.27
  224.43  224.84  224.76  225.25  225.67  225.74  226.04  226.09  226.09   226.1
  226.69  226.75  227.11  227.64  227.87  228.08  228.48  228.65  229.15  229.38
  229.68  229.91  230.46  230.48  230.53  231.12   232.1  232.07  232.16  232.28
  232.69   233.4  233.44  233.73  233.82  233.89  234.74  235.26   235.3  235.32
  235.49  235.37  235.98  236.35  236.41  236.62  237.02  237.11  237.44  237.96
  237.88  238.58  238.71   238.9  238.66  239.44  239.59  239.85  239.79  240.18
  240.32  240.85  240.99
                                                                                
                                                                                
                                                                                
                                                                                
                                                                                
                                                                                
                                                                                
                                                                                
                                                                                
                                                                                
                                                                                
                                                                                
                                                                                
                                                                                
                                                                                
                                                                                
                                                                                
                                                                                
                                                                                
                        
Multiple Barrel Culv=2,8,9,45,.012,.4,1,8,1,210.34,210.34, 3,Culvert #1  , 0 ,59.15
 1332.42 1332.42 1342.42 1342.42 1352.42 1352.42
BC Design=,, 0 ,, 0 ,,,,,,

Type RM Length L Ch R = 1 ,20688.83,211.44,266.01,254.67
XS GIS Cut Line= 4
      1861764.92      396477.668     1861182.895      395564.302
     1860879.104      395106.571      1860302.52      394305.882
#Sta/Elev= 30
   -18.8   226.9  239.12  225.66  346.15  223.73  398.36  221.02     453  220.92
  501.45  219.69  684.45  218.32  738.13  218.67  769.31  217.75 1064.25   215.5
 1207.68  212.36 1325.91   212.4 1332.42  209.14 1352.42  209.14 1359.39  212.63
  1434.2  213.35  1502.8  215.68 1549.91   215.2 1751.12  216.08 1882.77  218.04
 1990.52  218.51 2040.99  221.11 2228.68  226.92 2351.39  235.85 2480.97   241.7
    2505  241.81 2528.81  243.43 2584.91  245.11 2591.08  247.25  2600.3  248.27
#Mann= 3 , 0 , 0
   -18.8     .12       0 1325.91     .07       0 1359.39     .12       0
#XS Ineff= 2 , 0
       0 1323.92  219.34 1360.92       0  219.34
Bank Sta=1325.91,1359.39
Exp/Cntr=.5,.3

Type RM Length L Ch R = 1 ,20422.82,356.27,387.08,353.88
XS GIS Cut Line= 5
     1861778.438      396206.865     1861655.706      396018.931
     1861310.779      395454.009     1861121.079      395009.704
     1860838.769      394354.375
#Sta/Elev= 30
       0  227.05  172.13  226.17  187.11  225.51  296.13   224.3  319.16  223.32
  447.38  222.54  470.66   219.2  533.79     218  560.54  218.12  592.15     217
   615.8   215.4 1050.21  211.92  1173.7  212.38  1176.5  212.42 1182.98  209.18
 1202.98  209.18 1210.41  212.89 1212.26  212.92 1346.45  212.97  1502.2  215.42
 1656.32  216.36 1710.46  217.59 1724.31  217.35 1758.96  218.45  1788.9  218.21
 1937.76   222.7  1967.6  225.31 1984.78  225.25 2004.94  226.01 2083.02   231.2
#Mann= 3 , 0 , 0
       0     .12       0  1173.7     .07       0 1212.26     .12       0
Bank Sta=1173.7,1212.26
Exp/Cntr=.3,.1