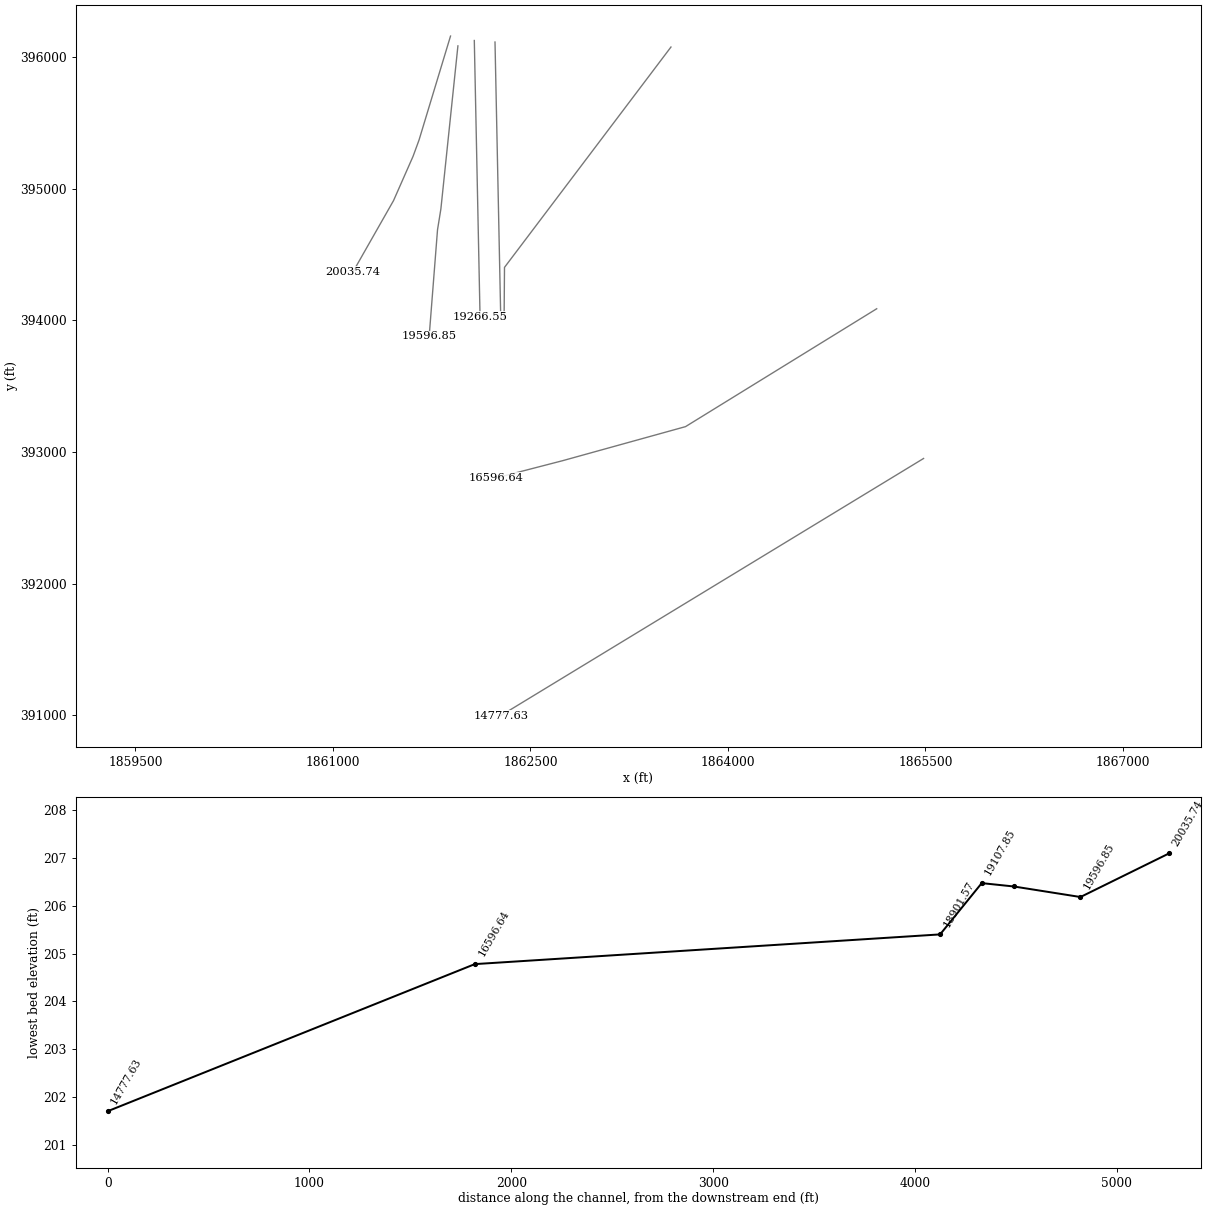
HEC-RAS study jordan.prj: Jordan Creek

--- jordan.g02 (geometry) --- (continued)

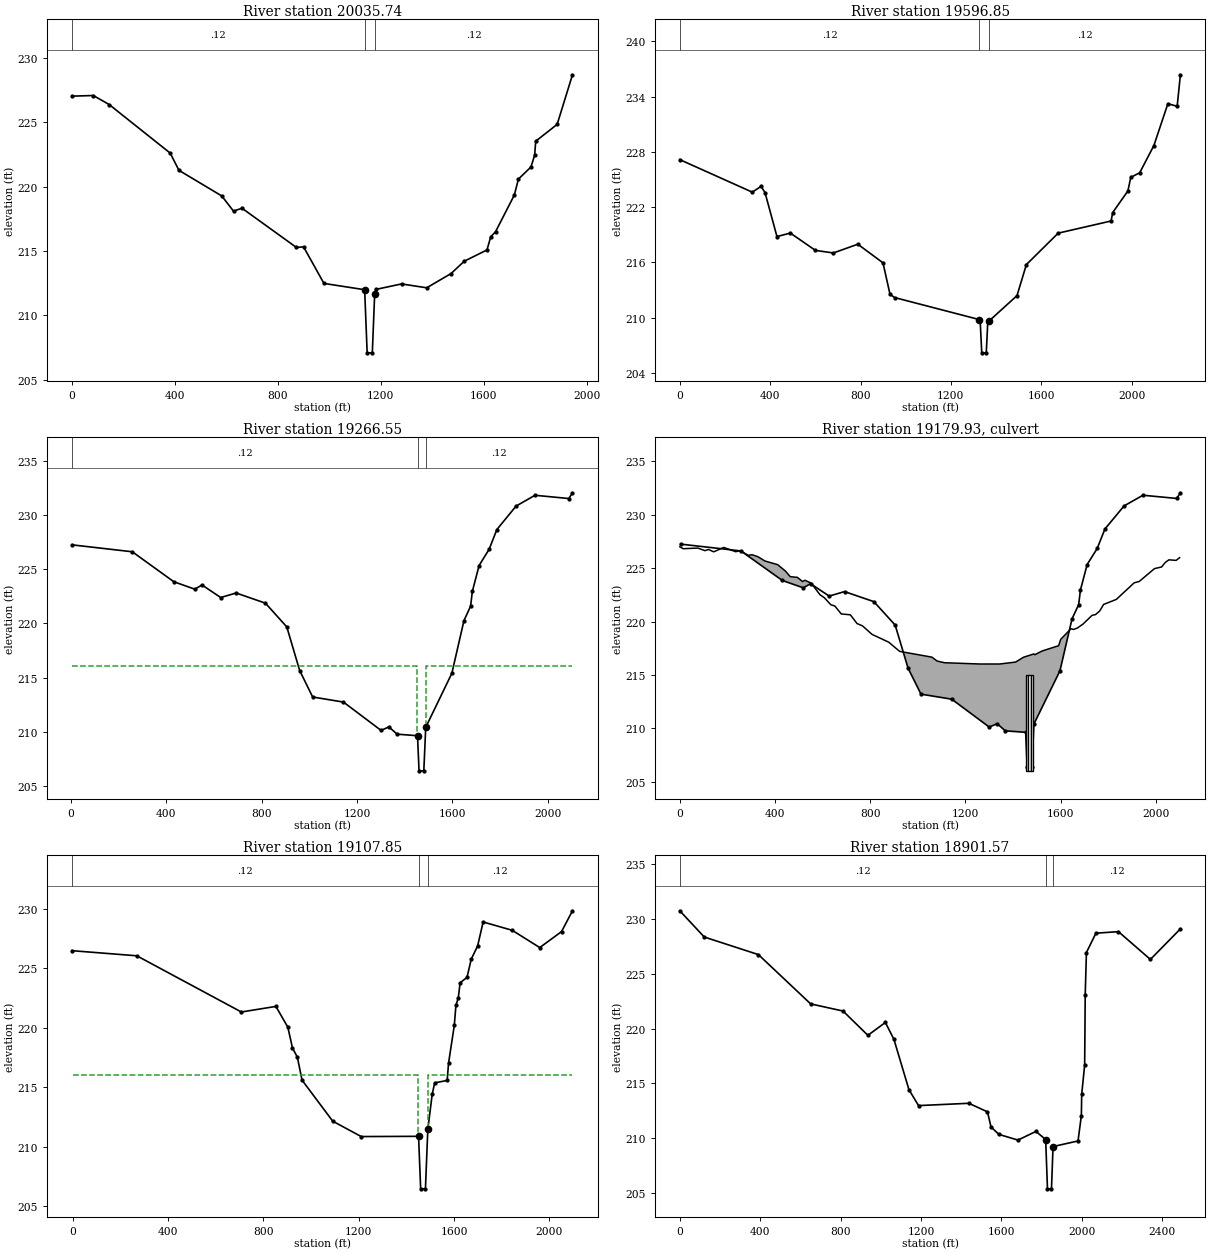
Type RM Length L Ch R = 1 ,20035.74,355.79,438.9,428.82
XS GIS Cut Line= 5
     1861892.968      396158.615     1861653.813       395368.99
     1861608.386      395245.098     1861460.208      394909.151
     1861153.271      394369.716
#Sta/Elev= 30
       0  227.02   83.18  227.07  144.85  226.37  381.86   222.6  416.01  221.26
  582.38  219.27  627.95  218.09   660.8  218.32  872.56  215.27  900.04  215.32
  979.23  212.48 1137.38  211.99 1147.17  207.09 1167.17  207.09  1176.3  211.65
 1180.01  212.01 1280.62  212.44  1378.6  212.14 1473.38  213.25  1524.1   214.2
 1612.72  215.08 1627.16   216.1  1645.9  216.49  1719.1  219.35 1734.76  220.58
 1783.51  221.52 1797.96  222.45 1801.91  223.52 1885.28  224.83 1944.82  228.68
#Mann= 3 , 0 , 0
       0     .12       0 1137.38     .07       0  1176.3     .12       0
Bank Sta=1137.38,1176.3
Exp/Cntr=.3,.1

Type RM Length L Ch R = 1 ,19596.85,294.02,330.3,326.64
XS GIS Cut Line= 4
     1861949.129      396084.065      1861819.71      394845.354
     1861794.157      394686.927     1861730.871      393879.367
#Sta/Elev= 30
       0  227.15  320.93  223.62  359.68  224.25  377.19  223.58  430.11   218.8
   489.3  219.18   600.4   217.3   679.8  217.02  787.93  217.97  899.39  215.95
  930.64  212.53  950.94  212.18 1325.87  209.79 1329.59  209.71 1336.66  206.18
 1356.66  206.18 1363.42  209.56 1367.45   209.6 1492.68  212.39 1534.24  215.76
 1674.96  219.17 1909.17  220.49 1916.44  221.41 1983.56  223.75 1996.34  225.23
 2035.77  225.72 2098.64  228.68 2160.59  233.22 2201.71  232.94 2215.96  236.36
#Mann= 3 , 0 , 0
       0     .12       0 1325.87     .07       0 1367.45     .12       0
Bank Sta=1325.87,1367.45
Exp/Cntr=.5,.3

Type RM Length L Ch R = 1 ,19266.55,157.94,158.7,157.18
XS GIS Cut Line= 2
       1862073.6      396124.951      1862117.26      394025.313
#Sta/Elev= 30
     3.4  227.24  256.89   226.6  430.85  223.84  519.17  223.15  549.31  223.54
  627.81  222.38   692.3   222.8  815.48  221.86  905.02  219.67  959.04  215.65
 1013.47  213.21 1142.64  212.74 1300.43  210.13 1333.32  210.45 1367.96  209.78
 1453.34  209.64 1459.82   206.4 1479.82   206.4 1487.84  210.41  1597.4  215.39
 1648.18  220.25 1676.02  221.58 1683.41  222.94 1711.68  225.33 1753.85  226.83
 1786.33  228.65 1866.77  230.81 1946.25  231.81 2088.03  231.51 2103.49  232.04
#Mann= 3 , 0 , 0
     3.4     .12       0 1453.34     .07       0 1487.84     .12       0
#XS Ineff= 2 , 0
       0 1449.32  216.03 1490.32       0  216.03
Bank Sta=1453.34,1487.84
Exp/Cntr=.5,.3

Type RM Length L Ch R = 2 ,19179.93,,,
BEGIN DESCRIPTION:
US 15-501 (NCDOT # 100)
END DESCRIPTION:
Bridge Culvert--1,0,-1,-1, 0
Deck Dist Width WeirC Skew NumUp NumDn MinLoCord MaxHiCord MaxSubmerge Is_Ogee
59.62,54,2.6,0, 60, 60,216.03,,.95,0,0,0,,
       0   14.25   75.81  105.53   120.3   142.4  184.74  234.84  253.88  287.78
  303.03  327.51  357.95  411.21  444.41  463.89  493.97  516.06   525.7  551.73
  589.03   607.2  634.74  651.56  678.62   716.7  744.94  767.42  807.81  877.86
  923.92 1059.53 1080.98 1111.95 1260.81 1344.14 1411.12 1443.94 1487.75 1491.93
  1522.8  1591.8 1600.65 1644.08  1654.3  1670.2 1694.11 1732.42  1746.9  1764.3
  1780.9 1834.37  1909.3 1930.59 1994.72 2024.33  2039.8 2055.13 2085.67 2100.09
  226.99  226.81  226.87  226.63  226.74  226.52  226.93  226.53  226.62  226.19
  226.25  226.07  225.66  225.32  224.71   224.2  224.13  223.74  223.86   223.6
  222.51  222.23  221.57  221.45  220.71  220.63  219.81   219.6   218.8  218.07
  217.21  216.67  216.31  216.15  216.03  216.03  216.21  216.66  216.97   216.9
  217.25  217.74  218.34  219.33  219.26  219.39  219.76  220.58  220.65  220.98
   221.6  222.07  223.62  223.75  224.95   225.1  225.52  225.77  225.72  225.97
                                                                                
                                                                                
                                                                                
                                                                                
                                                                                
                                                                                
       0   14.25   75.81  105.53   120.3   142.4  184.74  234.84  253.88  287.78
  303.03  327.51  357.95  411.21  444.41  463.89  493.97  516.06   525.7  551.73
  589.03   607.2  634.74  651.56  678.62   716.7  744.94  767.42  807.81  877.86
  923.92 1059.53 1080.98 1111.95 1260.81 1344.14 1411.12 1443.94 1487.75 1491.93
  1522.8  1591.8 1600.65 1644.08  1654.3  1670.2 1694.11 1732.42  1746.9  1764.3
  1780.9 1834.37  1909.3 1930.59 1994.72 2024.33  2039.8 2055.13 2085.67 2100.09
  226.99  226.81  226.87  226.63  226.74  226.52  226.93  226.53  226.62  226.19
  226.25  226.07  225.66  225.32  224.71   224.2  224.13  223.74  223.86   223.6
  222.51  222.23  221.57  221.45  220.71  220.63  219.81   219.6   218.8  218.07
  217.21  216.67  216.31  216.15  216.03  216.03  216.21  216.66  216.97   216.9
  217.25  217.74  218.34  219.33  219.26  219.39  219.76  220.58  220.65  220.98
   221.6  222.07  223.62  223.75  224.95   225.1  225.52  225.77  225.72  225.97
                                                                                
                                                                                
                                                                                
                                                                                
                                                                                
                                                                                
Multiple Barrel Culv=2,9,10,54,.012,.4,1,8,1,206.04,206.02, 3,Culvert #1  , 0 ,59.62
 1458.82 1458.82 1469.82 1469.82 1480.82 1480.82
BC Design=,, 0 ,, 0 ,,,,,,

Type RM Length L Ch R = 1 ,19107.85,307.94,206.28,154.61
XS GIS Cut Line= 2
     1862230.822      396113.304     1862274.482      394013.667
#Sta/Elev= 30
    -3.4  226.47  268.92  226.04  707.61  221.32  852.52  221.79  902.66  220.04
  921.98   218.3  942.62  217.52  962.12   215.6 1090.98  212.15 1210.56  210.86
 1450.99  210.88 1459.81  206.47 1479.81  206.47 1489.79  211.46 1508.22  214.41
 1518.55  215.37 1570.92  215.57    1577  217.05 1600.97  220.21  1607.7  221.87
 1617.68  222.51 1625.26  223.77 1654.26  224.23 1672.03  225.76 1698.85  226.87
 1721.87  228.88 1843.98  228.18 1959.39  226.73 2050.71  228.07 2096.69  229.82
#Mann= 3 , 0 , 0
    -3.4     .12       0 1450.99     .07       0 1489.79     .12       0
#XS Ineff= 2 , 0
       0 1449.32  216.03 1490.32       0  216.03
Bank Sta=1450.99,1489.79
Exp/Cntr=.5,.3

Type RM Length L Ch R = 1 ,18901.57,1912.74,2304.93,1743.26
XS GIS Cut Line= 3
     1863567.239      396075.413     1862302.919      394401.922
     1862299.878      394009.441
#Sta/Elev= 30
       0  230.72  121.76  228.33  390.92  226.73  650.99  222.24  811.91  221.59
  935.56  219.38 1022.54  220.55 1065.14  219.01 1139.77  214.43 1187.49  212.98
 1437.77  213.19 1530.48  212.41 1547.78  211.04 1586.95  210.36 1681.89  209.84
 1771.46  210.63 1819.81  209.89 1828.78   205.4 1848.78   205.4 1856.47  209.25
 1980.78  209.76 1997.33  212.07 1999.05  214.01  2013.8  216.69 2016.55  223.09
 2022.57  226.92 2069.72  228.68 2181.81  228.82  2340.7  226.29 2489.89  229.07
#Mann= 3 , 0 , 0
       0     .12       0 1819.81     .07       0 1856.47     .12       0
Bank Sta=1819.81,1856.47
Exp/Cntr=.3,.1

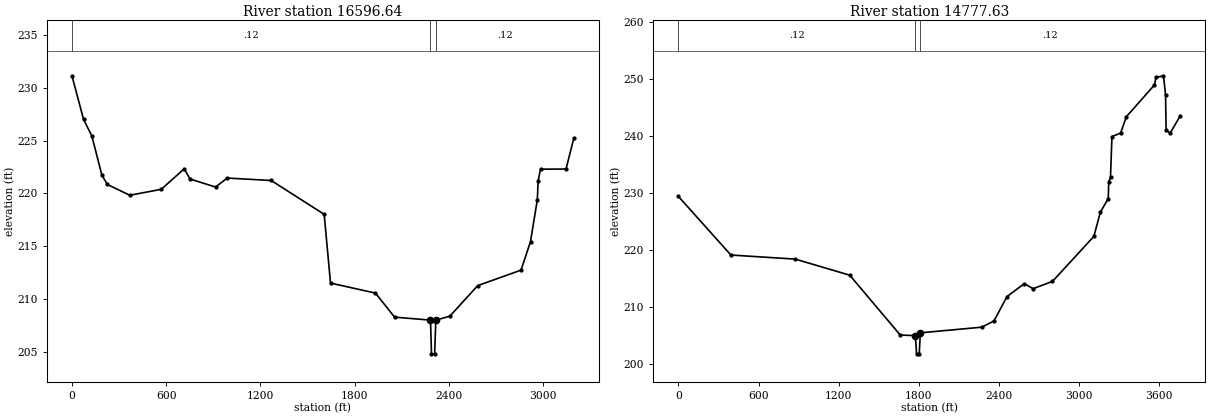
Type RM Length L Ch R = 1 ,16596.64,1630.52,1819.01,1392.81
XS GIS Cut Line= 4
     1865129.739      394087.566      1863677.79      393192.302
     1862742.657      392933.168     1862239.114      392802.844
#Sta/Elev= 30
       0  231.15    73.6  227.03  127.01  225.43  190.12  221.75  225.51  220.84
  368.11  219.82  568.48  220.38  715.18  222.33  751.69  221.36  914.84   220.6
  988.88  221.45 1268.78  221.22  1606.3  218.01  1646.6  211.49 1932.84  210.54
 2054.73  208.26 2282.14  207.98 2283.32  207.98 2289.72  204.78 2309.72  204.78
  2317.3  207.98 2406.47  208.35 2584.08  211.25 2860.02  212.72 2920.22  215.43
 2963.75  219.41 2968.89  221.18 2983.88  222.29 3146.51  222.31 3196.28  225.24
#Mann= 3 , 0 , 0
       0     .12       0 2282.14     .07       0  2317.3     .12       0
Bank Sta=2282.14,2317.3
Exp/Cntr=.3,.1

Type RM Length L Ch R = 1 ,14777.63,1035.16,1114.73,1059.53
XS GIS Cut Line= 2
     1865485.642      392950.413     1862273.836      390997.288
#Sta/Elev= 30
       0  229.35  392.97  219.06  875.35  218.34 1283.05  215.52 1661.55  205.01
 1775.12  204.91 1783.49  201.71 1803.49  201.71 1811.86   205.4 2271.32  206.39
 2363.21  207.48 2461.21  211.77 2590.99  214.04 2656.22  213.15 2801.68  214.43
 3111.57  222.33 3160.08  226.58  3219.1  228.97 3223.16   231.9 3236.14  232.78
 3246.96  239.86 3311.42  240.46 3355.52  243.36 3565.09  248.91 3576.39  250.23
 3632.82  250.53  3648.2  247.22 3652.78  240.93 3683.57  240.49 3759.04  243.52
#Mann= 3 , 0 , 0
       0     .12       0 1775.12     .07       0 1811.86     .12       0
Bank Sta=1775.12,1811.86
Exp/Cntr=.3,.1