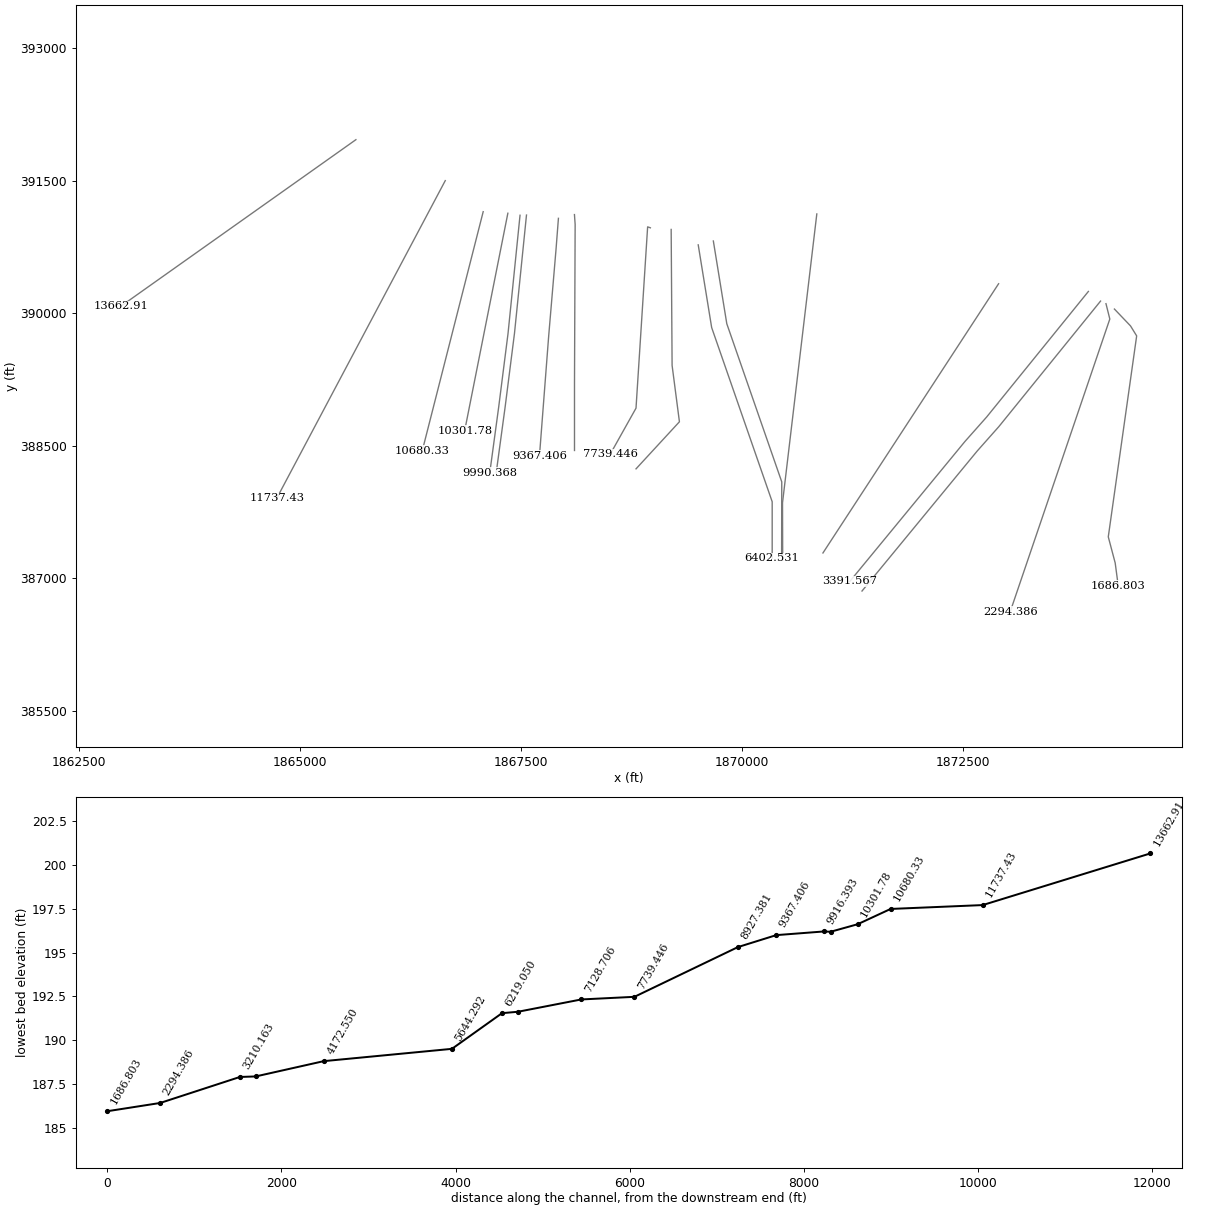
HEC-RAS study jordan.prj: Jordan Creek

--- jordan.g02 (geometry) --- (continued)

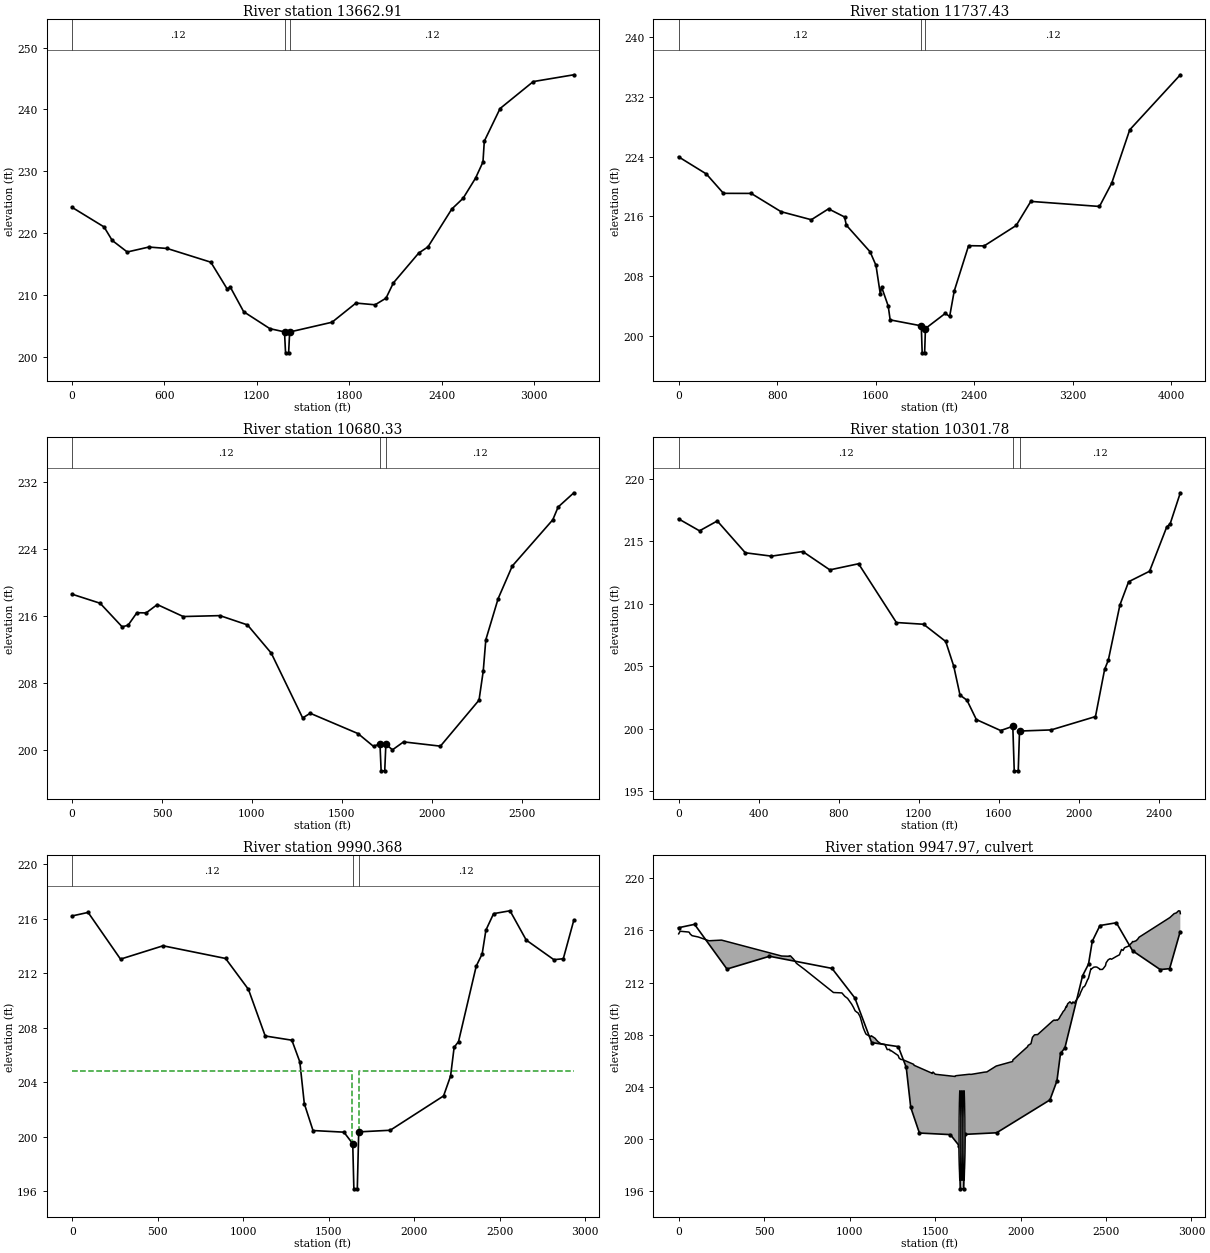
Type RM Length L Ch R = 1 ,13662.91,1855.1,1925.48,1950.49
XS GIS Cut Line= 2
     1865629.703      391963.553     1862970.807      390079.535
#Sta/Elev= 30
       0  224.17  207.89     221  260.62  218.82  358.42  216.95  498.51  217.75
   617.4  217.52  901.12   215.3 1006.83  210.99 1028.07  211.25 1114.43  207.29
 1284.75  204.55 1379.59  204.03 1386.36  200.64 1406.36  200.64  1413.1  204.01
 1688.26  205.59 1843.53  208.69 1967.75  208.41 2038.83  209.48 2086.66  211.95
 2251.29  216.78 2311.42  217.78 2466.08   223.9 2539.57  225.64 2620.35   228.9
 2668.48  231.51  2677.1  234.87 2779.53  240.15 2995.02  244.51 3258.72  245.61
#Mann= 3 , 0 , 0
       0     .12       0 1379.59     .07       0  1413.1     .12       0
Bank Sta=1379.59,1413.1
Exp/Cntr=.3,.1

Type RM Length L Ch R = 1 ,11737.43,982.14,1057.1,1042.11
XS GIS Cut Line= 2
     1866641.119      391500.222     1864732.751      387902.928
#Sta/Elev= 30
       0  223.99  225.54  221.69  364.61  219.09  589.59  219.08  831.86  216.63
 1077.55  215.55 1217.15  217.01 1347.43  215.92  1361.7  214.82 1554.58  211.25
 1602.37  209.43 1637.52  205.57 1647.72  206.53  1701.6  203.98  1717.3  202.12
 1969.97  201.32 1977.21   197.7 1997.21   197.7 2003.73  200.96 2163.88  202.98
 2200.21  202.59 2237.02  205.97 2353.78  212.07 2480.11  212.04 2740.08  214.78
 2858.97  218.01 3415.93  217.33 3515.42  220.46 3661.61  227.61 4072.15  234.99
#Mann= 3 , 0 , 0
       0     .12       0 1969.97     .07       0 2003.73     .12       0
Bank Sta=1969.97,2003.73
Exp/Cntr=.3,.1

Type RM Length L Ch R = 1 ,10680.33,373.7,378.55,388.57
XS GIS Cut Line= 2
     1867070.346      391148.692     1866381.334      388444.975
#Sta/Elev= 30
       0  218.59  155.84  217.51  278.49  214.69  311.45  214.88  360.69  216.38
  411.47  216.35  473.83  217.35  618.03  215.92  822.23  216.03  975.17  214.92
 1107.48  211.55 1282.14   203.8 1324.09  204.36 1590.16  201.93 1676.23   200.4
 1712.01  200.72 1718.48  197.48 1738.48  197.48 1744.84  200.66 1781.52  199.99
  1843.2  200.94 2048.18  200.43 2262.84  205.93 2286.29  209.41 2300.52  213.14
 2369.27  218.07 2447.78  221.96 2672.93  227.48 2702.73  229.01 2790.13  230.71
#Mann= 3 , 0 , 0
       0     .12       0 1712.01     .07       0 1744.84     .12       0
Bank Sta=1712.01,1744.84
Exp/Cntr=.3,.1

Type RM Length L Ch R = 1 ,10301.78,288.36,311.42,318.02
XS GIS Cut Line= 2
     1867349.439      391131.248     1866861.026      388671.738
#Sta/Elev= 30
       0  216.81  104.85  215.85  193.55  216.64  333.78  214.09  464.49  213.82
  620.87  214.19   756.1  212.72  899.68  213.21 1088.61   208.5  1224.6  208.36
  1335.1  206.98 1375.24     205 1406.64  202.68 1441.44  202.27 1488.28  200.72
 1609.75  199.84 1670.44  200.18 1677.57  196.61 1697.57  196.61 1703.94   199.8
 1861.91  199.89 2083.52  200.96 2129.32  204.75 2147.53  205.47  2205.7  209.91
 2249.17  211.77 2353.83  212.61 2439.12  216.14 2456.89  216.42 2507.54   218.9
#Mann= 3 , 0 , 0
       0     .12       0 1670.44     .07       0 1703.94     .12       0
Bank Sta=1670.44,1703.94
Exp/Cntr=.5,.3

Type RM Length L Ch R = 1 ,9990.368,72.83,73.98,74.66
XS GIS Cut Line= 4
     1867487.172      391108.329     1867351.373      389770.112
     1867245.787      388938.395     1867144.732       388193.79
#Sta/Elev= 30
    -.75  216.21   93.06  216.47  282.59  213.04  531.33  214.02   897.1  213.09
 1030.92  210.82 1128.88   207.4 1284.83  207.09 1331.36   205.5 1357.63  202.43
 1408.43  200.46 1589.27  200.34 1640.86  199.49 1647.48  196.18 1667.48  196.18
 1675.84  200.36 1860.13  200.48 2172.12     203 2213.08  204.46 2233.94  206.57
  2259.6  206.99 2363.16  212.53 2397.81  213.42 2419.74  215.17 2464.72  216.38
 2560.77  216.59  2655.6  214.44  2817.3     213 2872.34  213.07 2934.16  215.91
#Mann= 3 , 0 , 0
    -.75     .12       0 1640.86     .07       0 1675.84     .12       0
#XS Ineff= 2 , 0
       0 1637.03   204.8 1677.93       0   204.8
Bank Sta=1640.86,1675.84
Exp/Cntr=.5,.3

Type RM Length L Ch R = 2 ,9947.97 ,,,
BEGIN DESCRIPTION:
Railroad
END DESCRIPTION:
Bridge Culvert--1,0,-1,-1, 0
Deck Dist Width WeirC Skew NumUp NumDn MinLoCord MaxHiCord MaxSubmerge Is_Ogee
30.4,24,2.6,0,145,145,204.8,,.95,0,0,0,,
       0     8.5   58.33   62.43   67.31   78.48  114.36  114.58  177.41  249.95
  253.95  602.51  646.25  647.42  654.13  673.34  677.18  688.99  733.71  905.65
   954.9  971.91  988.15 1011.92 1022.26 1032.31 1041.48 1049.09 1060.34 1064.02
 1075.99 1080.11 1090.05 1096.04 1099.01 1122.98 1126.85 1129.63  1139.6  1149.9
 1154.79 1165.93 1182.19 1206.73 1220.17 1233.58 1237.42  1241.7 1283.84 1290.19
 1299.78 1315.24 1316.62 1374.99 1376.68 1482.24 1482.94 1488.01 1501.09 1617.23
 1618.52 1622.44 1700.34 1710.98 1788.14 1803.12 1857.66 1953.68 1955.45 2041.84
 2043.32 2044.17 2061.16 2069.66  2081.7  2092.4 2099.66 2180.15 2183.48 2188.36
 2196.56 2202.39 2209.75 2214.83  2225.5 2233.09 2242.52 2249.22 2258.06 2267.21
 2270.12 2275.49 2289.04 2300.16 2306.87 2314.75 2323.02 2327.26 2341.48 2345.53
 2351.22  2366.5  2373.3 2378.58 2393.53 2396.12 2397.36 2402.56 2411.72 2414.99
 2428.25 2437.64 2446.61 2460.69 2464.18 2467.09 2479.21 2485.44 2497.08 2500.76
 2512.92  2524.9 2531.89 2562.22 2577.01 2579.48 2582.72 2590.93 2599.81 2607.66
  2612.5 2623.53 2630.37 2651.46 2655.45 2661.32 2676.02 2685.45 2693.29 2873.77
 2898.58 2911.82 2924.57 2932.74 2934.91
  215.74  215.94  215.88  215.85  215.73   215.6   215.5   215.5  215.21  215.26
  215.25  214.04  214.02  214.05  214.05  213.78  213.71  213.48  213.04  211.24
  211.21  210.95  210.79  210.35  210.11  209.84  209.74  209.68  209.42  209.28
  208.72  208.53  208.21  208.05  208.02  207.86  207.92   207.9  207.81  207.72
  207.63  207.47  207.32  207.25  206.86  206.88  206.77  206.79  206.41   206.2
  206.11  206.08  206.06  205.73  205.66  205.05  205.03  205.14  204.97   204.8
  204.83  204.86  204.97  204.96  205.13  205.15   205.6  205.95  206.07  207.09
  207.15  207.18  207.32   207.8  207.99  208.01  208.01  208.96     209  209.06
  209.13   209.1  209.14  209.11  209.24  209.43  209.62  209.78   209.9  210.18
  210.14  210.37  210.53  210.38  210.52  210.42  210.61  210.67  210.95  211.02
  211.23  211.66  211.69   211.8  212.26  212.29  212.33   212.6  213.07  213.05
  213.18   213.2  213.19  213.07     213  213.01  213.01   213.1   213.3  213.52
  213.75  213.84  213.79  214.02  214.12  214.15  214.28  214.54  214.47  214.66
   214.7  214.76  214.79  215.06  215.15  215.14  215.21  215.33  215.48  216.99
  217.29  217.35  217.51  217.49  217.29
                                                                                
                                                                                
                                                                                
                                                                                
                                                                                
                                                                                
                                                                                
                                                                                
                                                                                
                                                                                
                                                                                
                                                                                
                                                                                
                                                                                
                                        
       0     8.5   58.33   62.43   67.31   78.48  114.36  114.58  177.41  249.95
  253.95  602.51  646.25  647.42  654.13  673.34  677.18  688.99  733.71  905.65
   954.9  971.91  988.15 1011.92 1022.26 1032.31 1041.48 1049.09 1060.34 1064.02
 1075.99 1080.11 1090.05 1096.04 1099.01 1122.98 1126.85 1129.63  1139.6  1149.9
 1154.79 1165.93 1182.19 1206.73 1220.17 1233.58 1237.42  1241.7 1283.84 1290.19
 1299.78 1315.24 1316.62 1374.99 1376.68 1482.24 1482.94 1488.01 1501.09 1617.23
 1618.52 1622.44 1700.34 1710.98 1788.14 1803.12 1857.66 1953.68 1955.45 2041.84
 2043.32 2044.17 2061.16 2069.66  2081.7  2092.4 2099.66 2180.15 2183.48 2188.36
 2196.56 2202.39 2209.75 2214.83  2225.5 2233.09 2242.52 2249.22 2258.06 2267.21
 2270.12 2275.49 2289.04 2300.16 2306.87 2314.75 2323.02 2327.26 2341.48 2345.53
 2351.22  2366.5  2373.3 2378.58 2393.53 2396.12 2397.36 2402.56 2411.72 2414.99
 2428.25 2437.64 2446.61 2460.69 2464.18 2467.09 2479.21 2485.44 2497.08 2500.76
 2512.92  2524.9 2531.89 2562.22 2577.01 2579.48 2582.72 2590.93 2599.81 2607.66
  2612.5 2623.53 2630.37 2651.46 2655.45 2661.32 2676.02 2685.45 2693.29 2873.77
 2898.58 2911.82 2924.57 2932.74 2934.91
  215.74  215.94  215.88  215.85  215.73   215.6   215.5   215.5  215.21  215.26
  215.25  214.04  214.02  214.05  214.05  213.78  213.71  213.48  213.04  211.24
  211.21  210.95  210.79  210.35  210.11  209.84  209.74  209.68  209.42  209.28
  208.72  208.53  208.21  208.05  208.02  207.86  207.92   207.9  207.81  207.72
  207.63  207.47  207.32  207.25  206.86  206.88  206.77  206.79  206.41   206.2
  206.11  206.08  206.06  205.73  205.66  205.05  205.03  205.14  204.97   204.8
  204.83  204.86  204.97  204.96  205.13  205.15   205.6  205.95  206.07  207.09
  207.15  207.18  207.32   207.8  207.99  208.01  208.01  208.96     209  209.06
  209.13   209.1  209.14  209.11  209.24  209.43  209.62  209.78   209.9  210.18
  210.14  210.37  210.53  210.38  210.52  210.42  210.61  210.67  210.95  211.02
  211.23  211.66  211.69   211.8  212.26  212.29  212.33   212.6  213.07  213.05
  213.18   213.2  213.19  213.07     213  213.01  213.01   213.1   213.3  213.52
  213.75  213.84  213.79  214.02  214.12  214.15  214.28  214.54  214.47  214.66
   214.7  214.76  214.79  215.06  215.15  215.14  215.21  215.33  215.48  216.99
  217.29  217.35  217.51  217.49  217.29
                                                                                
                                                                                
                                                                                
                                                                                
                                                                                
                                                                                
                                                                                
                                                                                
                                                                                
                                                                                
                                                                                
                                                                                
                                                                                
                                                                                
                                        
Multiple Barrel Culv=3,6.916,10.66,24,.027,.7,1,34,2,196.81,196.79, 3,Culvert #1  , 0 ,30.4
 1645.82 1645.82 1657.48 1657.48 1669.14 1669.14
BC Design=,, 0 ,, 0 ,,,,,,

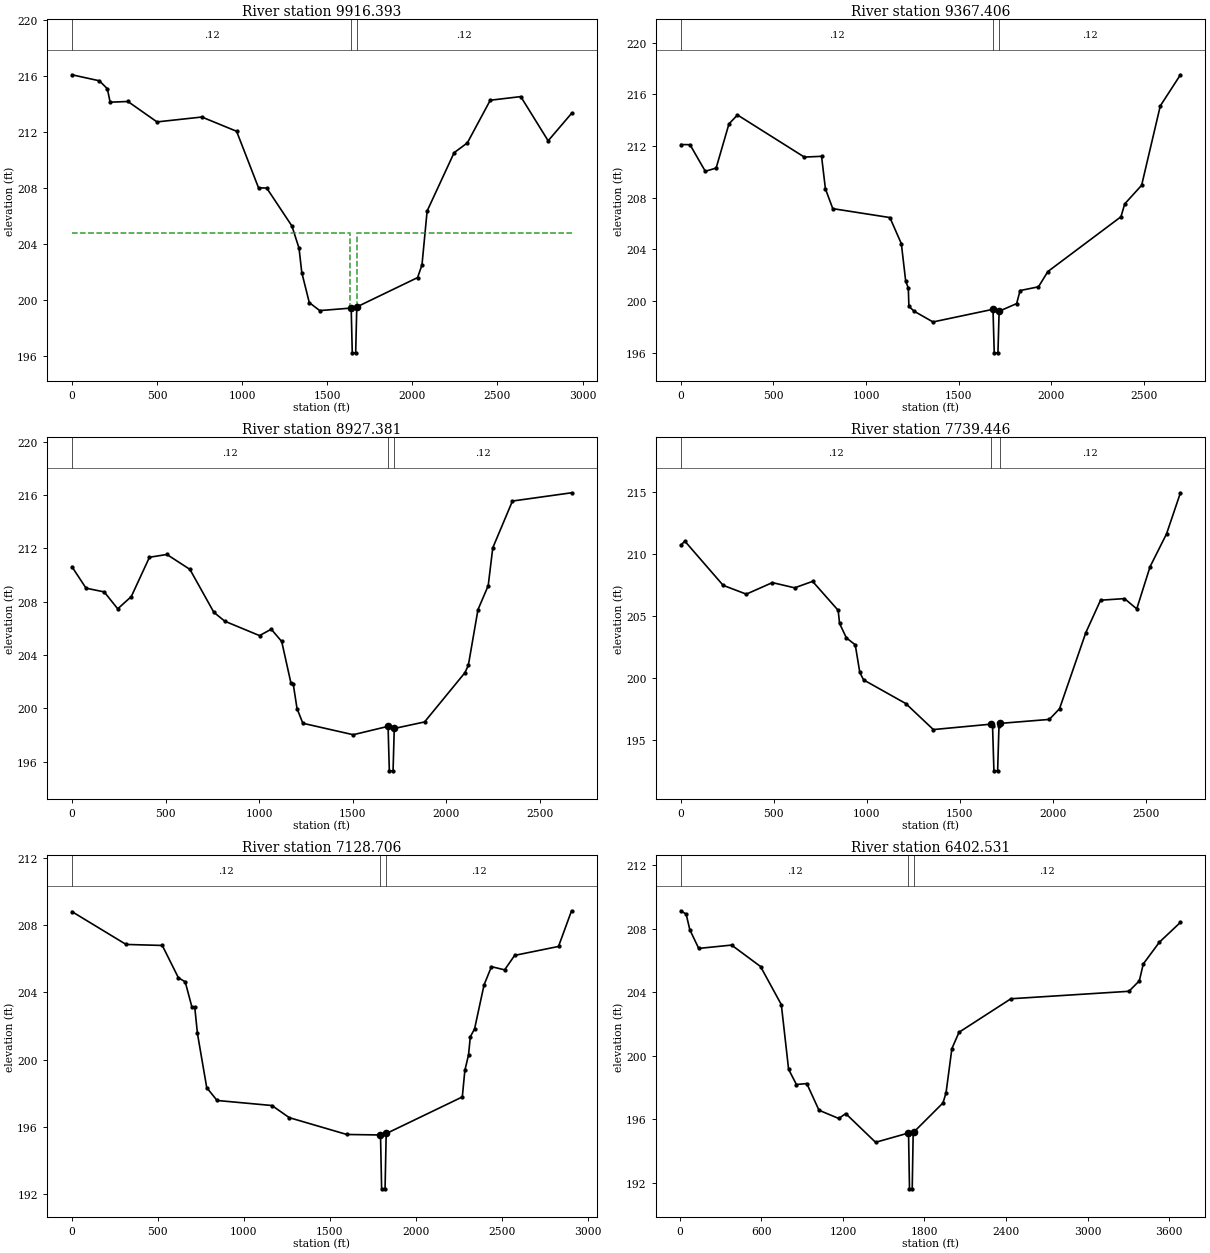
Type RM Length L Ch R = 1 ,9916.393,407.11,548.99,410.17
XS GIS Cut Line= 4
     1867560.278      391110.545     1867424.479      389772.328
     1867318.893      388940.611     1867217.839      388196.005
#Sta/Elev= 30
     .75  216.08  161.68  215.65  208.62  215.08  225.05  214.12   329.4  214.17
   500.3  212.71   763.9  213.06  967.95  212.04 1096.76     208 1145.01  207.98
 1292.79  205.27 1334.78  203.68 1350.86  201.94 1394.96  199.79  1456.5  199.22
 1639.56   199.4 1641.06   199.4 1647.47   196.2 1667.47   196.2 1674.04  199.49
 1675.38  199.49 2031.15  201.58 2057.04  202.49 2087.21  206.34 2245.85  210.51
 2323.49  211.21 2458.07  214.26 2637.24  214.52 2798.19  211.36 2935.66  213.32
#Mann= 3 , 0 , 0
     .75     .12       0 1639.56     .07       0 1675.38     .12       0
#XS Ineff= 2 , 0
       0 1637.03   204.8 1677.93       0   204.8
Bank Sta=1639.56,1675.38
Exp/Cntr=.5,.3

Type RM Length L Ch R = 1 ,9367.406,301.74,440.02,328.22
XS GIS Cut Line= 4
     1867921.773      391073.549     1867895.045       390728.12
     1867811.688      389744.503     1867707.028      388383.923
#Sta/Elev= 30
       0  212.11   49.37   212.1  132.12  210.04  190.56  210.29  259.82  213.71
  305.93   214.4  666.95  211.14  759.99   211.2  780.79  208.68  820.54  207.15
 1128.96  206.46 1190.79  204.44 1214.55  201.52  1228.5  201.01 1231.66  199.59
 1260.01  199.21 1361.87  198.38 1685.84  199.36 1692.57  195.99 1712.57  195.99
 1719.01  199.21 1813.59   199.8 1832.05  200.81 1931.51   201.1 1982.01  202.28
 2376.83  206.52 2397.53  207.52 2488.67  208.96 2589.33   215.1  2698.2  217.51
#Mann= 3 , 0 , 0
       0     .12       0 1685.84     .07       0 1719.01     .12       0
Bank Sta=1685.84,1719.01
Exp/Cntr=.3,.1

Type RM Length L Ch R = 1 ,8927.381,747.89,1187.94,722.66
XS GIS Cut Line= 4
     1868103.013      391115.931     1868110.921      391005.813
     1868103.599      389204.839     1868103.599      388446.054
#Sta/Elev= 30
       0  210.63   75.23  209.02  172.23  208.74  244.72  207.47   317.1  208.39
  414.18  211.34  507.45  211.55  630.45  210.43  758.32  207.21  816.96  206.54
 1002.54  205.46  1065.2  205.94 1121.01  205.02 1169.89  201.93 1182.72  201.82
 1202.97  199.98 1234.08  198.88 1503.19  198.02 1689.56  198.65 1696.24  195.31
 1716.24  195.31  1722.6  198.49 1884.69  198.98 2099.92  202.67 2118.54  203.23
 2170.09  207.41 2224.61   209.2 2249.17  212.05 2354.33  215.56 2670.17  216.18
#Mann= 3 , 0 , 0
       0     .12       0 1689.56     .07       0  1722.6     .12       0
Bank Sta=1689.56,1722.6
Exp/Cntr=.3,.1

Type RM Length L Ch R = 1 ,7739.446,391.1,610.74,475.85
XS GIS Cut Line= 4
     1868962.178      390966.191     1868931.338      390977.058
     1868799.714      388925.011     1868508.399      388404.992
#Sta/Elev= 30
       0  210.71   21.84  211.01  227.37  207.45  351.78  206.74  491.85  207.67
  611.66  207.25   708.1  207.77  845.61  205.43  852.92  204.38  889.68  203.21
  937.33  202.65  961.82  200.42  982.04  199.82 1208.97  197.91 1357.04  195.81
 1668.66  196.25 1675.28  196.11 1682.54  192.48 1702.54  192.48  1709.8  196.11
 1716.42  196.31 1980.25  196.63 2035.16  197.49 2176.44  203.63  2255.7  206.25
 2384.31  206.38 2450.16  205.55 2521.93  208.96 2610.23   211.6 2685.02  214.92
#Mann= 3 , 0 , 0
       0     .12       0 1668.66     .07       0 1716.42     .12       0
Bank Sta=1668.66,1716.42
Exp/Cntr=.3,.1

Type RM Length L Ch R = 1 ,7128.706,651.94,726.17,680.59
XS GIS Cut Line= 4
     1869197.633      390947.724     1869208.195      389408.635
     1869291.076      388771.032     1868799.974      388238.378
#Sta/Elev= 30
       0   208.8  314.92  206.85  525.51  206.79  619.22  204.87  658.84  204.63
  697.42  203.15  714.54  203.11  730.04  201.56  784.14  198.34  844.26  197.58
 1163.62  197.28 1264.22  196.56  1598.7  195.56 1793.37  195.53  1795.2  195.53
 1801.61  192.33 1821.61  192.33 1828.18  195.62 1829.85  195.62 2271.08  197.79
 2285.88  199.37 2307.32  200.29 2317.48  201.36 2342.59  201.84 2397.36  204.44
 2440.55  205.53 2517.21  205.34 2575.62   206.2 2830.68  206.73 2906.59  208.85
#Mann= 3 , 0 , 0
       0     .12       0 1793.37     .07       0 1829.85     .12       0
Bank Sta=1793.37,1829.85
Exp/Cntr=.5,.3

Type RM Length L Ch R = 1 ,6402.531,176.09,183.49,177.69
XS GIS Cut Line= 4
     1869503.772      390773.187     1869655.967      389837.186
     1870340.846      387866.257     1870340.846      387227.037
#Sta/Elev= 30
    8.17  209.14   47.13  208.93   74.39  207.94  139.63  206.77  381.45  206.98
  594.19  205.63  747.06  203.23  800.57  199.16  858.01   198.2  934.27  198.26
 1024.12  196.58 1169.65  196.06 1220.79  196.37 1440.19  194.56 1679.81  195.14
 1682.78  195.09 1689.71  191.63 1709.71  191.63 1716.73  195.14 1719.61  195.19
 1936.07  197.04 1958.53  197.68 2001.42  200.46 2053.89  201.49 2435.65   203.6
  3303.5  204.07 3380.03  204.73 3408.87  205.79 3527.19  207.16 3682.22  208.41
#Mann= 3 , 0 , 0
    8.17     .12       0 1679.81     .07       0 1719.61     .12       0
Bank Sta=1679.81,1719.61
Exp/Cntr=.5,.3

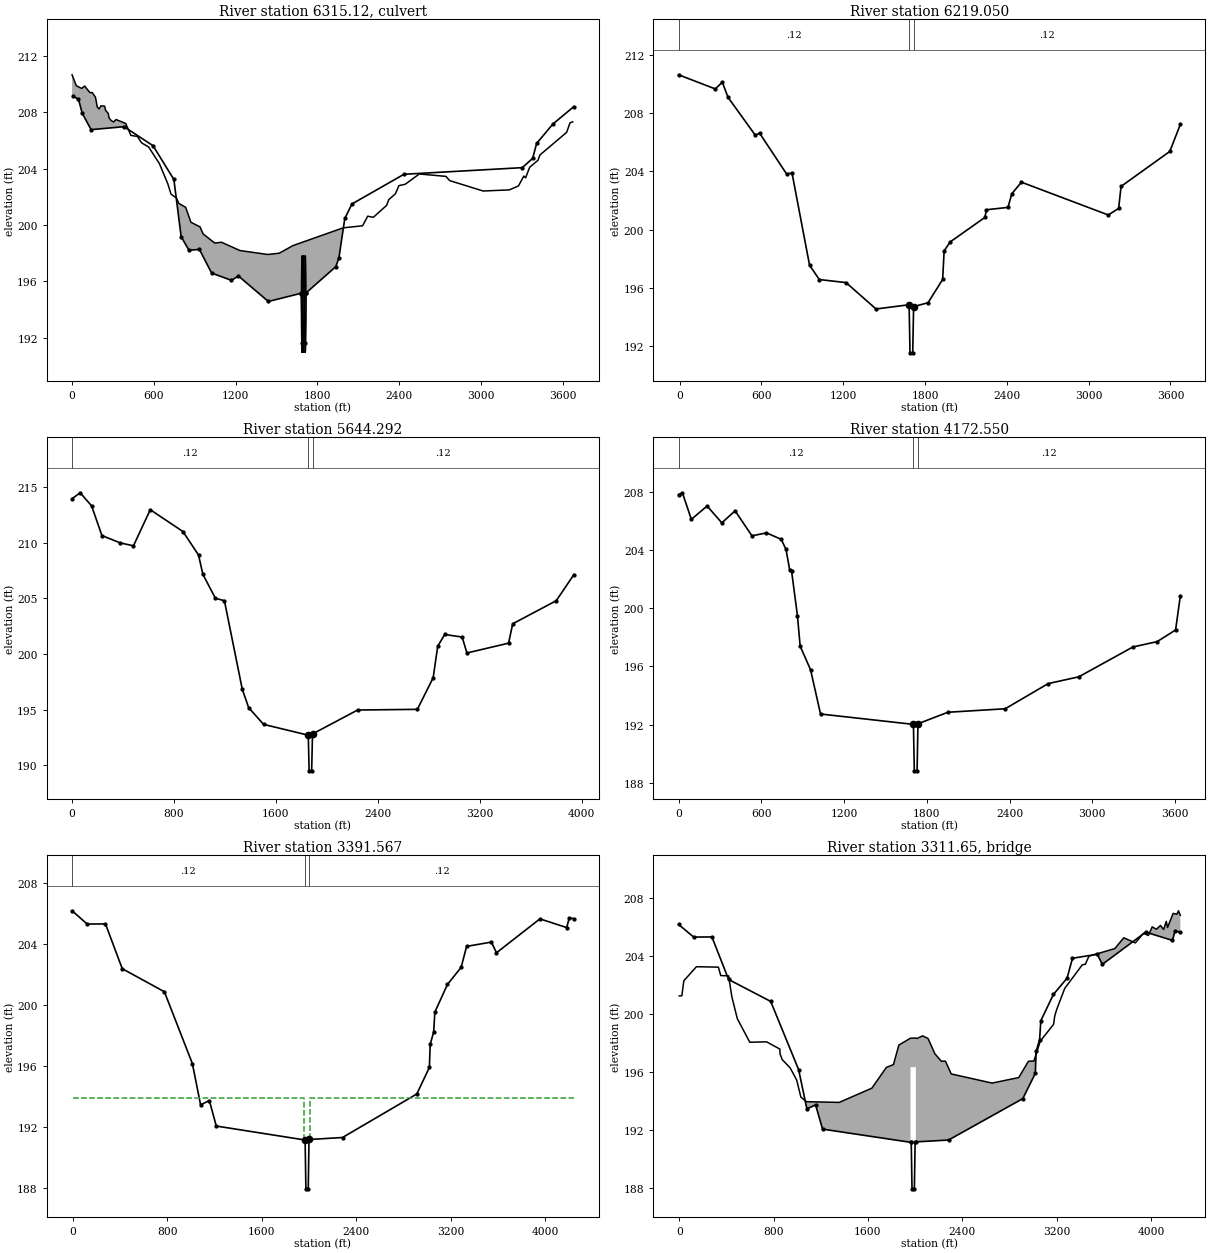
Type RM Length L Ch R = 2 ,6315.12 ,,,
BEGIN DESCRIPTION:
SR 1429 (NCDOT # 87)
END DESCRIPTION:
Bridge Culvert--1,0,-1,-1, 0
Deck Dist Width WeirC Skew NumUp NumDn MinLoCord MaxHiCord MaxSubmerge Is_Ogee
56.91,61,2.6,0, 60, 60,197.9,,.95,0,0,0,,
       0   31.11   70.39   92.36  130.89  147.52  171.67  185.13  198.17  211.35
  238.76  246.63  266.08  270.22  286.58  304.87  323.14  393.52  431.93  479.02
  510.59  561.57  640.64  703.08   725.8  765.77  783.57  833.54  872.12   939.1
  961.63 1047.42 1095.85 1232.14 1435.67 1520.28 1620.44 1988.58 2131.79 2169.54
 2210.37 2308.45 2324.19 2372.61 2398.18 2444.72 2547.81  2743.3 2770.76 3016.55
 3208.49  3275.8 3314.85 3328.05 3358.15 3419.31    3433 3629.39 3653.61 3674.05
  210.67  209.89   209.7  209.87   209.4  209.41  209.08  208.38  208.24  208.46
  208.44  208.13  207.92  207.63  207.42  207.32  207.49  207.21  206.36  206.29
  205.83  205.54  204.36  202.91  202.19  201.91  201.53  201.25  200.19  199.86
  199.36  198.71  198.77  198.18   197.9  197.99  198.53  199.79  199.94  200.62
  200.54  201.39   201.8  202.21  202.79  202.89  203.62  203.45  203.15  202.41
  202.49  202.77  203.47  203.35   204.1   204.6  204.97  206.58  207.25  207.33
                                                                                
                                                                                
                                                                                
                                                                                
                                                                                
                                                                                
       0   31.11   70.39   92.36  130.89  147.52  171.67  185.13  198.17  211.35
  238.76  246.63  266.08  270.22  286.58  304.87  323.14  393.52  431.93  479.02
  510.59  561.57  640.64  703.08   725.8  765.77  783.57  833.54  872.12   939.1
  961.63 1047.42 1095.85 1232.14 1435.67 1520.28 1620.44 1988.58 2131.79 2169.54
 2210.37 2308.45 2324.19 2372.61 2398.18 2444.72 2547.81  2743.3 2770.76 3016.55
 3208.49  3275.8 3314.85 3328.05 3358.15 3419.31    3433 3629.39 3653.61 3674.05
  210.67  209.89   209.7  209.87   209.4  209.41  209.08  208.38  208.24  208.46
  208.44  208.13  207.92  207.63  207.42  207.32  207.49  207.21  206.36  206.29
  205.83  205.54  204.36  202.91  202.19  201.91  201.53  201.25  200.19  199.86
  199.36  198.71  198.77  198.18   197.9  197.99  198.53  199.79  199.94  200.62
  200.54  201.39   201.8  202.21  202.79  202.89  203.62  203.45  203.15  202.41
  202.49  202.77  203.47  203.35   204.1   204.6  204.97  206.58  207.25  207.33
                                                                                
                                                                                
                                                                                
                                                                                
                                                                                
                                                                                
Multiple Barrel Culv=3,6.916,10.66,61,.027,.7,1,34,2,190.91,190.89, 3,Culvert #1  , 0 ,56.91
 1688.05 1688.05 1699.71 1699.71 1711.37 1711.37
BC Design=,, 0 ,, 0 ,,,,,,

Type RM Length L Ch R = 1 ,6219.050,693.99,574.76,527.77
XS GIS Cut Line= 4
     1869674.954      390816.893     1869827.149      389880.892
     1870449.191      388090.792     1870447.539      387253.408
#Sta/Elev= 30
   -8.17  210.63  261.39  209.66  312.95  210.12  355.04  209.08  555.12  206.48
  585.98  206.63   784.1  203.83  824.43  203.88  952.72  197.57 1024.12  196.58
 1220.79  196.37 1440.19  194.56 1683.12  194.85 1689.71  191.55 1709.71  191.55
 1716.05  194.72  1822.1  194.99 1929.29  196.59 1940.05  198.55 1984.28  199.16
 2238.75  200.84 2250.56  201.37 2408.49  201.53 2435.93  202.46 2507.02  203.26
 3143.92  201.01 3220.17  201.46 3237.84  202.97 3595.35  205.37 3672.61  207.22
#Mann= 3 , 0 , 0
   -8.17     .12       0 1683.12     .07       0 1716.05     .12       0
Bank Sta=1683.12,1716.05
Exp/Cntr=.5,.3

Type RM Length L Ch R = 1 ,5644.292,1594.63,1471.74,1313.86
XS GIS Cut Line= 3
     1870845.885      391123.156     1870457.718      387853.925
     1870459.686      387206.536
#Sta/Elev= 30
       0  213.95    63.9  214.48  153.46   213.3  234.37  210.64  378.54  209.98
   481.9  209.72  613.91  212.96  870.62     211  992.87  208.89 1026.97  207.16
 1125.28  205.01 1196.13  204.79  1336.5  196.83 1386.64  195.19  1503.6  193.69
 1854.64  192.72 1861.05  189.52 1881.05  189.52 1887.66  192.83 2242.09  194.98
 2710.75  195.04 2834.87  197.87  2870.7   200.7  2925.6  201.76 3062.42  201.53
 3099.96   200.1 3426.97  200.98  3459.5  202.72 3801.24  204.79 3939.59  207.13
#Mann= 3 , 0 , 0
       0     .12       0 1854.64     .07       0 1887.66     .12       0
Bank Sta=1854.64,1887.66
Exp/Cntr=.3,.1

Type RM Length L Ch R = 1 ,4172.550,794.37,780.98,660.94
XS GIS Cut Line= 2
     1872903.177      390333.226      1870915.33      387286.351
#Sta/Elev= 30
       0  207.83   28.18  207.95    92.7  206.12  207.37  207.04  313.77  205.88
  410.01  206.71  532.05  204.99  637.74  205.19  744.28  204.75  779.38  204.05
  806.14  202.63  819.77  202.55  862.02   199.5   881.8   197.4  957.31  195.77
 1029.45  192.73  1699.5  192.02 1702.99  192.02  1709.4  188.82  1729.4  188.82
 1735.89  192.07  1739.3  192.07 1952.46  192.85 2368.22  193.09 2679.53  194.82
 2902.36  195.29 3293.74  197.34 3470.04  197.71 3603.69  198.51 3637.99  200.86
#Mann= 3 , 0 , 0
       0     .12       0  1699.5     .07       0  1739.3     .12       0
Bank Sta=1699.5,1739.3
Exp/Cntr=.5,.3

Type RM Length L Ch R = 1 ,3391.567,210.67,181.41,197.95
XS GIS Cut Line= 4
     1873919.302      390245.992     1872767.971      388824.979
     1872521.562      388547.131     1871219.649      386964.742
#Sta/Elev= 30
   -6.22  206.15  122.06  205.28  276.82  205.29  418.54  202.36  775.52  200.85
 1012.53  196.15 1082.22  193.45 1156.13  193.73 1215.08  192.06 1963.93  191.15
 1967.42  191.15 1973.83  187.95 1993.83  187.95 2000.28  191.18 2003.73  191.18
 2284.12  191.31 2913.41  194.16 3019.73   195.9  3026.4  197.41  3055.9  198.21
 3066.17  199.52 3172.88  201.33 3288.79  202.45 3334.81  203.82 3544.89   204.1
 3587.76   203.4  3955.7  205.62 4182.61  205.05 4204.45  205.69 4243.17  205.63
#Mann= 3 , 0 , 0
   -6.22     .12       0 1963.93     .07       0 2003.73     .12       0
#XS Ineff= 2 , 0
       0 1956.33   193.9 2011.33       0   193.9
Bank Sta=1963.93,2003.73
Exp/Cntr=.5,.3

Type RM Length L Ch R = 3 ,3311.65 ,,,
BEGIN DESCRIPTION:
US 401 (NCDOT # 33)
END DESCRIPTION:
Bridge Culvert--1,0,-1,-1, 0
Deck Dist Width WeirC Skew NumUp NumDn MinLoCord MaxHiCord MaxSubmerge Is_Ogee
60.22,39.4,2.6,0, 60, 60,193.9,,.95,0,0,0,,
       0    21.9    38.5  145.51  331.68  351.72  418.26  445.55  491.86  598.18
  740.03  853.33  854.23  872.63  940.86  996.17 1031.08 1078.48 1356.35 1633.38
 1756.27 1816.29 1862.57 1950.68 1961.33 2006.33 2015.03 2064.84 2110.68 2167.64
 2222.86 2257.54 2306.28  2652.3 2879.27 2960.69  3007.9 3061.68 3174.47 3183.97
 3200.08 3269.31 3417.91 3443.82 3473.92 3693.76 3769.69  3868.1 3936.24 3978.62
  4010.7 4046.64 4080.75 4107.82 4130.23 4141.09 4188.27 4220.01 4233.64 4249.39
  201.23  201.24  202.27  203.24  203.21  202.63  202.61  201.19  199.67  198.04
  198.07  197.57  197.25  196.85  196.27  195.43  194.27  193.95   193.9  194.88
  196.31   196.5  197.85  198.27  198.32  198.33   198.3  198.48  198.29  197.25
  196.73  196.74  195.86  195.23  195.61  196.73  196.75  198.12  199.27  199.83
  200.28  201.75  203.37  203.41  203.96  204.49  205.23  204.88  205.54  205.39
  205.98  205.82  206.08   205.8  206.36  205.94  206.91  206.85  207.09  206.78
                                                                                
                                                                                
                                  196.33  196.33
                                                                                
                                                                                
                                                                                
       0    21.9    38.5  145.51  331.68  351.72  418.26  445.55  491.86  598.18
  740.03  853.33  854.23  872.63  940.86  996.17 1031.08 1078.48 1356.35 1633.38
 1756.27 1816.29 1862.57 1950.68 1961.33 2006.33 2015.03 2064.84 2110.68 2167.64
 2222.86 2257.54 2306.28  2652.3 2879.27 2960.69  3007.9 3061.68 3174.47 3183.97
 3200.08 3269.31 3417.91 3443.82 3473.92 3693.76 3769.69  3868.1 3936.24 3978.62
  4010.7 4046.64 4080.75 4107.82 4130.23 4141.09 4188.27 4220.01 4233.64 4249.39
  201.23  201.24  202.27  203.24  203.21  202.63  202.61  201.19  199.67  198.04
  198.07  197.57  197.25  196.85  196.27  195.43  194.27  193.95   193.9  194.88
  196.31   196.5  197.85  198.27  198.32  198.33   198.3  198.48  198.29  197.25
  196.73  196.74  195.86  195.23  195.61  196.73  196.75  198.12  199.27  199.83
  200.28  201.75  203.37  203.41  203.96  204.49  205.23  204.88  205.54  205.39
  205.98  205.82  206.08   205.8  206.36  205.94  206.91  206.85  207.09  206.78
                                                                                
                                                                                
                                  196.33  196.33
                                                                                
                                                                                
                                                                                
BR Coef=-1 , 1 , 0 ,, 0 ,,,.8,0,1.2,0,
WSPro=,,,, 1 ,,,, 0 ,,,, 0 ,,,,-1 ,-1 ,-1 , 0 , 0 , 0 , 0 , 0
BC Design=,, 0 ,, 0 ,,,,,,

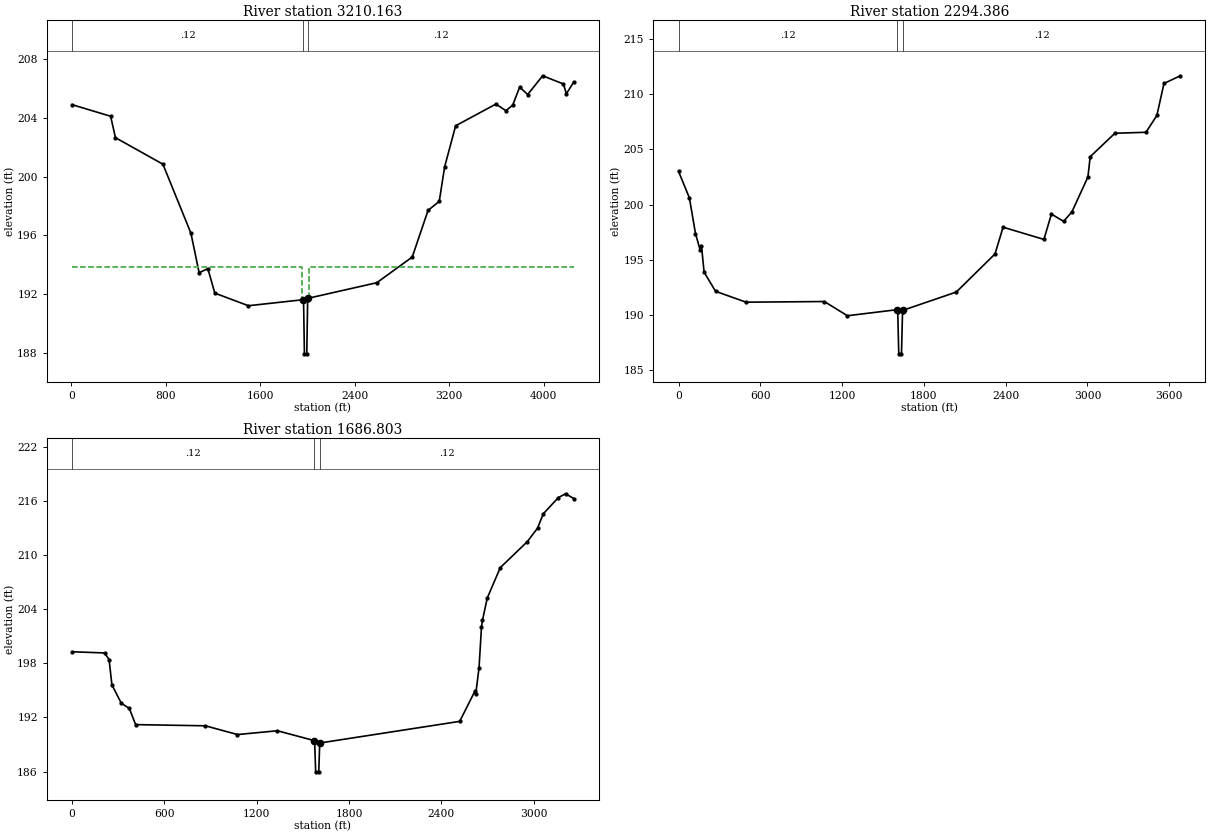
Type RM Length L Ch R = 1 ,3210.163,699.89,915.78,1002.18
XS GIS Cut Line= 4
     1874057.048      390136.942     1872905.718       388715.93
     1872659.309      388438.082     1871357.395      386855.692
#Sta/Elev= 30
    6.22  204.91  332.73  204.12  373.53  202.66  775.52  200.85 1012.53  196.15
 1082.22  193.45 1156.13  193.73 1215.08  192.06 1499.65   191.2 1961.44  191.61
 1966.66  191.51 1973.83  187.92 1993.83  187.92 2001.11  191.56 2006.22  191.71
 2586.93  192.77  2886.9  194.52 3020.85   197.7 3115.73  198.32 3161.31  200.67
 3254.52  203.47 3595.21  204.95 3680.59   204.5    3738  204.88  3796.7  206.11
 3864.19   205.6 3991.55  206.88 4167.52  206.32 4191.85  205.65 4255.61  206.46
#Mann= 3 , 0 , 0
    6.22     .12       0 1961.44     .07       0 2006.22     .12       0
#XS Ineff= 2 , 0
       0 1956.33  193.81 2011.33       0  193.81
Bank Sta=1961.44,2006.22
Exp/Cntr=.5,.3

Type RM Length L Ch R = 1 ,2294.386,519.55,607.58,673.53
XS GIS Cut Line= 3
     1874118.455      390107.531     1874161.857       389933.92
     1873033.385      386617.948
#Sta/Elev= 30
       0  203.01   79.69   200.6  124.41  197.36  158.36  195.88  168.14  196.26
  187.61  193.86  271.49  192.12  495.41  191.13  1069.7  191.19 1239.14   189.9
 1603.98  190.45 1608.19  190.28 1615.87  186.44 1635.87  186.44 1643.52  190.27
 1647.76   190.4 2037.81  192.05 2321.93  195.51 2381.29  197.94  2680.7  196.83
 2735.87  199.13 2825.41  198.47 2886.58  199.34 3003.71   202.5 3020.32  204.34
 3201.59  206.47 3429.79  206.56 3509.77  208.09 3561.52  210.99 3681.68  211.69
#Mann= 3 , 0 , 0
       0     .12       0 1603.98     .07       0 1647.76     .12       0
Bank Sta=1603.98,1647.76
Exp/Cntr=.3,.1

Type RM Length L Ch R = 1 ,1686.803,448.25,1686.8,798.95
XS GIS Cut Line= 6
     1874213.941      390046.767     1874396.232      389855.795
     1874465.677      389742.948     1874144.496      387468.642
     1874222.621      387173.503     1874257.344      386913.087
#Sta/Elev= 30
       0  199.27  211.97  199.14  240.68   198.4  258.84  195.61  320.06  193.57
  372.42  192.99  413.07   191.2  866.47  191.07 1075.06   190.1 1334.51  190.52
 1574.13  189.43 1576.39  189.41 1583.28  185.97 1603.28  185.97 1609.72  189.19
 1612.44  189.17  2519.4  191.56 2618.38  194.91 2623.53  194.56 2645.17  197.51
 2661.04  202.02 2667.44  202.76 2698.26  205.21 2783.14  208.59 2958.46  211.46
 3025.31  212.96 3062.51  214.55 3160.73  216.35 3207.53  216.77 3261.41  216.24
#Mann= 3 , 0 , 0
       0     .12       0 1574.13     .07       0 1612.44     .12       0
Bank Sta=1574.13,1612.44
Exp/Cntr=.3,.1

Chan Stop Cuts=-1

--- jordan.g01 (geometry) ---

Geom Title=Base Geometry
Version=September 1998 Version 2.2

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
River Reach=Jordan_Creek    ,01

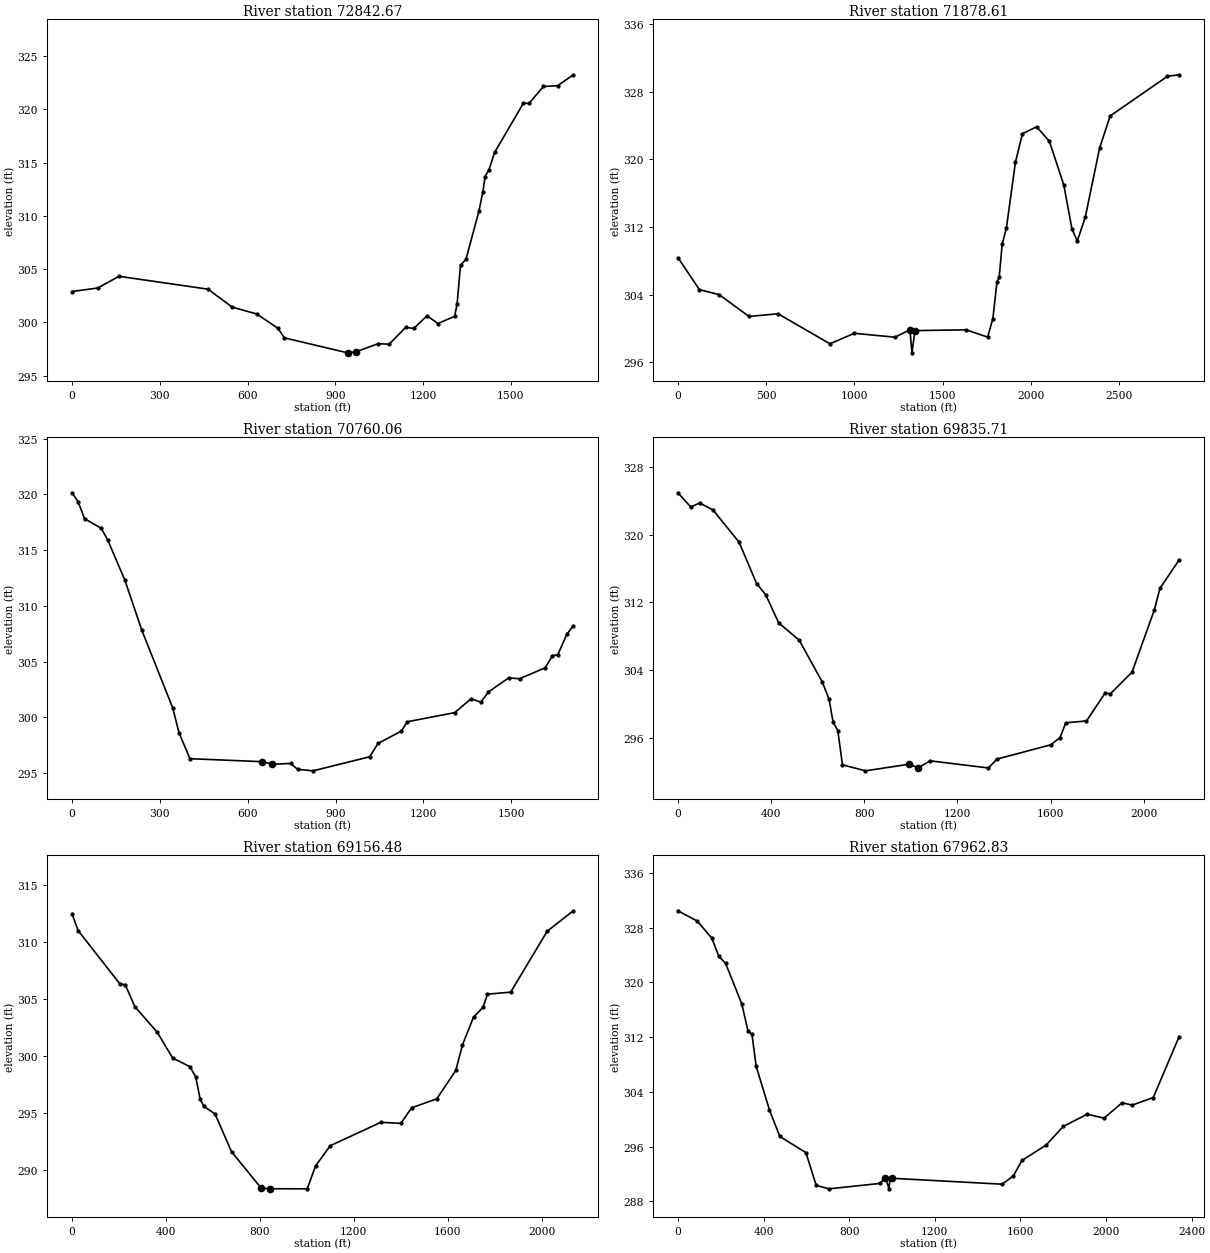
Type RM Length L Ch R = 1 ,72842.67,619.43,964.06,978.73
XS GIS Cut Line= 4
     1845509.903      428919.146      1845035.66       429032.77
     1844336.273      429508.906     1844003.305      429691.734
#Sta/Elev= 30
       0  302.89   87.85  303.22  160.36  304.32  465.08  303.11  547.06  301.43
   631.4  300.78  703.73  299.44  725.64  298.54   942.1  297.13  971.61  297.23
 1046.34  297.99  1084.1  297.94 1140.82  299.53  1168.1  299.42 1213.95  300.61
 1250.72  299.88 1308.15  300.56 1316.47  301.75 1328.07  305.36 1346.89  305.93
 1390.93  310.44 1404.61  312.27 1411.97  313.69 1425.18  314.32 1444.49  315.95
 1543.23  320.59 1562.39  320.56 1611.65  322.15 1659.95  322.22  1713.6  323.25
#Mann= 0 , 0 , 0
Bank Sta=942.1,971.61
Exp/Cntr=.3,.1

Type RM Length L Ch R = 1 ,71878.61,983.71,1118.55,1113.35
XS GIS Cut Line= 6
     1845373.303      428710.156     1844932.844      428777.919
     1844408.602      428854.587     1843740.226      428565.971
     1843591.254      428366.681     1842742.888      428629.234
#Sta/Elev= 30
       0  308.38   121.6   304.6  233.86     304  402.68  301.42  567.17  301.74
  861.52  298.19  999.64  299.43 1229.16  298.97 1315.09  299.83 1326.17  297.12
 1343.49  299.75 1632.71  299.84 1754.95  298.98 1784.79  301.17 1807.93  305.51
 1820.69  306.04  1837.4  309.95 1861.24  311.85 1912.65  319.65  1952.3  323.02
 2032.59  323.84 2104.53  322.15 2186.68  316.96 2232.99  311.75 2263.14  310.34
 2308.31  313.14 2389.34  321.32 2449.43  325.13 2774.09  329.81 2840.37  329.99
#Mann= 0 , 0 , 0
Bank Sta=1315.09,1343.49
Exp/Cntr=.3,.1

Type RM Length L Ch R = 1 ,70760.06,858.19,924.35,734.94
XS GIS Cut Line= 4
     1845576.592      428486.538     1845373.303       428445.88
     1844241.661      427700.487     1844092.582      427693.711
#Sta/Elev= 30
       0  320.14    20.9  319.34   42.64  317.82   99.45  316.96  121.25  315.94
  180.19  312.32  238.37  307.81   343.7  300.86  365.35  298.62  402.61   296.3
  650.15  296.03  684.18   295.8  746.18  295.87  770.18  295.35  822.94  295.21
 1016.45  296.47 1044.85  297.67 1124.33  298.77 1144.82  299.61 1307.03  300.43
 1362.15  301.67 1395.85  301.37 1421.88  302.28 1490.55  303.54 1528.29  303.47
 1615.92  304.45 1640.55  305.53 1658.72  305.63 1689.35  307.44 1711.62  308.22
#Mann= 0 , 0 , 0
Bank Sta=650.15,684.18
Exp/Cntr=.3,.1

Type RM Length L Ch R = 1 ,69835.71,713.19,679.23,662.76
XS GIS Cut Line= 4
     1846373.096      427863.609      1845987.68        427795.9
     1845669.971      427650.067     1844326.221      427217.775
#Sta/Elev= 30
       0  324.95   55.06  323.28   93.93  323.74  150.82  322.92  262.57  319.12
  338.29  314.21  376.78  312.93  432.56  309.61  521.11  307.54  619.13  302.66
  649.38  300.56   666.4  297.87  686.79  296.89  706.54  292.84  805.54  292.13
  992.29  292.91 1032.34   292.5 1083.26  293.31 1333.68  292.47 1369.52  293.51
  1600.5   295.2  1640.8  296.05  1665.7   297.8 1754.53  298.02 1834.23   301.3
 1856.73  301.21 1950.34  303.79    2046  311.14 2069.94  313.67 2152.47  317.03
#Mann= 0 , 0 , 0
Bank Sta=992.29,1032.34
Exp/Cntr=.3,.1

Type RM Length L Ch R = 1 ,69156.48,1252.03,1193.66,991.24
XS GIS Cut Line= 2
     1846315.499      427028.126     1844206.194      426697.974
#Sta/Elev= 30
       0  312.45   25.65  310.98  204.28  306.29  226.57  306.23  267.78   304.3
  362.68  302.07  428.58   299.8  501.93  299.05  526.58  298.16  545.91  296.19
  561.43  295.58  609.35  294.89  679.25   291.6  805.97  288.39  843.28  288.35
 1001.74  288.34 1037.19  290.35 1099.81  292.12 1315.63  294.17 1400.52  294.08
 1446.31  295.44 1553.55  296.23 1634.63  298.72    1663  300.96 1710.26   303.4
 1750.21  304.24 1769.58   305.4 1868.47  305.58 2023.57  310.91 2134.99  312.71
#Mann= 0 , 0 , 0
Bank Sta=805.97,843.28
Exp/Cntr=.3,.1

Type RM Length L Ch R = 1 ,67962.83,1134.32,1158.5,1125.45
XS GIS Cut Line= 2
     1846164.763      425405.275     1844159.555      426613.609
#Sta/Elev= 30
       0  330.48   90.65  328.97  158.77  326.46  190.97  323.83   222.8  322.79
   298.2  316.88  327.24  312.94  346.03   312.4  365.37  307.76  427.51  301.37
  475.81  297.49  597.97  295.12  645.94  290.33  706.02  289.83  943.02  290.62
  969.23  291.44  985.97  289.85  990.35  291.24 1002.01  291.37 1514.39  290.51
 1567.04  291.73 1607.21  293.99 1719.73  296.23 1799.74  298.95 1911.59  300.74
 1990.57  300.17 2074.49  302.41 2122.02  302.07 2220.24  303.18 2341.14  312.09
#Mann= 0 , 0 , 0
Bank Sta=969.23,1002.01
Exp/Cntr=.3,.1