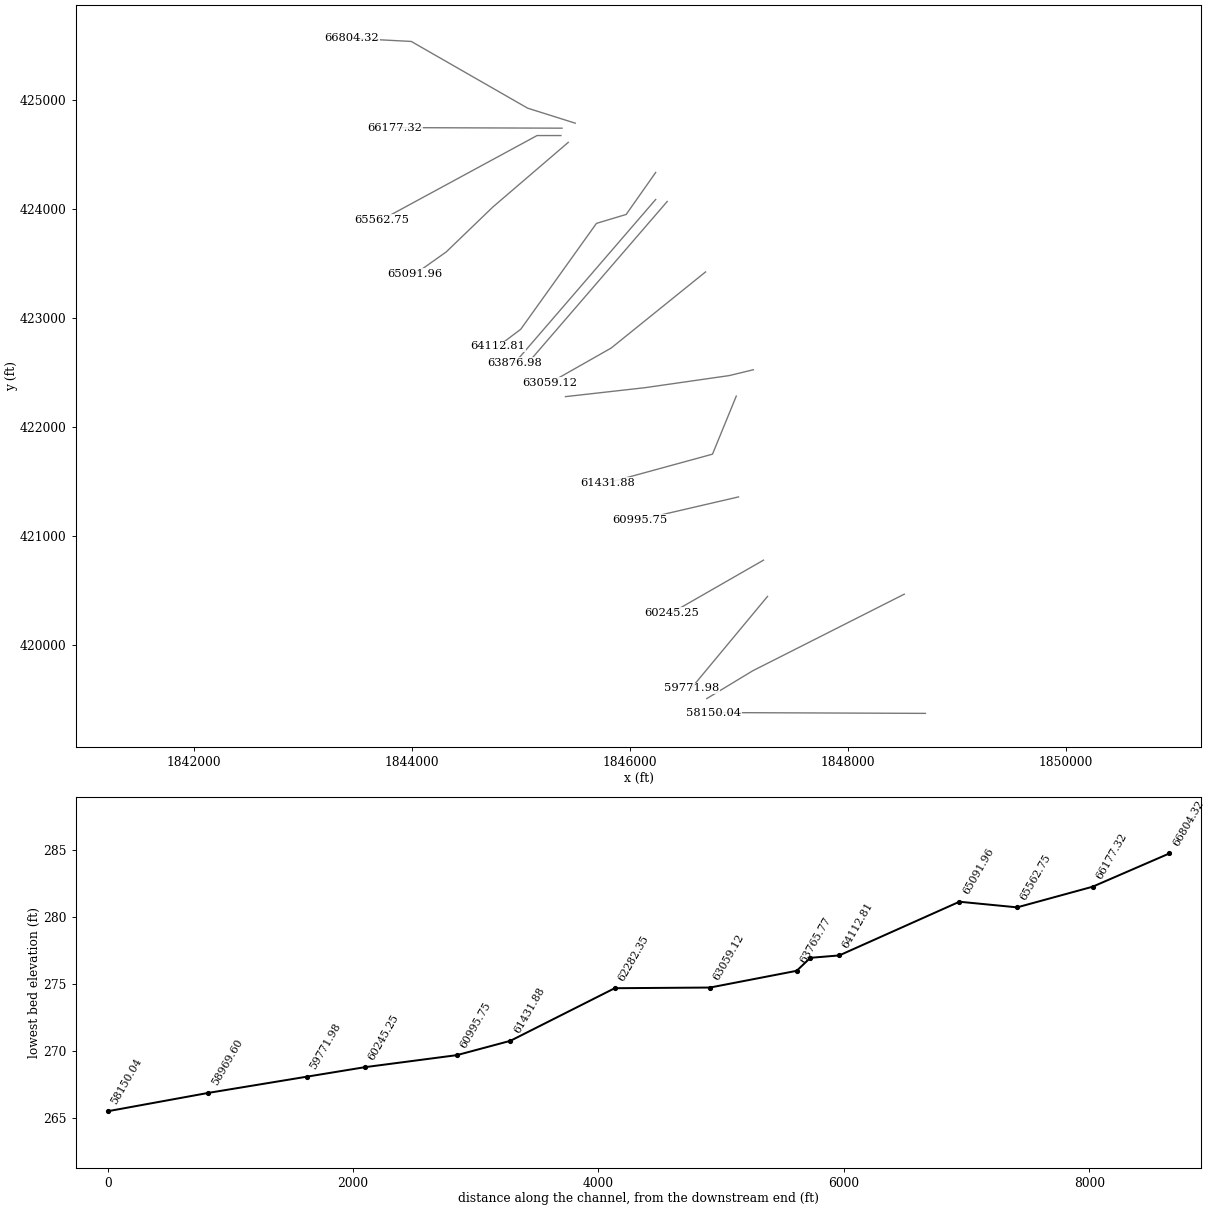
HEC-RAS study jordan.prj: Jordan Creek

--- jordan.g01 (geometry) --- (continued)

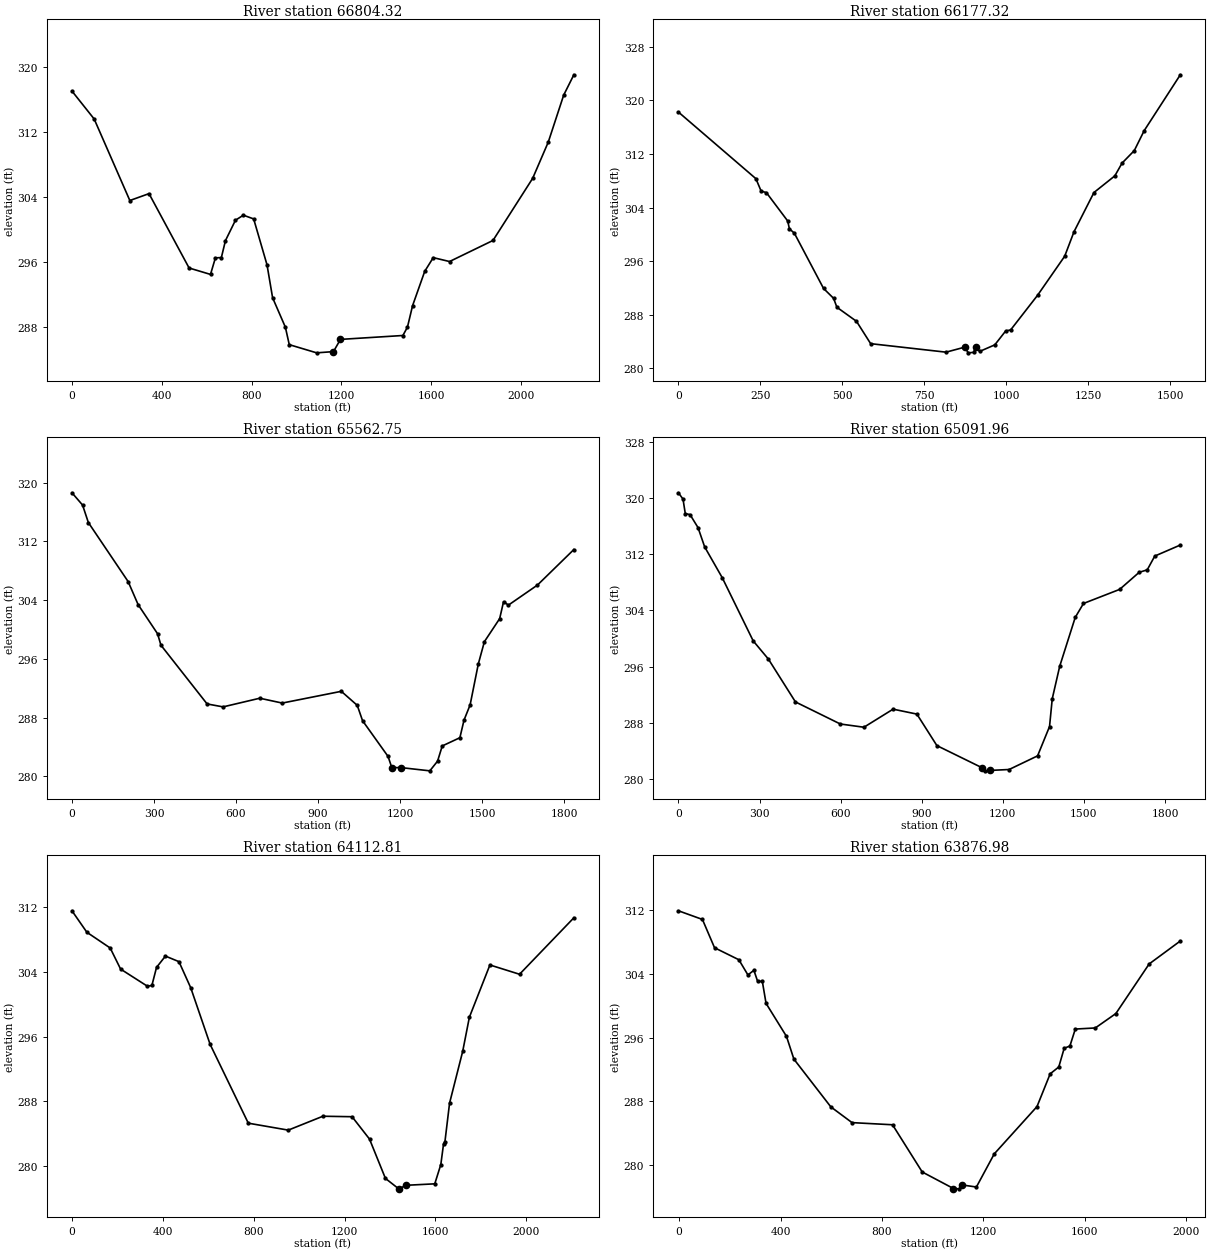
Type RM Length L Ch R = 1 ,66804.32,532.94,627,733.63
XS GIS Cut Line= 4
     1845499.459       424784.52     1845062.737      424922.183
     1843994.664      425534.544     1843448.761      425563.026
#Sta/Elev= 30
       0  317.09   99.03  313.64  257.86  303.58  343.27  304.43  521.87  295.25
  617.19  294.46  638.95   296.5  665.59  296.54  683.74  298.63  728.38  301.15
  763.56  301.77  809.45  301.31  868.95  295.64  893.78  291.58  950.64  287.95
  968.05  285.79 1089.99  284.78 1164.81  284.93 1196.11  286.44 1474.13  286.92
 1494.44  287.95 1517.28   290.6 1571.57  294.85 1609.42  296.53 1682.01  296.05
 1875.45  298.65 2052.28  306.32 2121.74  310.79 2190.43  316.59 2235.71   319.1
#Mann= 0 , 0 , 0
Bank Sta=1164.81,1196.11
Exp/Cntr=.3,.1

Type RM Length L Ch R = 1 ,66177.32,567.08,614.58,660.73
XS GIS Cut Line= 2
     1845378.305      424738.609     1843847.055      424743.817
#Sta/Elev= 30
       0  318.26  236.35  308.31   252.4  306.45  268.39  306.23  333.38  301.99
  338.64  300.82  353.79  300.16  442.78  291.91  473.48  290.43  483.46   289.1
  543.28     287  586.51  283.66   816.5  282.39  872.82  283.13  884.46  282.29
  900.57  282.36  906.51  283.13  919.03   282.5  965.17  283.48  998.45  285.56
 1013.54  285.71 1095.63  290.88 1178.47  296.72 1206.99  300.39 1267.73  306.24
 1331.51  308.73 1353.46  310.63  1390.9  312.51 1420.85  315.47 1531.26  323.83
#Mann= 0 , 0 , 0
Bank Sta=872.82,906.51
Exp/Cntr=.3,.1

Type RM Length L Ch R = 1 ,65562.75,438.46,470.78,478.01
XS GIS Cut Line= 3
     1845367.888        424670.9     1845149.138        424670.9
     1843727.263      423900.067
#Sta/Elev= 30
       0  318.62   38.83  316.95   59.96  314.57   205.5  306.53  242.17  303.38
  313.22  299.42  325.59  297.86  494.43  289.86   552.9  289.46  687.08  290.64
   769.3  289.98  985.41  291.58 1043.74  289.67 1063.12  287.58 1156.48  282.71
 1170.15  281.19 1203.98  281.19 1309.24  280.75 1337.54  282.07 1354.66  284.14
 1419.17  285.26 1434.34  287.66 1456.61  289.73 1486.57   295.3 1508.83  298.34
 1564.71  301.48 1578.96  303.79 1596.74  303.32 1702.94  306.05 1836.13  310.89
#Mann= 0 , 0 , 0
Bank Sta=1170.15,1203.98
Exp/Cntr=.3,.1

Type RM Length L Ch R = 1 ,65091.96,931.33,979.16,955.29
XS GIS Cut Line= 4
     1845435.596        424608.4     1844742.888       424014.65
     1844315.805      423603.192     1844029.346      423400.067
#Sta/Elev= 30
       0  320.71   17.01  319.81   25.36  317.76   43.08   317.6   72.51  315.76
   97.14  313.01  162.31  308.62   276.6  299.65  332.83  297.06  432.89  290.97
  598.94  287.83  686.24  287.37  794.09  289.94  882.04  289.24  956.07  284.76
 1123.22  281.61 1134.66  281.17 1152.92  281.23 1223.27  281.36 1328.57   283.3
 1372.78  287.47 1382.81  291.42 1410.41  296.04 1467.85  302.99 1498.37  304.97
 1632.09  306.97 1704.37   309.4 1734.18  309.75 1762.04  311.71 1856.56  313.28
#Mann= 0 , 0 , 0
Bank Sta=1123.22,1152.92
Exp/Cntr=.3,.1

Type RM Length L Ch R = 1 ,64112.81,255.48,235.83,222.18
XS GIS Cut Line= 5
      1846237.68      424332.359     1845966.846      423946.942
     1845694.088      423864.985     1844999.271      422893.182
     1844792.299      422737.621
#Sta/Elev= 30
       0  311.59   65.67  308.93  168.36  306.98   214.2  304.37   332.1  302.25
  351.87  302.34  372.36  304.58  411.53  305.98  471.06  305.29  522.99  302.05
  608.24  295.05  776.31  285.29  952.29  284.43 1104.73  286.15 1233.14  286.09
 1309.93  283.32 1379.99  278.45 1438.55  277.16 1440.54  277.19 1471.48   277.6
 1597.18  277.78  1623.8  280.17 1635.75  282.71 1641.93     283 1662.27  287.77
 1720.12  294.19 1749.51  298.41 1839.88  304.88 1970.36  303.73 2209.42  310.72
#Mann= 0 , 0 , 0
Bank Sta=1440.54,1471.48
Exp/Cntr=.3,.1

Type RM Length L Ch R = 1 ,63876.98,121.73,111.21,116.47
XS GIS Cut Line= 2
     1846237.454      424084.171     1844944.293      422584.812
#Sta/Elev= 30
   -2.97  311.96   91.76  310.87  139.51  307.31  235.47   305.8  271.24  303.89
  294.75  304.47  309.25  303.11  328.12  303.07  342.77  300.31  423.33  296.16
  452.55   293.3  598.33  287.29  681.95  285.31  841.71  285.04  958.85   279.1
 1082.06  277.02 1104.18  276.98 1115.72  277.47 1172.56  277.21 1243.04  281.38
 1411.66  287.33  1463.6  291.45 1497.53  292.31 1518.83  294.66 1541.46  294.95
 1562.71  297.08  1641.7  297.22 1722.67  299.03 1854.05  305.27 1977.02  308.16
#Mann= 3 , 0 , 0
   -2.97               0 1082.06               0 1115.72               0
Bank Sta=1082.06,1115.72
Exp/Cntr=.3,.1

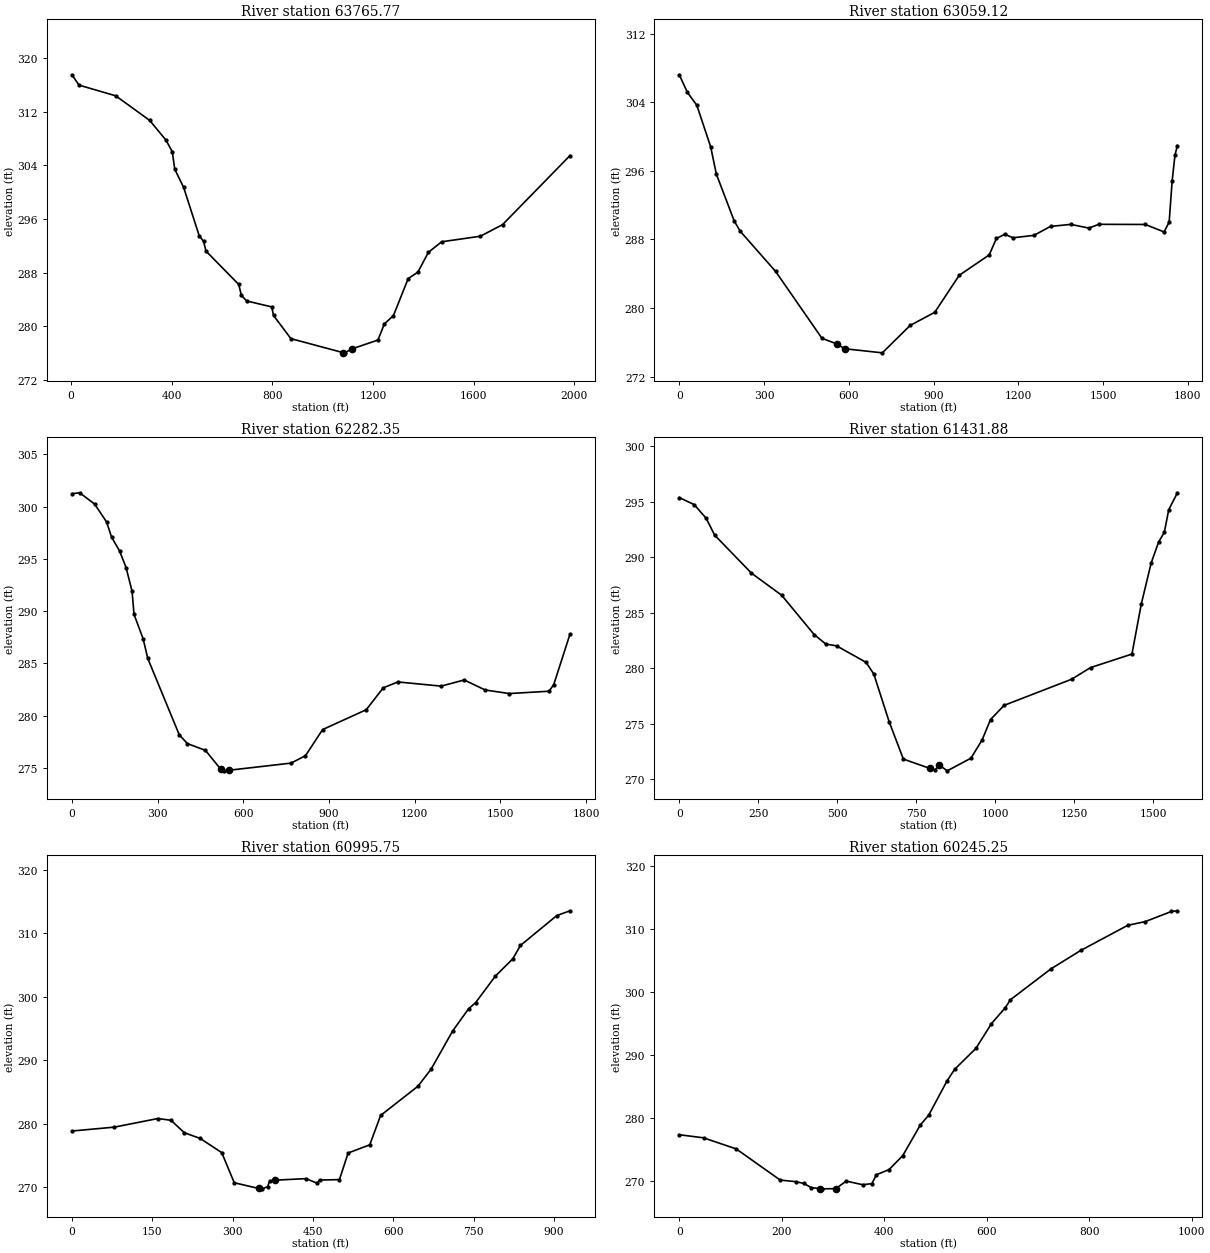
Type RM Length L Ch R = 1 ,63765.77,694.36,706.65,677.38
XS GIS Cut Line= 2
      1846343.37      424065.837      1845050.21      422566.478
#Sta/Elev= 30
    2.97  317.55   31.72     316  177.08  314.41  312.07  310.74  377.11  307.78
  402.22  306.04  411.79  303.45  446.89  300.75     509  293.51  526.24  292.67
  536.07  291.21  666.36  286.22  676.77  284.58  697.81  283.76  797.39  282.87
  804.52  281.59  873.52  278.13 1080.08  276.05 1086.88  276.01  1117.7  276.62
 1219.52  277.92 1244.99  280.33 1281.06  281.57  1339.7   287.1 1378.31  288.07
 1420.03  291.02 1472.71   292.6 1626.65  293.43 1714.69  295.16 1982.95  305.48
#Mann= 3 , 0 , 0
    2.97               0 1080.08               0  1117.7               0
Bank Sta=1080.08,1117.7
Exp/Cntr=.3,.1

Type RM Length L Ch R = 1 ,63059.12,793.72,776.78,673.81
XS GIS Cut Line= 3
     1846695.094      423419.454     1845828.322      422720.379
     1845263.721      422400.067
#Sta/Elev= 30
       0  307.19   28.63  305.14   62.04  303.64  111.11  298.78  131.24   295.6
  194.33  290.15  215.17  288.96  341.01  284.25     505  276.45  557.01  275.81
  585.21  275.24  718.49  274.76  816.78  277.95  904.11  279.49  990.56   283.8
 1096.68  286.18 1122.23   288.1 1151.93  288.59 1180.69  288.18 1254.85  288.46
 1314.05  289.51 1385.72  289.74 1449.58  289.31 1484.81  289.75 1649.22  289.73
 1715.59  288.86 1733.54  290.01 1744.09  294.79 1754.08  297.82 1762.69  298.93
#Mann= 0 , 0 , 0
Bank Sta=557.01,585.21
Exp/Cntr=.3,.1

Type RM Length L Ch R = 1 ,62282.35,782.43,850.47,741.08
XS GIS Cut Line= 4
     1847134.264      422521.971     1846912.979      422468.327
     1846138.966      422357.206     1845409.555      422275.067
#Sta/Elev= 30
       0  301.24   27.13  301.33   79.63  300.25  121.41  298.54  139.16  297.07
  166.79  295.77  189.66  294.17  210.69   291.9  217.52  289.69  249.51  287.34
  265.64  285.47  375.83  278.16   404.2  277.32  467.41  276.67  521.36  274.86
  533.67  274.71     551  274.77  767.22  275.45  817.74  276.16  877.67  278.66
 1030.37  280.56 1090.12  282.66 1141.26  283.22 1292.62  282.82 1373.13  283.41
 1446.58  282.45 1531.02  282.11 1670.16  282.33 1686.67  282.96 1743.66   287.8
#Mann= 0 , 0 , 0
Bank Sta=521.36,551
Exp/Cntr=.3,.1

Type RM Length L Ch R = 1 ,61431.88,432.17,436.13,424.8
XS GIS Cut Line= 3
     1846977.263      422280.275     1846759.021      421747.166
     1845794.109      421483.568
#Sta/Elev= 30
       0   295.4   47.44  294.76   85.34  293.52     112  292.01  228.43  288.59
  323.97   286.6  426.75  283.06   463.8   282.2  497.79  282.04  591.26  280.55
  615.73  279.49  664.43  275.18  709.11  271.84  792.89     271  809.51  270.86
  822.84   271.3  847.97  270.78  923.05  271.92  958.48  273.57  984.93   275.4
    1028  276.68 1241.36  279.03 1301.38  280.08 1432.47   281.3 1462.21  285.83
 1493.67  289.54 1517.17  291.41 1534.92  292.26 1548.86   294.3 1576.32  295.83
#Mann= 0 , 0 , 0
Bank Sta=792.89,822.84
Exp/Cntr=.3,.1

Type RM Length L Ch R = 1 ,60995.75,720.64,750.49,783.07
XS GIS Cut Line= 2
     1846997.698      421354.911     1846091.846      421144.859
#Sta/Elev= 30
       0  278.82   79.18  279.43  160.65  280.79  185.04  280.51  209.88  278.55
  239.52  277.65  279.79  275.41  303.09  270.67  348.71  269.77  354.76  269.71
  365.43  270.04  369.07  270.93  378.46  271.07  437.09  271.32  456.79  270.63
  463.47   271.1  499.45  271.16   515.7  275.36  556.06  276.64  576.31  281.27
  645.96  285.87  670.45  288.55   710.9  294.59  740.47  298.07  753.73  299.05
  790.47  303.22  823.24  305.96  837.28  308.05  905.16  312.76  929.89  313.52
#Mann= 0 , 0 , 0
Bank Sta=348.71,378.46
Exp/Cntr=.3,.1

Type RM Length L Ch R = 1 ,60245.25,408.21,473.27,450.47
XS GIS Cut Line= 2
      1847226.82      420774.502     1846383.513      420290.692
#Sta/Elev= 30
       0   277.4   47.28  276.91  111.12  275.15  197.01   270.2  227.39  269.95
  242.81  269.68  257.42  269.01  274.17  268.85  279.02  268.81  305.47  268.84
  325.83  270.04  358.18  269.46  375.94  269.64  384.84  271.05  409.51  271.87
  436.29   274.1   470.5  278.95  486.99  280.53  522.23  285.89  537.25  287.77
  578.92  291.11  609.39  295.05  636.43  297.58  646.27  298.83  724.78   303.7
  783.51  306.66  875.29  310.65  909.41  311.24  960.53  312.85  972.23  312.96
#Mann= 0 , 0 , 0
Bank Sta=274.17,305.47
Exp/Cntr=.3,.1

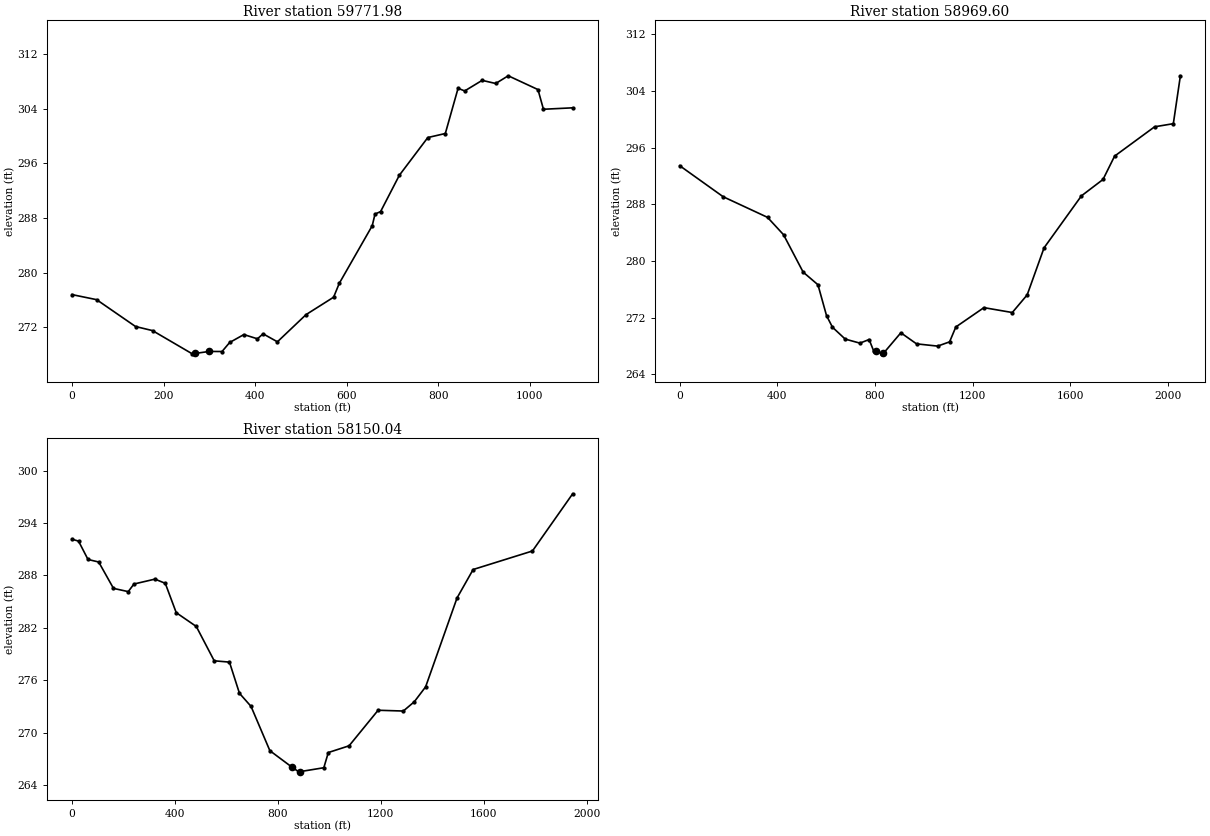
Type RM Length L Ch R = 1 ,59771.98,850.63,802.38,739.07
XS GIS Cut Line= 2
     1847263.816      420441.656     1846565.308      419600.595
#Sta/Elev= 30
       0  276.77    53.7  276.03  138.67   272.1  175.84   271.5  262.59   268.1
  268.95  268.16  299.56  268.45  327.61  268.44  344.23  269.76  375.27  270.92
  404.91   270.3  417.27  271.03  448.53  269.86  511.06  273.84  571.25  276.39
  583.63  278.42  655.58  286.85  661.69  288.56  673.84  288.92  714.84  294.24
  776.99  299.76   815.2  300.35  843.06  306.97   857.5  306.58  895.65  308.13
  925.21  307.67  952.61   308.8 1017.53  306.78 1029.48   303.9  1093.3  304.11
#Mann= 0 , 0 , 0
Bank Sta=268.95,299.56
Exp/Cntr=.3,.1

Type RM Length L Ch R = 1 ,58969.60,839.79,819.56,748.85
XS GIS Cut Line= 3
      1848518.93      420462.567     1847128.305      419759.442
      1846706.43      419504.234
#Sta/Elev= 30
       0  293.44  178.03  289.06  359.77  286.15  425.35   283.7  505.75  278.42
  566.35  276.64  601.61  272.27  625.95  270.64   678.1  268.97  738.28   268.4
  775.99  268.91  794.37  267.32  804.12  267.26  829.47  266.89  834.89  266.97
  906.04  269.86  970.24   268.3 1056.76  267.98 1105.68  268.58 1131.27  270.68
 1246.33  273.41 1362.63  272.72 1423.62  275.21 1492.79  281.85 1645.77  289.18
 1734.38   291.5 1781.75  294.79 1945.65  298.93 2022.47  299.37 2051.34  306.13
#Mann= 0 , 0 , 0
Bank Sta=804.12,834.89
Exp/Cntr=.3,.1

Type RM Length L Ch R = 1 ,58150.04,1016.17,1036.44,1002.52
XS GIS Cut Line= 2
      1848713.18      419368.595     1846767.373      419376.079
#Sta/Elev= 30
       0  292.15    25.4  291.93   62.12  289.83  103.71  289.54  161.17  286.52
  218.53  286.15  240.71  287.02  322.34  287.58  362.47   287.1  405.07  283.74
  483.03  282.16  552.68  278.23  611.93  278.08  650.78  274.51  695.81  273.01
     769  267.94  854.22  266.07  881.27  265.52  885.35  265.54  978.67  265.99
  996.11  267.73 1076.83   268.5 1189.66  272.57 1287.63  272.48 1330.24  273.54
 1374.32  275.25 1496.49  285.43 1558.98  288.68 1789.44   290.8 1945.82  297.35
#Mann= 0 , 0 , 0
Bank Sta=854.22,885.35
Exp/Cntr=.3,.1