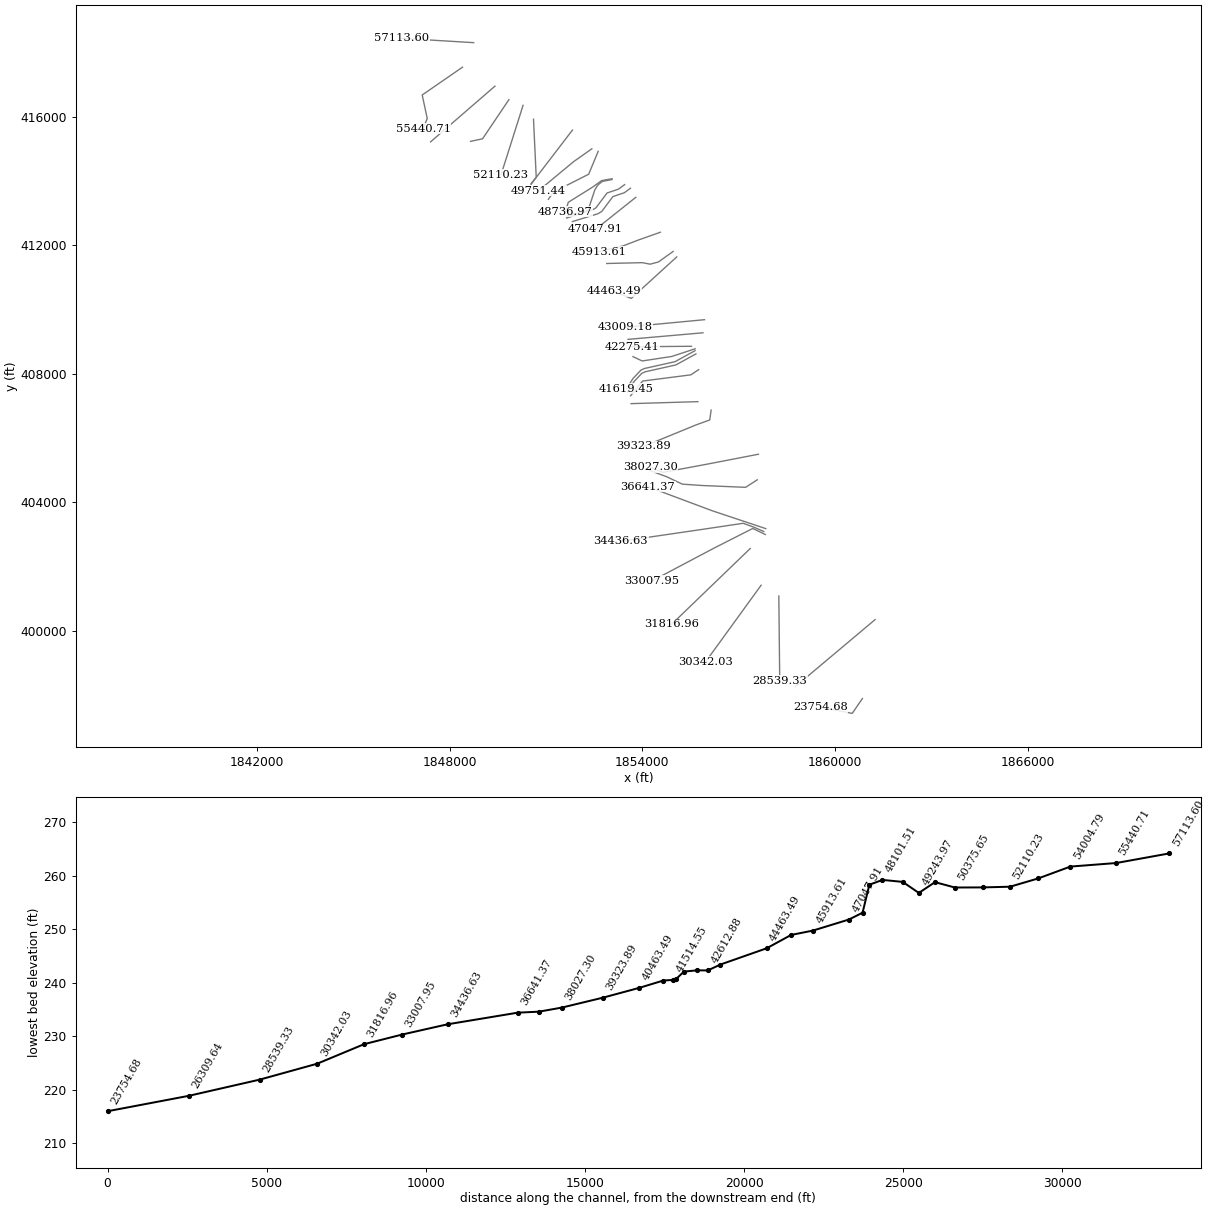
HEC-RAS study jordan.prj: Jordan Creek

--- jordan.g01 (geometry) --- (continued)

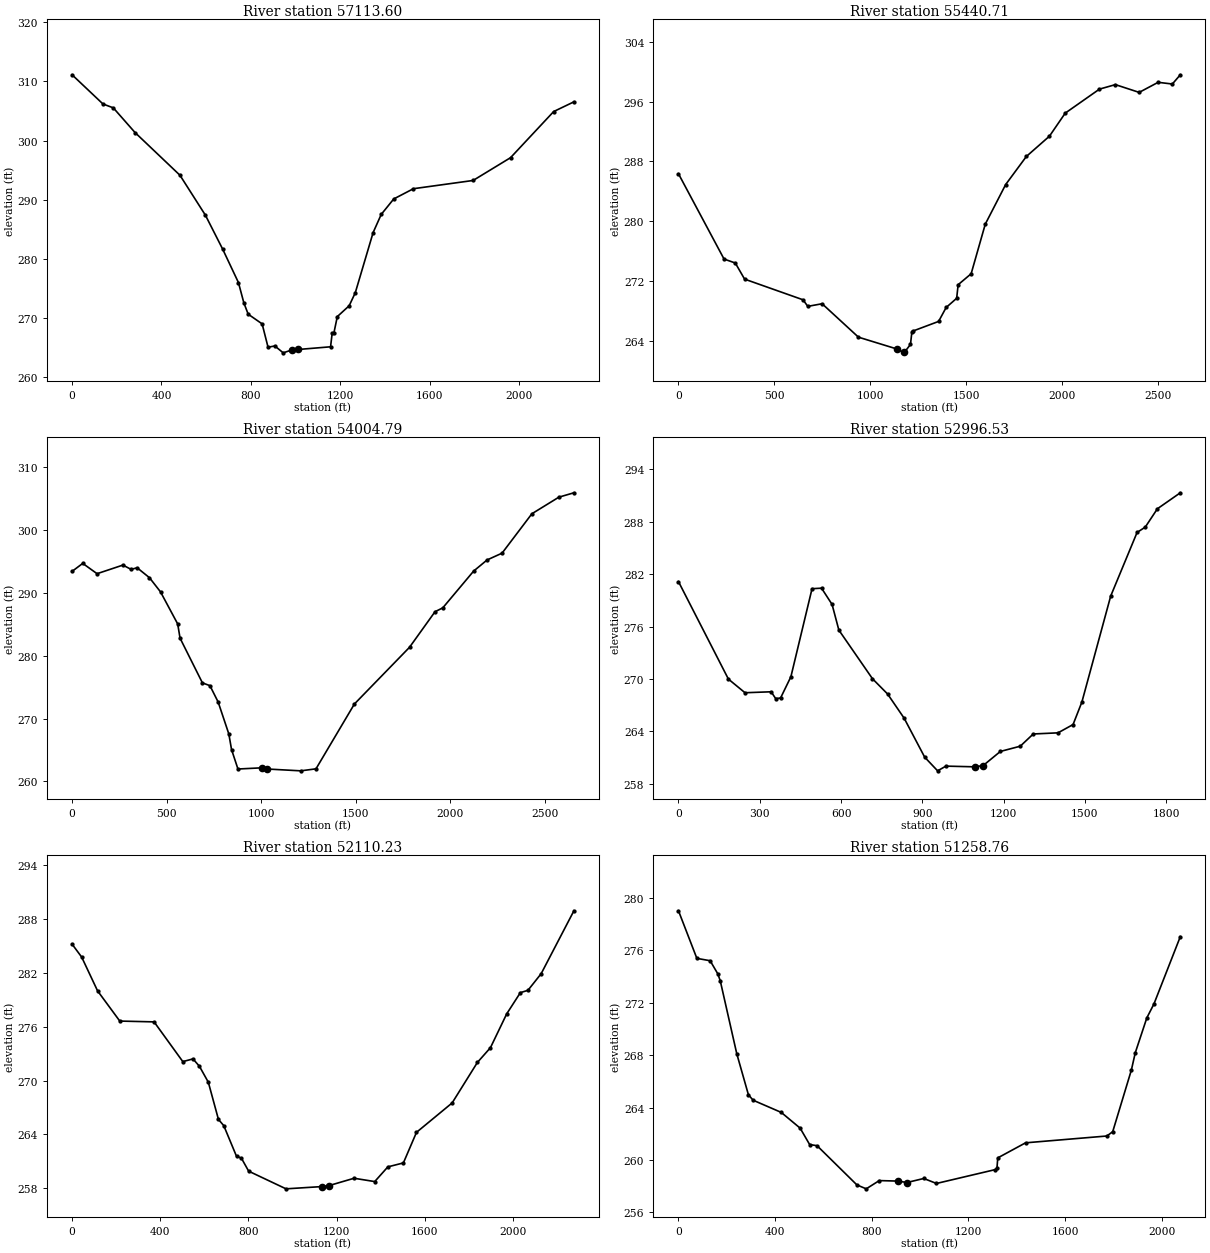
Type RM Length L Ch R = 1 ,57113.60,1520.55,1672.9,1644.62
XS GIS Cut Line= 2
     1848746.349      418313.702     1846505.437      418448.078
#Sta/Elev= 30
       0  311.11  138.14  306.18  184.58  305.52  281.56  301.36  482.63  294.14
  596.56  287.39  674.12  281.63   744.2  276.02  768.37   272.6  787.78  270.68
   850.2  269.04  876.65   265.1  907.09  265.31  944.44  264.15  983.28  264.64
 1012.47  264.72 1156.32  265.17 1163.79  267.55 1171.01  267.46 1186.46  270.27
 1239.55   272.1 1266.93   274.3 1346.69  284.46 1382.99  287.53 1438.94  290.14
 1527.06  291.87 1793.89  293.26 1961.44  297.11 2154.34   304.9 2244.94  306.54
#Mann= 0 , 0 , 0
Bank Sta=983.28,1012.47
Exp/Cntr=.3,.1

Type RM Length L Ch R = 1 ,55440.71,1346.35,1435.92,1360
XS GIS Cut Line= 4
     1848398.858      417550.013     1847142.778      416682.985
     1847300.054      415952.123     1847169.971      415634.442
#Sta/Elev= 30
       0  286.35  237.65  274.92  296.36  274.39  344.84  272.23  649.52  269.46
  674.45  268.58  749.05  268.93  938.54  264.45 1141.07  262.85 1177.17  262.35
 1177.71   262.4 1209.94  263.48 1217.05  265.12 1221.59  265.26 1356.52  266.56
 1395.94  268.43 1450.78  269.66 1458.45  271.48 1526.26  272.95 1599.97   279.6
 1706.37  284.91 1814.21  288.67  1934.6  291.39 2016.95  294.48 2195.61   297.7
 2278.55   298.3 2402.53  297.26 2501.58  298.61 2575.48  298.38 2617.14  299.62
#Mann= 0 , 0 , 0
Bank Sta=1141.07,1177.71
Exp/Cntr=.3,.1

Type RM Length L Ch R = 1 ,54004.79,980.06,1008.26,979.92
XS GIS Cut Line= 2
     1849409.181      416958.787     1847403.502      415222.528
#Sta/Elev= 30
       0  293.44    56.4  294.71  132.15  293.07   268.7  294.44  311.87  293.76
  344.05  294.01  409.17  292.43  467.45  290.18  558.34  285.07  570.76  282.81
  689.04  275.69  728.64  275.25  772.26  272.64  828.54  267.57  842.98  265.08
  876.83  261.98 1002.76  262.17 1031.94  261.98 1208.89  261.69 1289.37  262.01
 1492.46  272.33  1783.9  281.36 1918.57  287.02 1959.51  287.63 2122.53  293.48
 2193.94  295.26 2272.94  296.34 2430.61  302.61 2573.15  305.25  2652.8  305.95
#Mann= 0 , 0 , 0
Bank Sta=1002.76,1031.94
Exp/Cntr=.3,.1

Type RM Length L Ch R = 1 ,52996.53,762.99,886.3,835.66
XS GIS Cut Line= 3
      1849843.97      416537.662     1849023.351      415318.965
     1848649.138      415238.609
#Sta/Elev= 30
       0  281.14   184.3  269.98  245.54  268.42  342.01  268.53  358.68  267.75
  376.79  267.82  414.86  270.25  492.89  280.33     528  280.39  566.81  278.53
   591.9  275.59  715.98  270.02  771.59  268.28  832.69  265.51  908.49  261.05
  956.29  259.48  986.91  260.02 1092.54  259.94 1124.15  260.08 1187.88   261.7
 1261.27   262.3 1309.25   263.7 1400.61  263.83 1456.17  264.78 1488.74  267.36
 1595.07  279.49 1692.39  286.77 1722.59  287.38 1767.38  289.48 1851.97  291.31
#Mann= 0 , 0 , 0
Bank Sta=1092.54,1124.15
Exp/Cntr=.3,.1

Type RM Length L Ch R = 1 ,52110.23,794.84,851.47,829.46
XS GIS Cut Line= 2
     1850284.794      416360.077     1849596.278      414189.753
#Sta/Elev= 30
       0  285.22   43.48  283.78  115.67  280.01   216.5  276.64  372.12  276.55
   502.4  272.12  548.64  272.42  577.76   271.6   618.2  269.82  664.15  265.67
  688.24  264.98  746.41  261.54  767.79  261.37  801.25   259.9   970.7  257.93
 1131.84  258.18 1164.18  258.28 1279.43  259.11 1373.17  258.74 1432.71  260.38
 1503.21  260.82 1562.63  264.23 1724.39  267.51 1839.06  272.03 1898.17  273.67
  1972.1  277.45 2033.98  279.81 2068.32  280.07 2128.19  281.92 2276.92  288.94
#Mann= 0 , 0 , 0
Bank Sta=1131.84,1164.18
Exp/Cntr=.3,.1

Type RM Length L Ch R = 1 ,51258.76,852.49,883.11,516.38
XS GIS Cut Line= 3
     1850610.076      415928.713      1850695.11      414121.734
     1850530.307      413910.598
#Sta/Elev= 30
       0  279.01   76.09  275.38  131.04   275.2  162.73   274.2  172.91  273.67
  241.33   268.1  289.38  264.98  308.84  264.56  425.32  263.63  503.49  262.43
  542.78  261.18  573.55  261.09  738.36   258.1  776.95   257.8  831.05  258.43
  910.45  258.39  944.95  258.28 1015.18  258.59 1067.64  258.21 1311.49  259.27
 1318.15   259.4 1321.26  260.16 1436.41  261.31 1772.87  261.83 1797.02  262.16
 1874.22  266.86 1890.38  268.18  1938.2  270.84  1967.6   271.9 2076.82  277.04
#Mann= 0 , 0 , 0
Bank Sta=910.45,944.95
Exp/Cntr=.3,.1

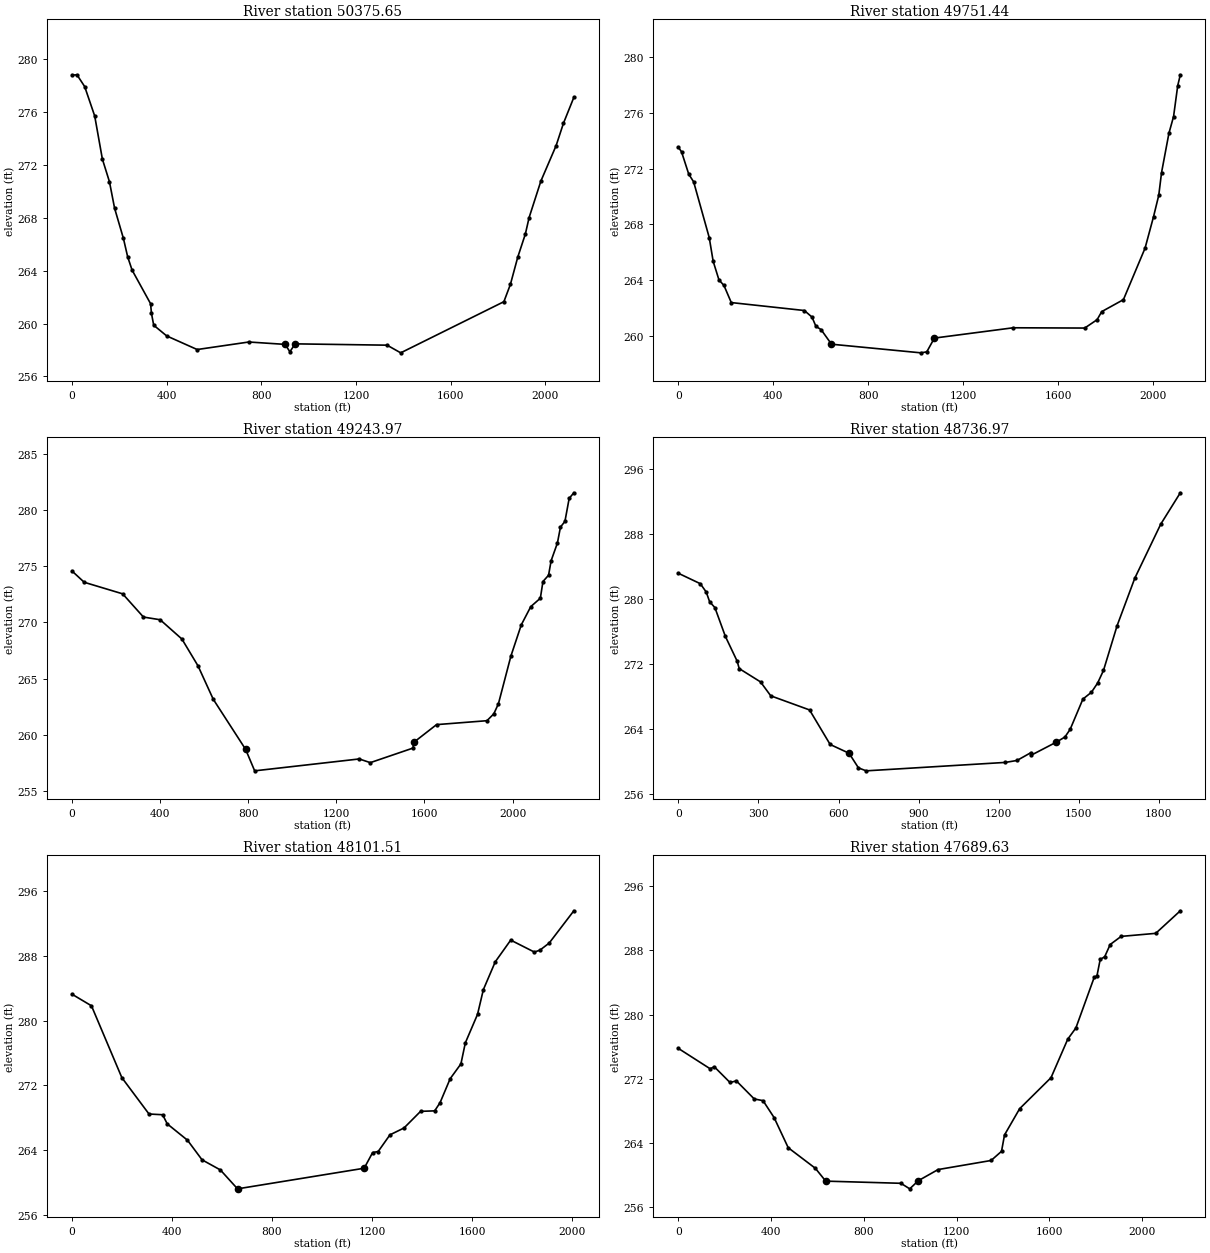
Type RM Length L Ch R = 1 ,50375.65,640.09,624.21,522.64
XS GIS Cut Line= 3
     1851823.617      415590.171     1850697.742      414120.155
     1850537.152      413905.332
#Sta/Elev= 30
       0  278.79   21.11  278.82    53.7  277.93   96.14   275.7  128.53  272.44
  158.35  270.73  180.13  268.72  217.34  266.44  235.43  265.04  254.05  264.04
  332.06   261.5   335.9  260.76  345.34  259.87  400.15  259.06  528.83  258.03
  747.08   258.6   900.5  258.42   920.4  257.86  942.79  258.46 1331.01  258.36
 1388.56  257.78 1824.31  261.65 1851.86  262.96 1882.91  265.02    1915  266.77
 1930.94  268.02 1980.64  270.78 2044.96  273.46 2075.88  275.15 2119.85  277.11
#Mann= 0 , 0 , 0
Bank Sta=900.5,942.79
Exp/Cntr=.3,.1

Type RM Length L Ch R = 1 ,49751.44,543.46,507.47,439.45
XS GIS Cut Line= 3
     1852427.784      415006.838     1851865.284      414611.005
     1850766.326      413699.546
#Sta/Elev= 30
       0  273.54    13.1  273.22   43.61  271.61   64.23  271.06  129.86  267.06
  146.42  265.36  170.85  264.02  191.97  263.62  222.82  262.39  530.73  261.82
  562.93  261.35  579.74  260.68   601.3  260.45  645.25   259.4 1021.97  258.78
 1046.84  258.85 1078.94  259.84 1411.36  260.58 1712.61  260.56 1764.79  261.16
 1784.24  261.74 1875.72   262.6 1966.94   266.3 2002.53  268.55 2024.71   270.1
 2036.46  271.73 2067.52  274.55 2087.07  275.75 2104.62  277.97 2115.56  278.75
#Mann= 0 , 0 , 0
Bank Sta=645.25,1078.94
Exp/Cntr=.3,.1

Type RM Length L Ch R = 1 ,49243.97,438.4,507,484.56
XS GIS Cut Line= 4
     1852625.701      414928.713     1852328.826      414215.171
     1851229.867       413657.88     1851073.617      413433.921
#Sta/Elev= 30
       0  274.59   55.78  273.58  230.12  272.55  324.52  270.48  400.43  270.24
  499.15  268.52  572.15  266.13  641.37  263.15  788.11  258.69  829.33  256.77
 1304.04  257.83 1354.14   257.5 1548.11   258.8 1551.39  259.31 1654.88  260.89
 1883.65  261.24 1914.72  261.85 1935.75  262.75 1992.31     267 2039.59  269.79
 2082.57  271.41 2126.03  272.16 2137.87  273.65 2163.32  274.21 2174.87   275.5
 2203.47  277.08  2217.3   278.5 2237.61  279.01 2256.84  281.06  2278.1  281.56
#Mann= 0 , 0 , 0
Bank Sta=788.11,1551.39
Exp/Cntr=.3,.1

Type RM Length L Ch R = 1 ,48736.97,272.65,635.45,608.5
XS GIS Cut Line= 5
     1853057.992      414074.546     1852735.076      414017.255
     1852443.409      413808.921     1851693.409      413340.171
     1851604.867      413043.296
#Sta/Elev= 30
       0  283.19   81.97  281.91  104.18  280.88  117.01  279.68  136.67  278.96
  175.94  275.41  220.17  272.35  227.79  271.44  307.61   269.8  346.02  268.08
  491.35  266.34  568.58  262.08  639.39     261   674.7  259.19  703.71  258.83
 1225.39  259.87 1268.68  260.11 1321.77  261.09 1322.49  260.77 1416.11  262.37
 1448.17     263 1467.88  263.95 1515.64  267.68  1547.6  268.52 1570.83  269.66
  1592.7  271.21 1643.85  276.74 1709.95  282.58 1807.09  289.24 1880.62  293.12
#Mann= 0 , 0 , 0
Bank Sta=639.39,1416.11
Exp/Cntr=.3,.1

Type RM Length L Ch R = 1 ,48101.51,336.98,411.89,180.76
XS GIS Cut Line= 6
     1853052.784      414048.505     1852755.909      413991.213
     1852615.284      413881.838     1852521.534      413730.796
     1852313.201      413100.588     1851656.951      412913.088
#Sta/Elev= 30
       0  283.29   78.06  281.85  199.53  272.96  308.06  268.46  362.58  268.37
  380.98  267.24  461.89  265.22  520.23  262.79  593.42  261.54  662.04   259.2
  662.23   259.2 1168.41  261.75 1202.19  263.69 1224.36  263.82 1271.42  265.88
 1327.62  266.73 1393.97  268.79 1450.31  268.85  1471.8  269.86 1512.25  272.83
 1555.21  274.66 1572.82  277.26 1621.62  280.79 1644.92  283.85 1692.62   287.3
 1754.33  289.98 1848.86   288.5 1871.11  288.74 1908.05  289.61 2006.77  293.61
#Mann= 0 , 0 , 0
Bank Sta=662.23,1168.41
Exp/Cntr=.3,.1

Type RM Length L Ch R = 1 ,47689.63,216.42,213.52,361.74
XS GIS Cut Line= 6
     1853449.157      413890.694     1853258.659      413750.835
     1852901.776      413630.267      1852554.54      413167.284
     1852433.971      413094.943     1851640.632      412851.395
#Sta/Elev= 30
       0  275.78  136.84  273.25  154.79   273.5  222.51  271.54  249.91  271.74
  327.17  269.49  364.99  269.28  412.76  267.17  473.65  263.42  590.62  260.86
  635.41  259.26  959.75  258.99  997.82   258.3 1034.65  259.31 1120.09   260.7
  1348.7  261.83 1393.71  262.97 1406.66  265.01 1471.95  268.28 1607.26  272.14
 1679.51  276.94 1714.53  278.33 1793.66  284.64 1805.38  284.81 1819.36  286.86
 1838.81   287.2 1862.47  288.72 1909.65  289.73 2058.95  290.11 2164.99  292.92
#Mann= 0 , 0 , 0
Bank Sta=635.41,1034.65
Exp/Cntr=.3,.1

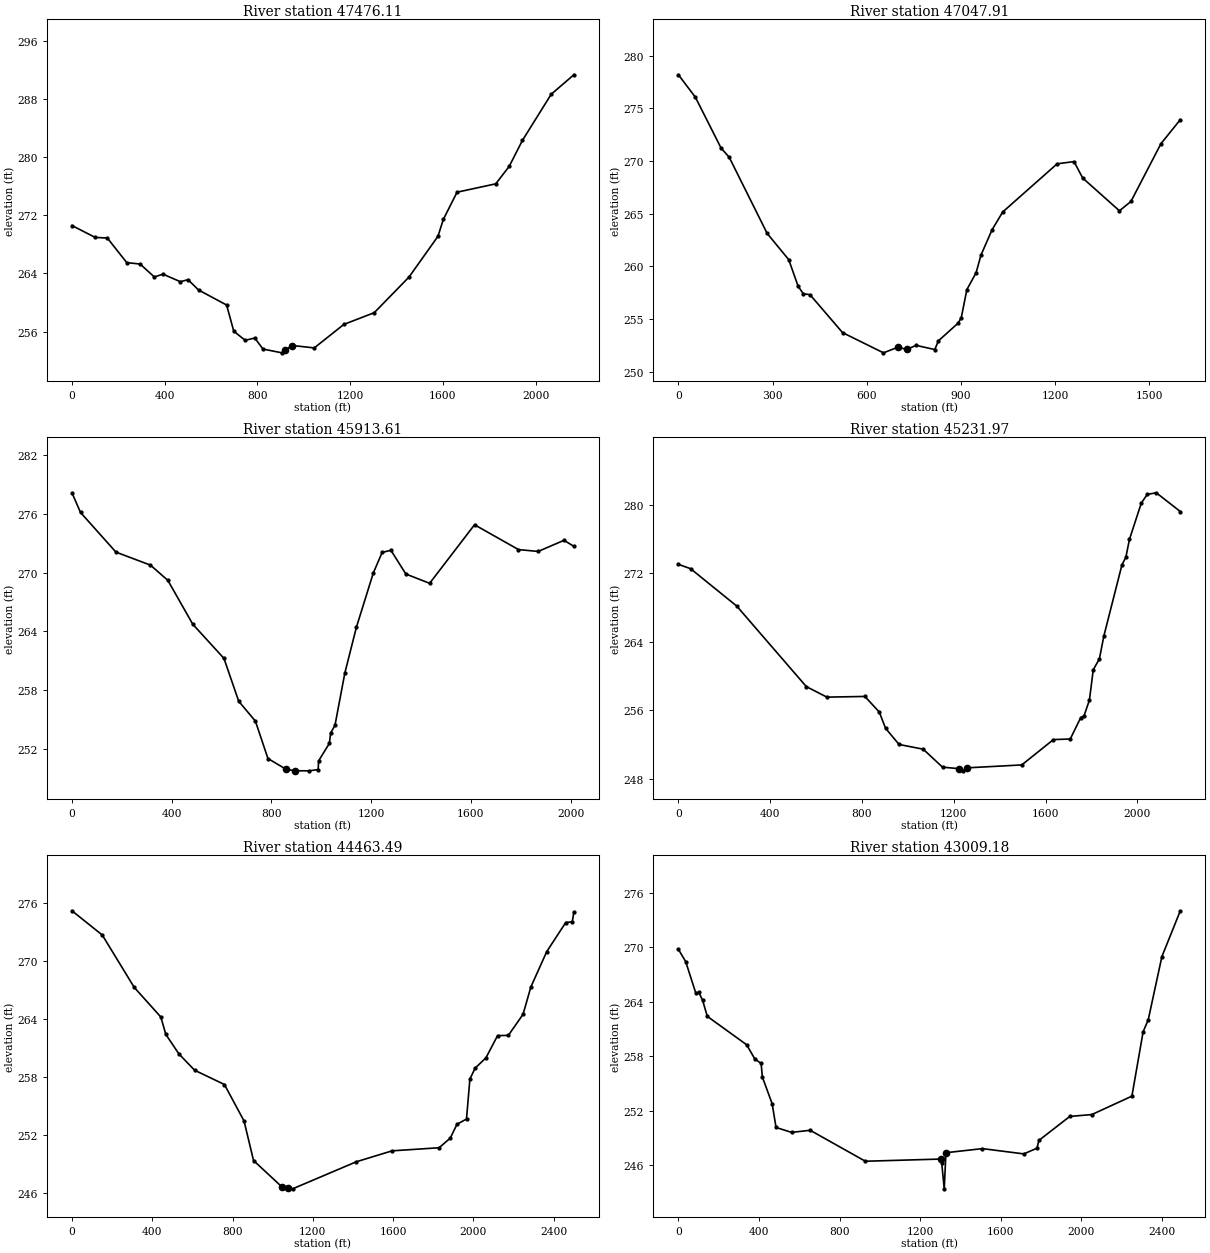
Type RM Length L Ch R = 1 ,47476.11,441.63,428.2,381.81
XS GIS Cut Line= 6
     1853630.658      413778.925      1853440.16      413639.065
     1853083.278      413518.497     1852736.041      413055.515
     1852615.473      412983.174     1851822.133      412739.626
#Sta/Elev= 30
       0   270.6  100.05  268.97  152.68  268.88  236.33   265.5  294.05   265.3
  355.41  263.52   392.6  263.91  467.69  262.87  500.64  263.15  546.07  261.73
  667.15  259.66  697.91  256.07  747.04   254.8  788.52  255.12  824.03   253.6
  905.97  253.08  920.12  253.44  950.43  254.09 1045.36  253.76 1172.73  256.99
 1304.11  258.61 1454.18  263.52 1578.81  269.12 1602.04  271.45 1661.18  275.19
 1828.06  276.34 1885.81  278.73 1943.37  282.33 2067.06  288.66 2164.99  291.35
#Mann= 0 , 0 , 0
Bank Sta=920.12,950.43
Exp/Cntr=.3,.1

Type RM Length L Ch R = 1 ,47047.91,1122.74,1134.31,1079.26
XS GIS Cut Line= 2
     1853796.782      413495.015     1852545.222      412498.748
#Sta/Elev= 30
       0  278.19   54.07  276.06  135.71  271.25  162.07  270.35  282.72  263.14
  351.66  260.64  381.29  258.14  397.82  257.41  419.36  257.32  523.14  253.72
  653.58   251.8  699.06  252.33  727.85  252.13  757.72  252.51  817.04  252.11
  828.72  252.94  891.09  254.61  901.44  255.12  919.32   257.8  948.74   259.4
  964.36  261.08   999.7  263.48 1033.64  265.17 1207.03  269.74  1260.9  269.95
 1288.53  268.39 1405.64  265.28 1442.35  266.17 1537.91  271.65 1599.67  273.93
#Mann= 0 , 0 , 0
Bank Sta=699.06,727.85
Exp/Cntr=.3,.1

Type RM Length L Ch R = 1 ,45913.61,705.66,681.64,637.91
XS GIS Cut Line= 4
     1854563.201       412407.88     1853870.492      412163.088
     1853396.534      411980.796     1852646.534      411803.713
#Sta/Elev= 30
       0  278.17   34.31  276.16  176.47   272.1  314.94  270.77  384.72  269.21
  484.75  264.72  609.73  261.23  668.81  256.85  735.92  254.81  786.07  250.99
  858.21   249.9  893.03  249.74  950.82  249.73  987.56  249.86  989.38  250.75
  1032.7  252.55 1037.48  253.59 1055.04  254.39  1094.6  259.74 1140.96  264.42
  1208.9  269.98 1244.18  272.07  1279.3  272.29 1339.35  269.86 1434.66  268.91
 1614.73   274.9 1791.05  272.36 1869.93  272.17 1973.83  273.31 2013.12  272.69
#Mann= 0 , 0 , 0
Bank Sta=858.21,893.03
Exp/Cntr=.3,.1

Type RM Length L Ch R = 1 ,45231.97,638.19,768.47,859.39
XS GIS Cut Line= 5
     1854959.034      411808.921     1854500.701      411480.796
     1854245.492      411413.088     1853995.492      411459.963
     1852891.326      411433.921
#Sta/Elev= 30
       0  273.04   53.12  272.53  253.93  268.17  557.25  258.76  646.77  257.53
  812.29  257.61  875.02  255.79   902.5  253.89  961.22     252 1066.31  251.45
 1150.57  249.35 1224.47  249.17 1241.92  248.92 1257.27  249.27 1495.77  249.61
 1633.81  252.57 1707.12  252.64 1752.95  255.15 1766.88  255.33 1790.51  257.18
 1807.27  260.73 1834.01     262 1853.34  264.66 1932.43     273 1949.18  273.85
 1964.84  275.95 2016.62   280.2 2042.46  281.21 2081.72   281.4 2186.55  279.21
#Mann= 0 , 0 , 0
Bank Sta=1224.47,1257.27
Exp/Cntr=.3,.1

Type RM Length L Ch R = 1 ,44463.49,1469.72,1454.31,1352.06
XS GIS Cut Line= 3
      1855072.47      411639.273     1853655.435       410346.54
     1853115.284       410564.13
#Sta/Elev= 30
       0  275.19  151.14  272.68  310.19  267.27  442.91   264.2   467.5  262.41
  532.71  260.39   610.9   258.7  759.65  257.22  857.32  253.45  904.61  249.36
 1047.68   246.6 1075.19  246.52 1099.19  246.43 1416.73  249.23 1594.81  250.36
 1829.07  250.68  1884.9  251.68 1918.23  253.11 1965.62  253.65 1982.49  257.78
 2008.43  258.91 2062.51  259.98 2120.46  262.28 2174.12   262.3 2247.53  264.49
 2286.11   267.3 2365.43  270.97 2459.81  273.97 2492.77  274.06 2500.44  275.05
#Mann= 0 , 0 , 0
Bank Sta=1047.68,1075.19
Exp/Cntr=.3,.1

Type RM Length L Ch R = 1 ,43009.18,395.96,396.3,397.06
XS GIS Cut Line= 2
     1855936.546      409683.018     1853456.811      409449.701
#Sta/Elev= 30
       0  269.77   36.11  268.42    86.3  264.95  101.42  265.02  119.94  264.17
  143.33  262.39  338.63  259.26  379.01   257.7  410.52   257.2  416.61  255.71
   465.2  252.76  484.47  250.15  561.36  249.61  653.98  249.84  927.71  246.43
 1300.99  246.67 1306.82  246.21 1319.17  243.39 1327.54  247.37 1508.54  247.82
 1714.02  247.24 1779.64  247.87  1788.6  248.72 1942.44  251.37 2051.34  251.57
 2250.43   253.6  2306.1  260.69 2331.44  262.01 2399.21  268.97 2490.69  274.02
#Mann= 0 , 0 , 0
Bank Sta=1300.99,1327.54
Exp/Cntr=.3,.1

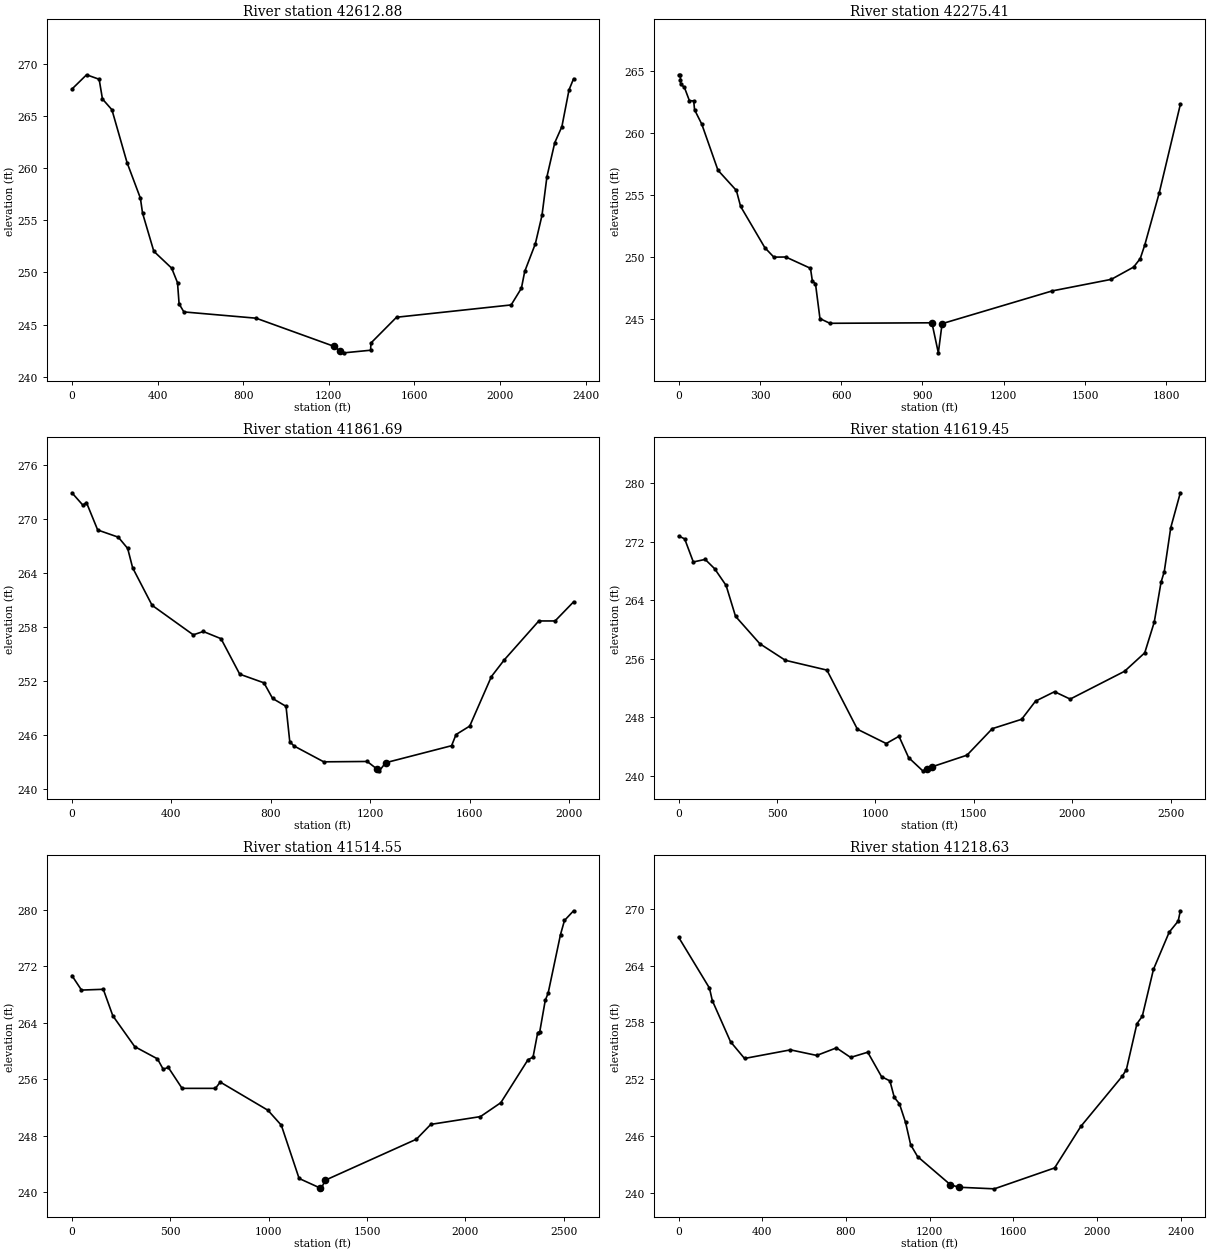
Type RM Length L Ch R = 1 ,42612.88,339.86,337.46,318.32
XS GIS Cut Line= 2
     1855889.721      409275.085      1853554.72      409070.773
#Sta/Elev= 30
       0  267.56   68.38  268.93  127.18   268.5  142.59  266.61  186.84  265.58
  257.47  260.52  319.85  257.11  329.88  255.68  382.57  252.02  466.14   250.4
  493.27  249.01   500.7  246.98  523.04  246.21  860.34  245.61 1223.53  242.92
 1251.65  242.48 1270.91  242.29 1395.48  242.54 1397.09  243.23 1516.66   245.7
 2052.24  246.88 2100.14  248.48 2115.66  250.09 2165.29  252.74 2196.32  255.46
  2219.4  259.16 2255.92  262.42 2289.28  263.96 2322.59  267.48 2343.92  268.55
#Mann= 0 , 0 , 0
Bank Sta=1223.53,1251.65
Exp/Cntr=.3,.1

Type RM Length L Ch R = 1 ,42275.41,386.27,413.73,418.36
XS GIS Cut Line= 2
     1855530.206      408855.117     1853678.434      408839.855
#Sta/Elev= 30
       0  264.71    6.33  264.68    6.45  264.29    7.37  263.95   20.83  263.71
    39.4  262.63   55.44   262.6    58.6  261.89   85.27  260.73  144.96  257.02
  212.97  255.39  228.48  254.11  318.05  250.78   351.3  250.02  395.44  250.03
  486.48  249.12  493.51  248.09  504.96  247.88  521.51  245.07  557.98  244.69
  934.78  244.73   958.5  242.31  972.33  244.66 1379.11   247.3 1596.98  248.23
  1679.4  249.22 1703.82   249.9 1720.47  250.99 1773.53  255.16 1851.84  262.32
#Mann= 0 , 0 , 0
Bank Sta=934.78,972.33
Exp/Cntr=.3,.1

Type RM Length L Ch R = 1 ,41861.69,240.36,242.24,261.37
XS GIS Cut Line= 4
     1855646.534      408777.671     1854917.367      408538.088
     1853995.492      408397.463     1853709.034      408532.879
#Sta/Elev= 30
       0  272.94   44.11  271.56   58.35  271.86  103.51  268.81  186.46  268.01
  224.13  266.76  243.95  264.62  322.19  260.45  487.89  257.17  528.15  257.54
  599.44  256.74  674.66   252.8  772.02  251.84  806.71  250.11  860.76  249.23
  875.87   245.3  893.01  244.83 1012.44  243.07 1187.13  243.11  1228.3  242.23
  1236.1  242.07 1261.19  242.97 1526.42  244.86 1544.39   246.1 1599.38  247.04
 1686.59  252.54    1738  254.38 1877.11  258.71 1942.55  258.71 2016.91  260.83
#Mann= 0 , 0 , 0
Bank Sta=1228.3,1261.19
Exp/Cntr=.3,.1

Type RM Length L Ch R = 1 ,41619.45,105.22,104.89,106.17
XS GIS Cut Line= 6
     1855643.839      408718.536     1855019.165      408375.405
     1854064.069      408162.293     1853955.492      408111.258
     1853705.492      407845.633     1853507.575      407533.133
#Sta/Elev= 30
       0  272.77   30.46  272.37    74.3  269.22  134.65  269.57  182.62   268.3
     241  266.01   288.8   261.8  412.42  258.05  542.07  255.79  753.37  254.45
  908.46  246.37 1054.78  244.42 1119.65  245.41 1168.54   242.5 1240.46  240.69
 1259.52  240.88 1287.57  241.24 1465.28  242.83 1593.82  246.45 1743.02  247.73
  1813.6  250.21 1910.27   251.5 1989.73  250.49 2266.32  254.29 2368.74  256.81
 2417.03     261 2451.66  266.46 2467.87  267.89 2500.88   273.9 2549.64  278.67
#Mann= 0 , 0 , 0
Bank Sta=1259.52,1287.57
Exp/Cntr=.3,.1

Type RM Length L Ch R = 1 ,41514.55,299.99,295.92,273.79
XS GIS Cut Line= 6
     1855669.725      408616.894     1855045.051      408273.763
     1854089.955       408060.65     1853981.378      408009.615
     1853731.378       407743.99     1853533.461       407431.49
#Sta/Elev= 30
       0  270.71    48.6  268.66  159.42  268.77  207.77  265.02  319.12  260.65
  434.63  258.92  463.86  257.45  489.74  257.71  559.83  254.74  729.39  254.74
  753.77  255.63  996.09  251.64  1064.2  249.52 1154.62  241.98 1259.52  240.65
 1266.23  240.51 1287.57  241.73 1750.84  247.54 1824.09  249.64 2076.22  250.74
 2179.84  252.71 2317.82  258.79 2343.59  259.16 2367.28  262.62 2377.67  262.75
 2405.75  267.21 2420.31  268.22 2483.23  276.53 2503.45  278.52 2549.64  279.89
#Mann= 0 , 0 , 0
Bank Sta=1259.52,1287.57
Exp/Cntr=.3,.1

Type RM Length L Ch R = 1 ,41218.63,758.34,755.13,734.23
XS GIS Cut Line= 4
     1855755.909      408126.629     1855511.117      407965.171
     1854011.117      407772.463     1853636.117      407314.129
#Sta/Elev= 30
       0  266.99  147.03  261.63  160.65  260.31  247.77  255.96   314.7  254.19
  534.32   255.1  659.85  254.51  753.96  255.31  821.73   254.3  903.59  254.85
  969.75  252.26  1009.6  251.82 1030.57  250.07 1055.13   249.4 1084.42  247.43
 1108.77  245.07  1141.8  243.82 1298.51  240.85 1338.31  240.58 1508.68  240.41
 1796.81  242.62 1922.22  247.01 2120.79  252.33 2139.92  253.02  2190.2  257.86
 2215.89  258.65 2269.37  263.61 2344.55  267.54 2387.53  268.71 2397.77   269.8
#Mann= 0 , 0 , 0
Bank Sta=1298.51,1338.31
Exp/Cntr=.3,.1

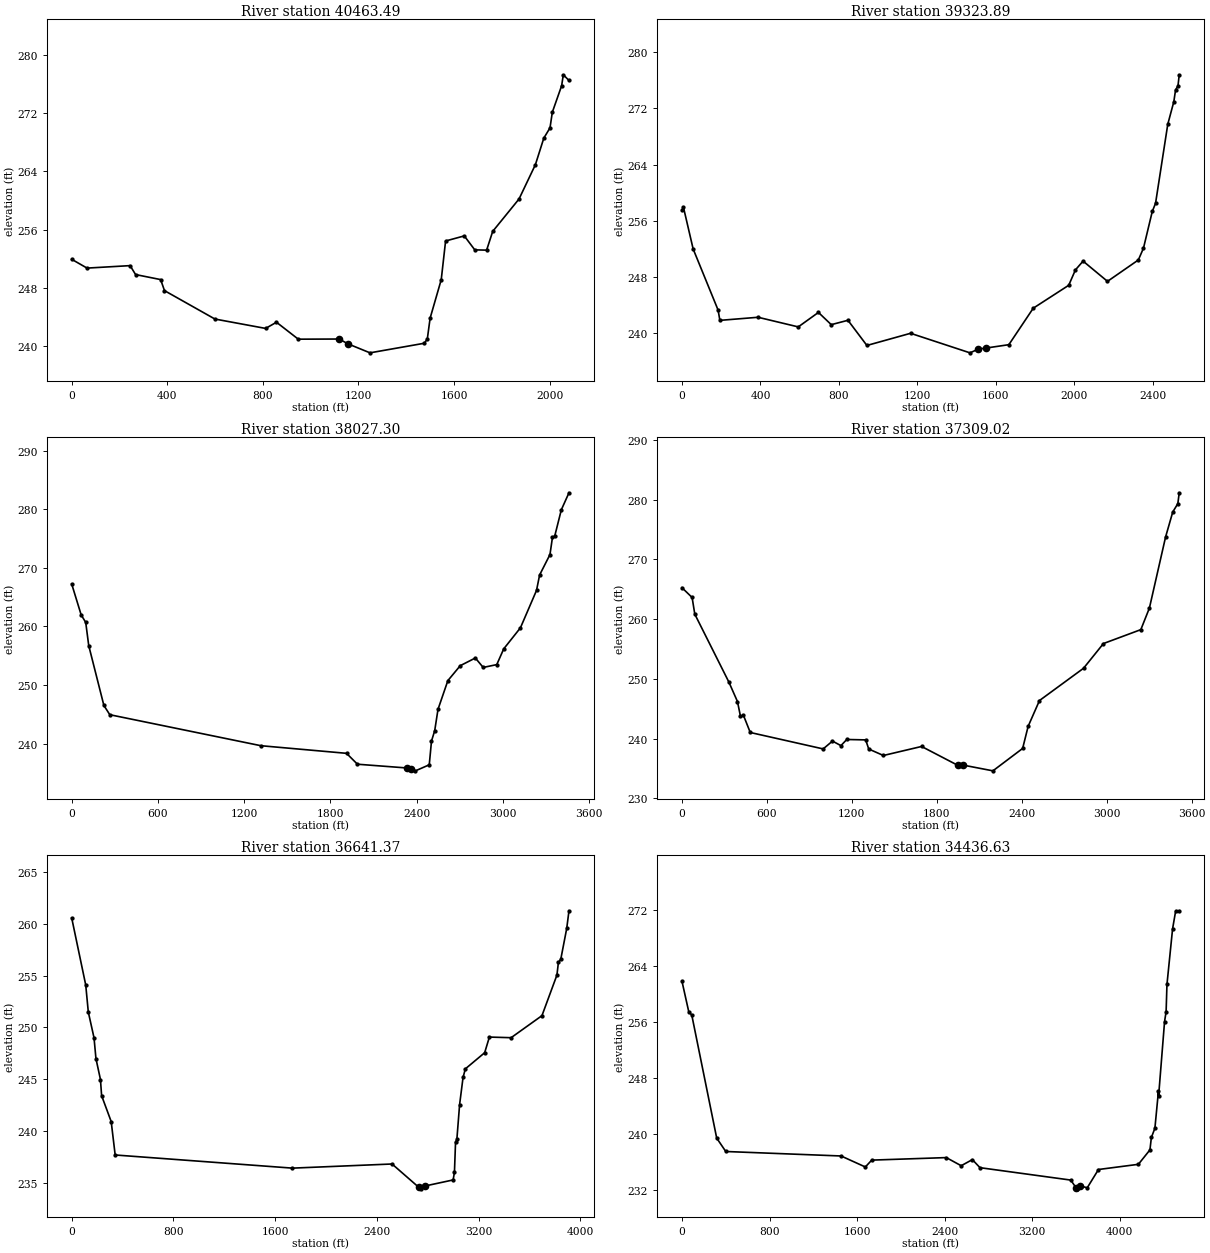
Type RM Length L Ch R = 1 ,40463.49,1055.21,1139.6,1136.71
XS GIS Cut Line= 2
     1855730.044      407129.885     1853649.682      407068.092
#Sta/Elev= 30
       0  251.91   64.16   250.7  244.31  251.04  267.34  249.81  372.17  249.12
   388.3   247.6  599.45  243.69  811.52   242.4  857.06  243.25  948.32  240.92
  1119.4  240.94 1156.72  240.27 1248.47  239.04  1475.9  240.36 1488.39  240.95
 1500.07  243.81 1546.65  249.11 1564.86  254.43 1643.11  255.13 1686.97  253.21
 1736.63  253.17 1762.02  255.75 1872.25  260.21 1940.83  264.94 1975.92  268.58
 2001.92     270 2011.61  272.15 2050.54  275.79 2057.57   277.3 2081.28  276.52
#Mann= 0 , 0 , 0
Bank Sta=1119.4,1156.72
Exp/Cntr=.3,.1

Type RM Length L Ch R = 1 ,39323.89,1234.54,1296.59,1178.82
XS GIS Cut Line= 4
     1856143.506      406867.261     1856100.165      406559.393
     1855664.511      406401.868     1854035.869      405733.579
#Sta/Elev= 30
       0  257.48    7.71   257.9   56.94  251.99   184.2  243.29  193.21  241.83
  387.84  242.27  592.76   240.9  695.56  242.96  760.91  241.22  846.04  241.84
  942.62  238.26 1165.18  239.99 1467.95  237.21 1510.45  237.74 1549.25  237.89
 1666.14  238.37 1790.52  243.56 1971.26  246.82 2005.51  249.01 2044.49  250.26
 2168.95  247.38  2326.1  250.42 2352.33   252.1 2397.15  257.32 2413.93  258.49
 2476.21  269.73 2507.01  272.94 2515.92  274.61  2528.3   275.2 2534.59  276.77
#Mann= 0 , 0 , 0
Bank Sta=1510.45,1549.25
Exp/Cntr=.3,.1

Type RM Length L Ch R = 1 ,38027.30,656.94,718.28,502.28
XS GIS Cut Line= 4
     1857617.465      405492.261     1856059.125      405190.589
     1854643.127      404926.585     1854242.465      405091.219
#Sta/Elev= 30
       0  267.23   65.99  261.95   97.47  260.69  118.38  256.73  223.87  246.51
  265.05  244.93 1316.42  239.64 1912.58  238.34 1988.63  236.48 2332.61  235.84
 2360.29  235.65 2392.24  235.35 2488.42  236.38 2503.99  240.43 2526.32   242.2
 2549.33  245.85 2617.92  250.75  2704.2   253.3 2809.25  254.61 2863.72     253
 2958.31  253.48 3006.75  256.17 3122.95  259.76 3234.88  266.14  3256.5  268.78
  3328.5  272.26  3346.1  275.23 3361.41  275.39 3407.55   279.9 3460.84  282.81
#Mann= 0 , 0 , 0
Bank Sta=2332.61,2360.29
Exp/Cntr=.3,.1

Type RM Length L Ch R = 1 ,37309.02,637.89,667.65,527.26
XS GIS Cut Line= 6
     1857581.006      404695.386     1857216.423      404461.011
     1855857.048      404518.303     1855247.673      404559.969
     1854763.298      404789.136      1854226.84      404987.053
#Sta/Elev= 30
       0  265.25   71.66  263.61   90.62  260.82  331.33  249.45  391.99  246.19
  413.38   243.7  434.02   243.9  482.42  241.01  997.26  238.26 1063.14  239.57
 1122.87  238.81 1164.11  239.84 1297.65  239.77 1319.39  238.24 1422.84  237.16
 1692.55  238.67 1946.27  235.54 1988.05  235.54 2196.44  234.59  2406.4  238.34
 2445.22  242.04  2525.3  246.36 2836.51  251.76  2977.1   255.9 3241.25  258.23
 3301.79  261.84 3416.09  273.74 3466.63  277.92 3502.59  279.32 3512.45  281.14
#Mann= 0 , 0 , 0
Bank Sta=1946.27,1988.05
Exp/Cntr=.3,.1

Type RM Length L Ch R = 1 ,36641.37,1548.57,2204.74,1735.22
XS GIS Cut Line= 3
     1857846.631      403174.553      1856170.23      403733.664
     1854164.099      404485.051
#Sta/Elev= 30
       0  260.56  110.19  254.09  130.42  251.48  175.37  248.99  190.55  246.98
  225.97  244.96  235.03   243.4  310.31   240.9  341.66  237.67 1735.32   236.4
 2518.47   236.8 2730.35  234.53 2742.65   234.4 2775.68  234.67 2998.66  235.26
 3008.96  235.99  3017.6   238.9 3027.93  239.17 3049.55  242.54  3076.6  245.16
 3094.76  245.99 3246.59  247.55 3283.64  249.06 3454.48     249 3697.03  251.13
 3814.69  255.05 3826.27  256.27 3844.89  256.57 3891.73  259.56  3909.4  261.26
#Mann= 0 , 0 , 0
Bank Sta=2730.35,2775.68
Exp/Cntr=.3,.1

Type RM Length L Ch R = 1 ,34436.63,1301.38,1428.67,1326.39
XS GIS Cut Line= 5
     1857784.131      403086.011     1857482.048      403216.219
     1857142.704      403341.383     1855945.069      403162.486
      1853330.45      402779.859
#Sta/Elev= 30
       0  261.86   61.75  257.53   89.66  257.03   317.4  239.47  400.22  237.56
 1454.04  236.92 1675.62  235.35 1734.11  236.33 2415.46  236.69 2551.46  235.53
  2653.6   236.4 2723.32  235.25 3552.81  233.48 3603.42  232.33 3609.41  232.23
 3635.23  232.67 3703.42  232.38 3806.04  234.99 4170.65  235.73 4276.37  237.79
 4289.48  239.56 4321.72  240.88 4354.43  246.23 4355.67  245.49 4410.04  256.11
 4424.22  257.53 4431.89   261.4 4483.34  269.35 4511.04  271.85 4544.03  271.92
#Mann= 0 , 0 , 0
Bank Sta=3603.42,3635.23
Exp/Cntr=.3,.1

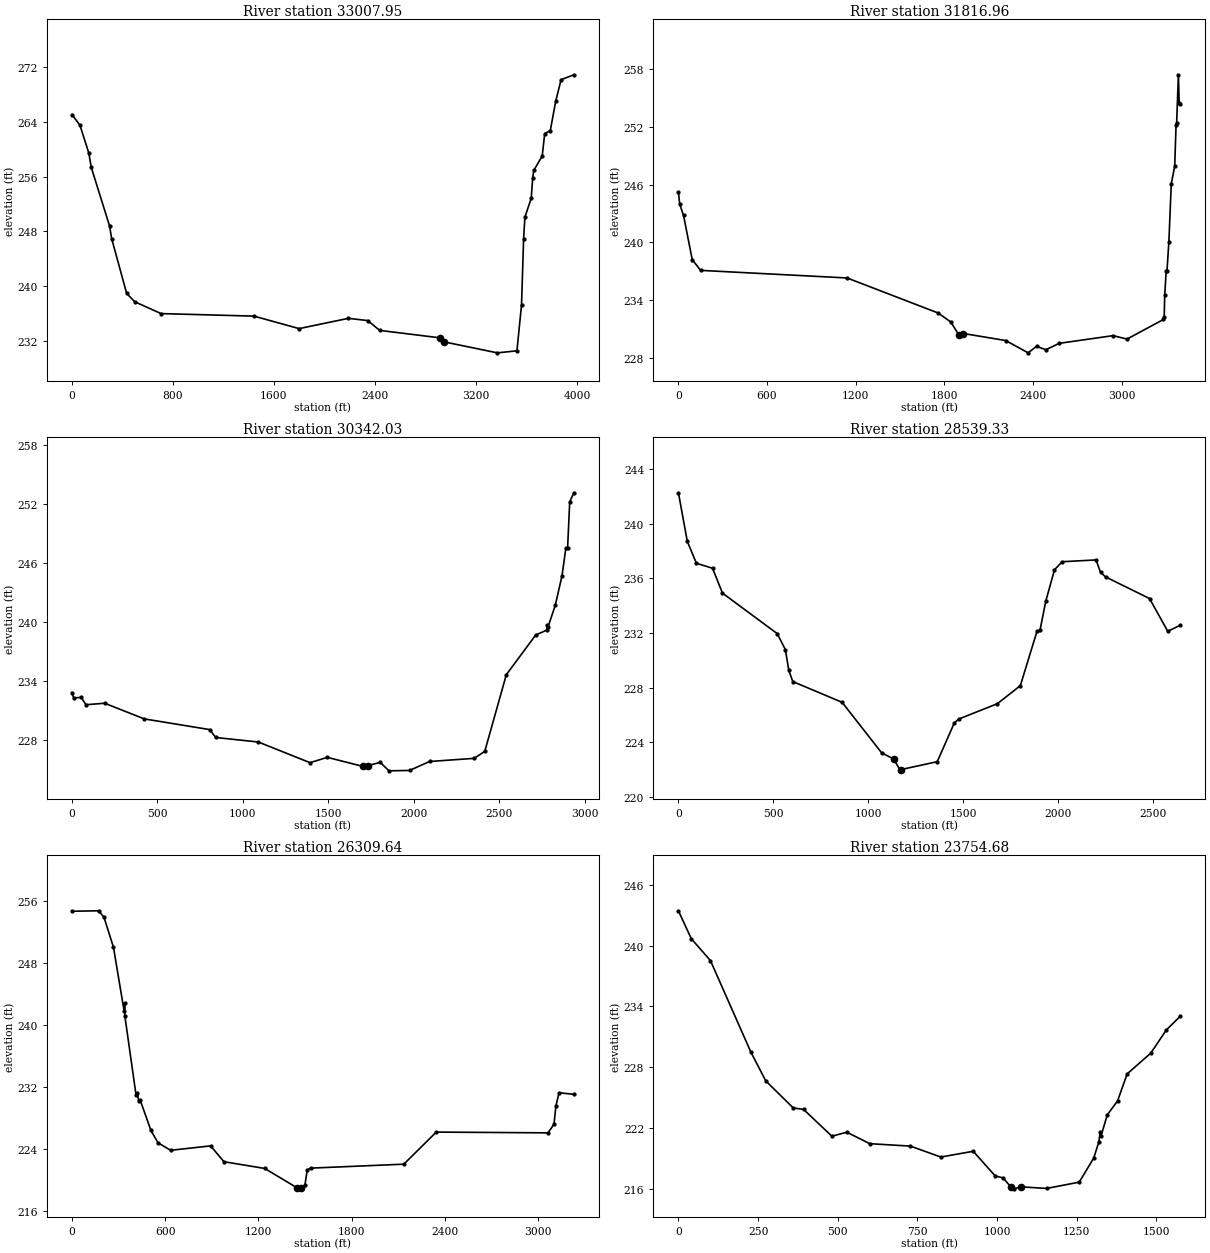
Type RM Length L Ch R = 1 ,33007.95,1153.81,1191,1247.61
XS GIS Cut Line= 4
     1857831.006      402992.261     1857440.381      403179.761
     1856235.895      402568.317     1854298.055      401543.839
#Sta/Elev= 30
       0  265.04   63.66  263.47  133.39  259.43   153.4  257.32   298.1  248.79
   314.4  246.97  433.29  238.97  497.77  237.75   706.2  236.03 1441.68  235.66
 1799.58  233.84 2190.61  235.34 2343.32  235.01 2438.01  233.58 2918.44  232.49
 2950.24   231.9 3369.58  230.31 3525.12   230.6  3561.6  237.31 3578.11  246.97
  3588.2  250.07 3638.45  252.84 3649.75  255.73  3658.5   256.9 3725.41  258.98
 3745.14  262.25 3789.71  262.71 3832.26  266.98 3874.77  270.11 3976.07  270.83
#Mann= 0 , 0 , 0
Bank Sta=2918.44,2950.24
Exp/Cntr=.3,.1

Type RM Length L Ch R = 1 ,31816.96,1402.44,1474.93,1440.1
XS GIS Cut Line= 2
     1857361.978      402555.277     1854915.704      400197.701
#Sta/Elev= 30
       0  245.24    8.68  243.99   34.78  242.81   93.54  238.22  150.17   237.1
 1141.85  236.31 1758.79  232.66 1843.78  231.73 1899.16  230.36 1929.73  230.53
 2215.26   229.8 2367.46  228.52 2424.05   229.2 2487.12  228.84 2577.91  229.51
 2942.42  230.31 3036.45  229.95 3283.03  231.99 3288.31  232.23 3291.69  234.52
 3301.69  237.01 3307.06  237.02 3320.05   240.1 3336.07  246.09 3359.49  247.95
 3368.68  252.25 3372.61  252.46 3384.45  257.45 3389.65  254.55 3397.42  254.38
#Mann= 0 , 0 , 0
Bank Sta=1899.16,1929.73
Exp/Cntr=.3,.1

Type RM Length L Ch R = 1 ,30342.03,1689.44,1802.7,1883.99
XS GIS Cut Line= 2
      1857700.58      401410.734     1855977.087      399033.784
#Sta/Elev= 30
       0  232.83     9.9  232.28   53.79  232.33   82.24  231.59  191.43  231.74
  422.99  230.15  806.27  229.06  840.59  228.26  1090.1   227.8 1392.57   225.7
 1494.02  226.24 1699.97  225.33 1732.26  225.41 1803.27  225.73  1854.5  224.87
 1974.83  224.91  2092.2  225.82 2353.51  226.14 2414.87  226.85 2540.98  234.64
 2713.05  238.68 2779.01  239.18 2781.27  239.65 2784.06  239.45 2827.31  241.69
 2867.06  244.72 2889.45  247.54 2899.37  247.49 2911.83  252.21 2936.04  253.13
#Mann= 0 , 0 , 0
Bank Sta=1699.97,1732.26
Exp/Cntr=.3,.1

Type RM Length L Ch R = 1 ,28539.33,2048.74,2229.69,1968.02
XS GIS Cut Line= 2
     1858252.397      401074.821     1858280.523      398429.336
#Sta/Elev= 30
       0  242.27   46.89  238.71   94.59  237.11  179.91  236.74  232.22  234.92
     521  231.95  563.73  230.78  581.87  229.26  602.92  228.44  862.94  226.92
 1071.67  223.21 1134.98  222.77  1170.3   221.9 1172.02  221.99 1364.18  222.57
 1453.73  225.39 1477.07  225.69 1681.46  226.82 1802.35  228.14 1890.02  232.12
 1906.05   232.2  1936.6  234.34 1982.38  236.63 2022.56  237.22 2201.45  237.35
 2225.01  236.44 2251.42  236.11 2483.56  234.52 2579.41  232.12 2645.63  232.57
#Mann= 0 , 0 , 0
Bank Sta=1134.98,1172.02
Exp/Cntr=.3,.1

Type RM Length L Ch R = 1 ,26309.64,2020.86,2554.96,1924.11
XS GIS Cut Line= 2
     1861251.975      400340.486     1858778.923      398263.094
#Sta/Elev= 30
       0  254.67  171.55  254.73  206.06   253.9  267.14  250.03  335.76  241.81
  339.37  242.85  340.32  241.18  412.72  230.93  421.07   231.2  429.23  230.21
  437.98  230.38  508.12   226.4  553.73  224.81  635.18  223.84  892.32  224.41
  977.81  222.37 1240.31   221.5 1446.95  219.02 1450.43  218.87 1476.01  218.93
 1499.03  219.34 1514.31  221.32 1535.92  221.54 2135.56  222.05  2344.3  226.19
 3063.43  226.09 3102.07   227.2 3114.06  229.53 3134.52  231.26 3229.79  231.06
#Mann= 0 , 0 , 0
Bank Sta=1446.95,1476.01
Exp/Cntr=.3,.1

Type RM Length L Ch R = 1 ,23754.68,495.45,766.93,611.58
XS GIS Cut Line= 3
     1860857.048      397882.886      1860539.34      397419.344
     1859544.548      397612.053
#Sta/Elev= 30
       0  243.45   40.47  240.69  100.51  238.53  227.36   229.5  274.13  226.65
  360.44  223.98  393.07  223.83  481.49  221.19  528.77  221.58   600.5  220.45
  728.05  220.21  823.67  219.13  925.24   219.7  994.13  217.27  1018.9  217.07
 1044.39  216.14 1053.76  215.99 1074.32  216.19 1155.61  216.03 1257.93  216.65
 1303.52  219.03  1319.4  220.61 1323.98  221.64 1326.39  221.21 1346.12   223.3
 1378.25  224.67 1408.39  227.34 1482.75   229.4 1531.36  231.68 1575.26  233.04
#Mann= 0 , 0 , 0
Bank Sta=1044.39,1074.32
Exp/Cntr=.3,.1