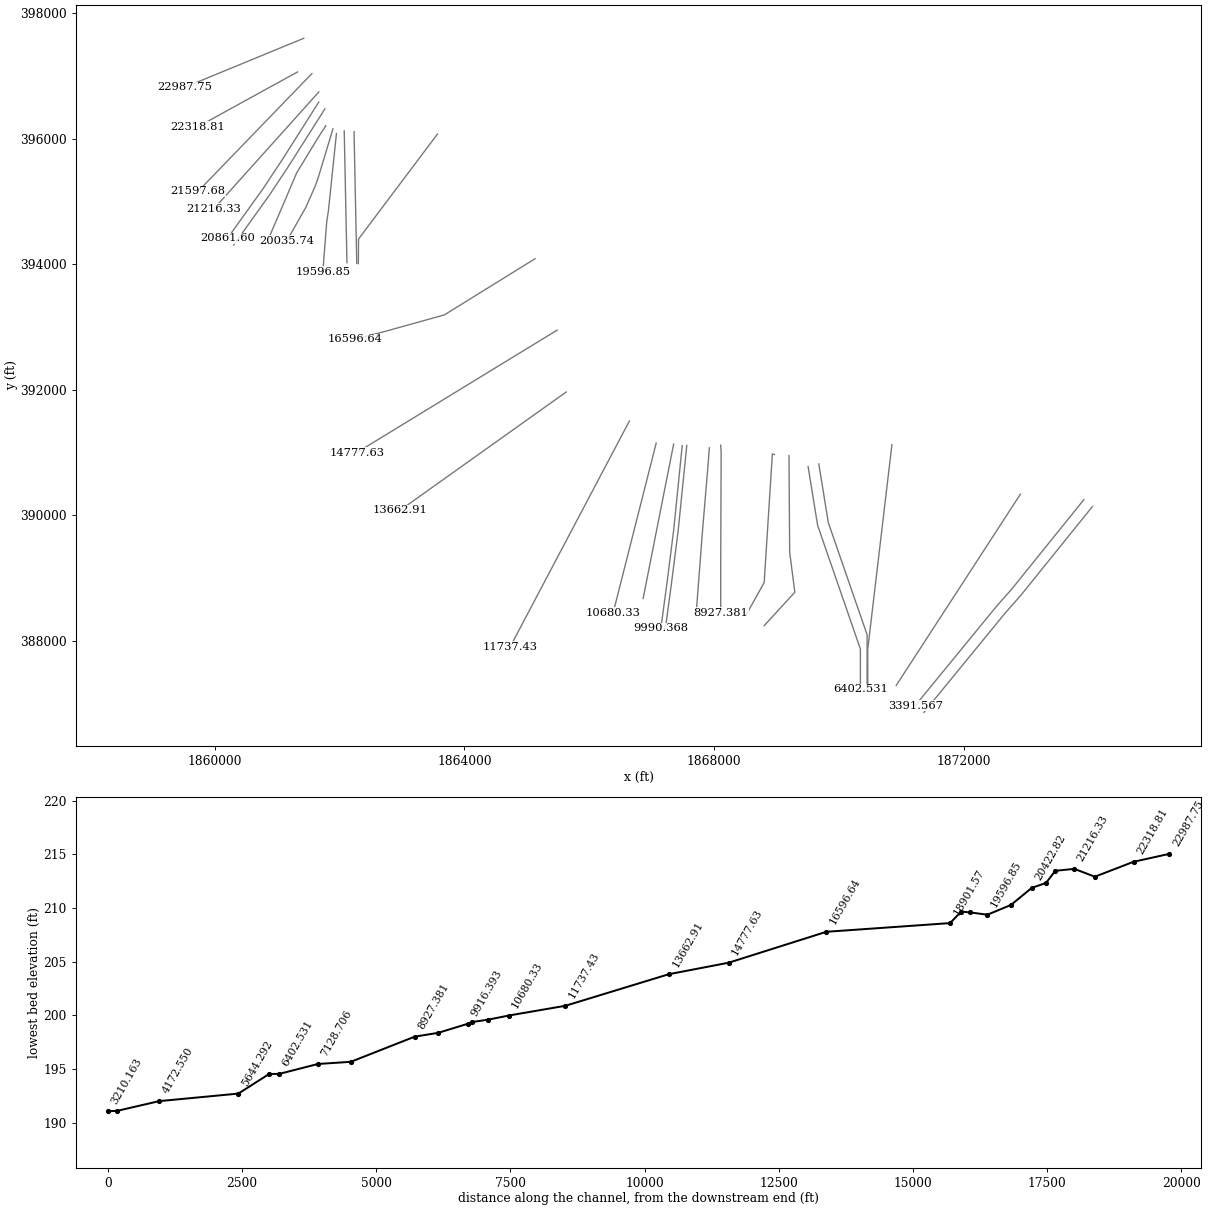
HEC-RAS study jordan.prj: Jordan Creek

--- jordan.g01 (geometry) --- (continued)

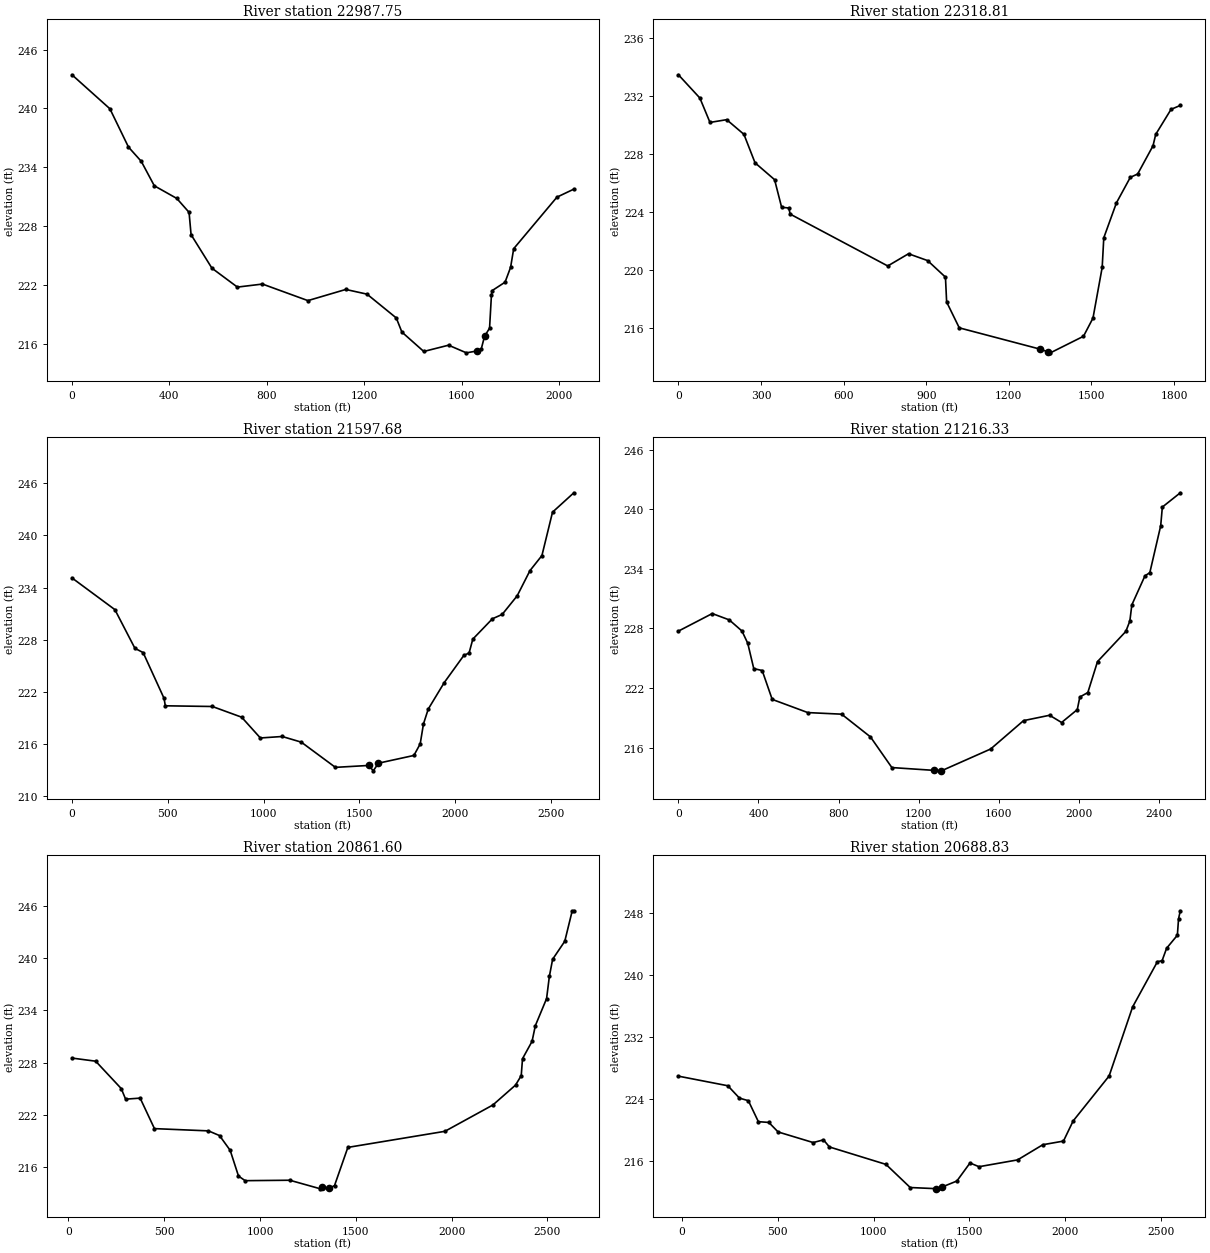
Type RM Length L Ch R = 1 ,22987.75,599.82,668.94,619.75
XS GIS Cut Line= 2
     1861424.756      397601.636     1859518.506      396820.386
#Sta/Elev= 30
       0  243.43  155.76  239.96  232.05  236.05   284.4   234.6  338.08   232.1
  430.29  230.81  480.71  229.39  488.97  227.11  574.58  223.69  679.06  221.76
  782.02  222.07  968.53  220.38 1123.99  221.52 1211.18  221.04 1331.28  218.61
 1354.26  217.17 1444.06  215.19 1545.91  215.83 1619.02  215.05 1664.59  215.25
  1679.9  215.43 1693.43  216.73 1714.15  217.57 1721.93  220.99 1725.31  221.41
 1777.72  222.26 1800.52  223.78 1813.18  225.68 1990.71  230.94 2060.13  231.76
#Mann= 0 , 0 , 0
Bank Sta=1664.59,1693.43
Exp/Cntr=.3,.1

Type RM Length L Ch R = 1 ,22318.81,589.84,721.13,658.69
XS GIS Cut Line= 2
     1861325.798      397065.178      1859726.84      396190.178
#Sta/Elev= 30
       0  233.45   77.89  231.85  114.66  230.17  175.28  230.36  237.93  229.35
  278.29  227.39  349.22  226.23  374.78  224.33  400.79  224.28  405.84  223.86
   760.2  220.29  835.62  221.13  904.97  220.66   969.8  219.52  974.06  217.81
 1019.96  216.03 1312.36  214.57 1343.34  214.37 1350.83  214.31 1471.08  215.45
 1505.53   216.7 1538.95  220.19 1544.79  222.23 1590.87  224.64 1641.12  226.39
 1667.78  226.62 1723.51  228.56 1733.42  229.35 1789.06  231.07 1822.72  231.34
#Mann= 0 , 0 , 0
Bank Sta=1312.36,1343.34
Exp/Cntr=.3,.1

Type RM Length L Ch R = 1 ,21597.68,356.74,381.35,391.7
XS GIS Cut Line= 2
     1861555.986      397039.143     1859730.344      395159.805
#Sta/Elev= 30
       0  235.11  224.17  231.46  328.76  227.01  371.63  226.52  480.93  221.25
  487.39   220.4  733.03  220.32  885.88  219.09  983.56   216.7 1097.56  216.87
 1197.19  216.22 1375.27  213.32 1549.25  213.54 1573.13  212.92    1600   213.8
 1785.07  214.69 1817.95  216.02 1835.07  218.32  1860.1  220.03 1943.48  223.07
 2045.65  226.19 2073.21  226.48 2092.65  228.07 2194.99  230.41 2245.92  230.91
 2323.99  233.04 2391.09  235.95 2453.42  237.68 2508.73  242.67 2620.09   244.9
#Mann= 0 , 0 , 0
Bank Sta=1549.25,1600
Exp/Cntr=.3,.1

Type RM Length L Ch R = 1 ,21216.33,337.09,354.73,360.32
XS GIS Cut Line= 2
     1861667.328      396746.496     1859987.729      394885.319
#Sta/Elev= 30
       0  227.73  169.06   229.5  254.01  228.86  317.43  227.74  346.24  226.51
  376.39  223.95  418.42  223.76  468.42  220.85  646.26  219.52  815.27  219.36
  959.23  217.07 1066.15  213.98 1274.63   213.7 1313.43  213.65 1559.61  215.85
 1723.97  218.71 1854.06  219.25 1914.01  218.52 1992.35  219.82 2005.07  221.09
 2044.99  221.54 2093.38  224.66 2234.89   227.7 2254.94  228.75 2264.79  230.37
  2330.3   233.3 2354.61  233.62 2409.01  238.35  2417.2  240.23    2507  241.67
#Mann= 0 , 0 , 0
Bank Sta=1274.63,1313.43
Exp/Cntr=.3,.1

Type RM Length L Ch R = 1 ,20861.60,163.2,172.77,156.81
XS GIS Cut Line= 4
     1861666.332      396585.059     1861084.307      395671.693
     1860780.515      395213.962     1860203.932      394413.273
#Sta/Elev= 30
    18.8  228.52  142.54  228.16  275.99  225.01  298.83  223.79  374.67  223.91
  449.28   220.4  731.27  220.14  788.85   219.6  844.48   217.9  887.89  214.94
  922.62  214.41 1155.51  214.46 1315.73  213.47 1325.73  213.72  1359.1  213.51
 1388.88  213.84 1458.61  218.24 1965.03  220.09 2215.41  223.12 2333.62  225.41
 2363.31   226.5 2370.01  228.45 2419.75  230.44 2436.95  232.25 2495.56  235.36
 2510.09  237.92 2527.15  239.89 2590.49  241.96 2629.06  245.44  2637.9  245.47
#Mann= 3 , 0 , 0
    18.8               0 1325.73               0  1359.1               0
Bank Sta=1325.73,1359.1
Exp/Cntr=.3,.1

Type RM Length L Ch R = 1 ,20688.83,211.44,266.01,254.67
XS GIS Cut Line= 4
      1861764.92      396477.668     1861182.895      395564.302
     1860879.104      395106.571      1860302.52      394305.882
#Sta/Elev= 30
   -18.8   226.9  239.12  225.66  299.89  224.06  346.15  223.73  398.36  221.02
     453  220.92  501.45  219.69  684.45  218.32  738.13  218.67  769.31  217.75
 1064.25   215.5 1190.88  212.51 1327.42  212.36 1335.86  212.34 1357.42  212.58
  1434.2  213.35  1502.8  215.68 1549.91   215.2 1751.12  216.08 1882.77  218.04
 1990.52  218.51 2040.99  221.11 2228.68  226.92 2351.39  235.85 2480.97   241.7
    2505  241.81 2528.81  243.43 2584.91  245.11 2591.08  247.25  2600.3  248.27
#Mann= 3 , 0 , 0
   -18.8               0 1327.42               0 1357.42               0
Bank Sta=1327.42,1357.42
Exp/Cntr=.3,.1

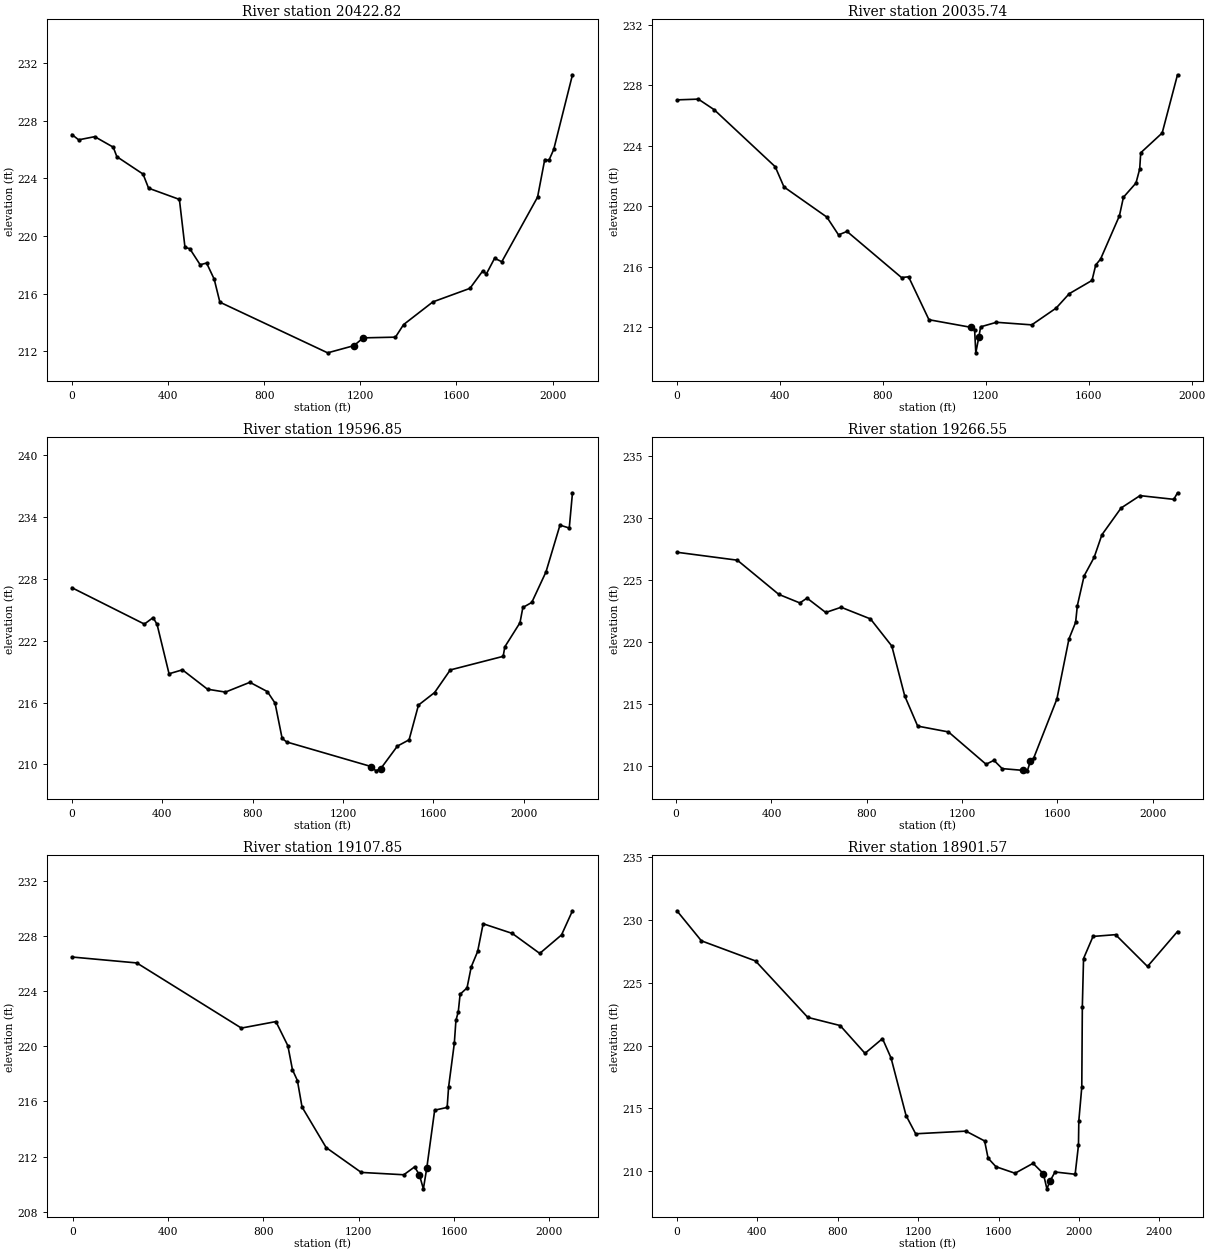
Type RM Length L Ch R = 1 ,20422.82,356.27,387.08,353.88
XS GIS Cut Line= 5
     1861778.438      396206.865     1861655.706      396018.931
     1861310.779      395454.009     1861121.079      395009.704
     1860838.769      394354.375
#Sta/Elev= 30
       0  227.05   28.16  226.68   95.06   226.9  172.13  226.17  187.11  225.51
  296.13   224.3  319.16  223.32  447.38  222.54  470.66   219.2  490.44  219.12
  533.79     218  560.54  218.12  592.15     217   615.8   215.4 1064.26  211.88
  1173.7  212.38 1212.26  212.92 1346.45  212.97 1380.06  213.84  1502.2  215.42
 1656.32  216.36 1710.46  217.59 1724.31  217.35 1758.96  218.45  1788.9  218.21
 1937.76   222.7  1967.6  225.31 1984.78  225.25 2004.94  226.01 2083.02   231.2
#Mann= 0 , 0 , 0
Bank Sta=1173.7,1212.26
Exp/Cntr=.3,.1

Type RM Length L Ch R = 1 ,20035.74,355.79,438.9,428.82
XS GIS Cut Line= 5
     1861892.968      396158.615     1861653.813       395368.99
     1861608.386      395245.098     1861460.208      394909.151
     1861153.271      394369.716
#Sta/Elev= 30
       0  227.02   83.18  227.07  144.85  226.37  381.86   222.6  416.01  221.26
  582.38  219.27  627.95  218.09   660.8  218.32  872.56  215.27  900.04  215.32
  979.23  212.48 1141.61  211.98 1156.59  211.82 1161.23  210.29 1172.73  211.31
 1180.01  212.01 1241.42  212.31  1378.6  212.14 1473.38  213.25  1524.1   214.2
 1612.72  215.08 1627.16   216.1  1645.9  216.49  1719.1  219.35 1734.76  220.58
 1783.51  221.52 1797.96  222.45 1801.91  223.52 1885.28  224.83 1944.82  228.68
#Mann= 0 , 0 , 0
Bank Sta=1141.61,1172.73
Exp/Cntr=.3,.1

Type RM Length L Ch R = 1 ,19596.85,294.02,330.3,326.64
XS GIS Cut Line= 4
     1861949.129      396084.065      1861819.71      394845.354
     1861794.157      394686.927     1861730.871      393879.367
#Sta/Elev= 30
       0  227.15  320.93  223.62  359.68  224.25  377.19  223.58  430.11   218.8
   489.3  219.18   600.4   217.3   679.8  217.02  787.93  217.97  865.25  217.07
  899.39  215.95  930.64  212.53  950.94  212.18 1325.87  209.79 1345.77  209.38
 1367.45   209.6  1440.9  211.78 1492.68  212.39 1534.24  215.76 1605.74  216.98
 1674.96  219.17 1909.17  220.49 1916.44  221.41 1983.56  223.75 1996.34  225.23
 2035.77  225.72 2098.64  228.68 2160.59  233.22 2201.71  232.94 2215.96  236.36
#Mann= 0 , 0 , 0
Bank Sta=1325.87,1367.45
Exp/Cntr=.3,.1

Type RM Length L Ch R = 1 ,19266.55,157.94,158.7,157.18
XS GIS Cut Line= 2
       1862073.6      396124.951      1862117.26      394025.313
#Sta/Elev= 30
     3.4  227.24  256.89   226.6  430.85  223.84  519.17  223.15  549.31  223.54
  627.81  222.38   692.3   222.8  815.48  221.86  905.02  219.67  959.04  215.65
 1013.47  213.21 1142.64  212.74 1300.43  210.13 1333.32  210.45 1367.96  209.78
 1453.65  209.64 1473.55   209.6 1485.99  210.36 1500.42  210.64  1597.4  215.39
 1648.18  220.25 1676.02  221.58 1683.41  222.94 1711.68  225.33 1753.85  226.83
 1786.33  228.65 1866.77  230.81 1946.25  231.81 2088.03  231.51 2103.49  232.04
#Mann= 3 , 0 , 0
     3.4               0 1453.65               0 1485.99               0
Bank Sta=1453.65,1485.99
Exp/Cntr=.3,.1

Type RM Length L Ch R = 1 ,19107.85,307.94,206.28,154.61
XS GIS Cut Line= 2
     1862230.822      396113.304     1862274.482      394013.667
#Sta/Elev= 30
    -3.4  226.47  268.92  226.04  707.61  221.32  852.52  221.79  902.66  220.04
  921.98   218.3  942.62  217.52  962.12   215.6  1063.3  212.66 1210.56  210.86
 1389.06  210.69 1434.34  211.26 1454.06   210.7 1471.22  209.67 1485.56  211.19
 1518.55  215.37 1570.92  215.57    1577  217.05 1600.97  220.21  1607.7  221.87
 1617.68  222.51 1625.26  223.77 1654.26  224.23 1672.03  225.76 1698.85  226.87
 1721.87  228.88 1843.98  228.18 1959.39  226.73 2050.71  228.07 2096.69  229.82
#Mann= 3 , 0 , 0
    -3.4               0 1454.06               0 1485.56               0
Bank Sta=1454.06,1485.56
Exp/Cntr=.3,.1

Type RM Length L Ch R = 1 ,18901.57,1912.74,2304.93,1743.26
XS GIS Cut Line= 3
     1863567.239      396075.413     1862302.919      394401.922
     1862299.878      394009.441
#Sta/Elev= 30
       0  230.72  121.76  228.33  390.92  226.73  650.99  222.24  811.91  221.59
  935.56  219.38 1022.54  220.55 1065.14  219.01 1139.77  214.43 1187.49  212.98
 1437.77  213.19 1530.48  212.41 1547.78  211.04 1586.95  210.36 1681.89  209.84
 1771.46  210.63  1822.6  209.81 1840.31   208.6 1854.97  209.19 1880.54  209.94
 1980.78  209.76 1997.33  212.07 1999.05  214.01  2013.8  216.69 2016.55  223.09
 2022.57  226.92 2069.72  228.68 2181.81  228.82  2340.7  226.29 2489.89  229.07
#Mann= 0 , 0 , 0
Bank Sta=1822.6,1854.97
Exp/Cntr=.3,.1

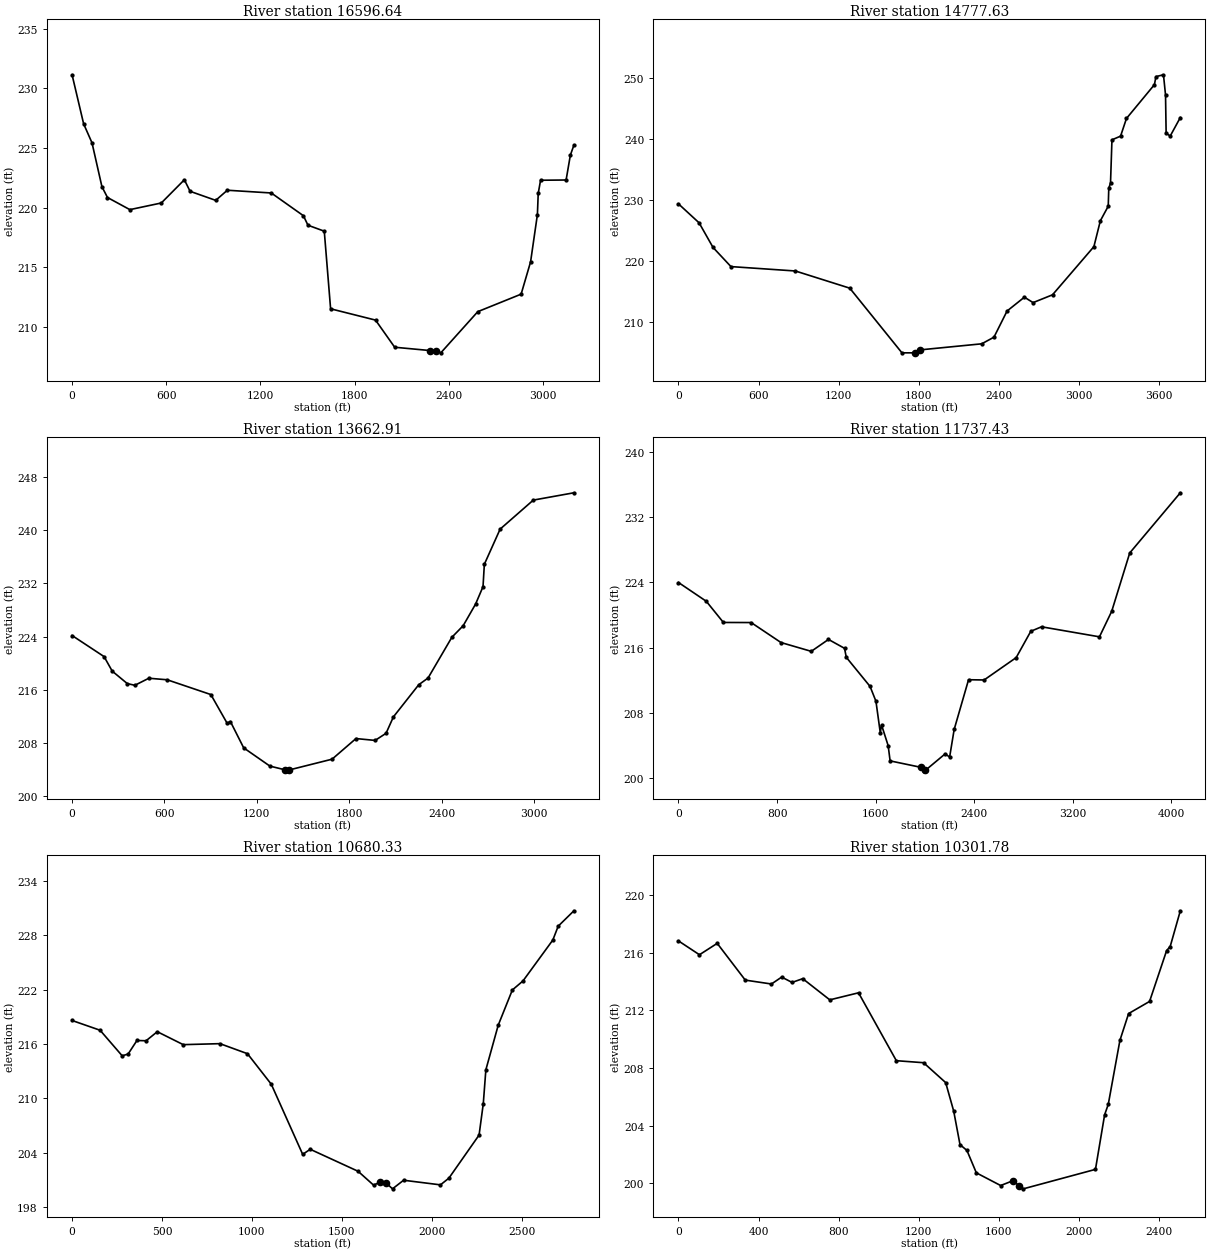
Type RM Length L Ch R = 1 ,16596.64,1630.52,1819.01,1392.81
XS GIS Cut Line= 4
     1865129.739      394087.566      1863677.79      393192.302
     1862742.657      392933.168     1862239.114      392802.844
#Sta/Elev= 30
       0  231.15    73.6  227.03  127.01  225.43  190.12  221.75  225.51  220.84
  368.11  219.82  568.48  220.38  715.18  222.33  751.69  221.36  914.84   220.6
  988.88  221.45 1268.78  221.22  1473.3  219.31 1502.47  218.51  1606.3  218.01
  1646.6  211.49 1932.84  210.54 2054.73  208.26 2282.14  207.98  2317.3  207.98
 2348.52  207.79 2584.08  211.25 2860.02  212.72 2920.22  215.43 2963.75  219.41
 2968.89  221.18 2983.88  222.29 3146.51  222.31 3173.65   224.4 3196.28  225.24
#Mann= 0 , 0 , 0
Bank Sta=2282.14,2317.3
Exp/Cntr=.3,.1

Type RM Length L Ch R = 1 ,14777.63,1035.16,1114.73,1059.53
XS GIS Cut Line= 2
     1865485.642      392950.413     1862273.836      390997.288
#Sta/Elev= 30
       0  229.35  154.45  226.24  258.94   222.2  392.97  219.06  875.35  218.34
 1283.05  215.52 1673.87  204.91 1775.12  204.91 1811.86   205.4 2271.32  206.39
 2363.21  207.48 2461.21  211.77 2590.99  214.04 2656.22  213.15 2801.68  214.43
 3111.57  222.33 3160.08  226.58  3219.1  228.97 3223.16   231.9 3236.14  232.78
 3246.96  239.86 3311.42  240.46 3355.52  243.36 3565.09  248.91 3576.39  250.23
 3632.82  250.53  3648.2  247.22 3652.78  240.93 3683.57  240.49 3759.04  243.52
#Mann= 0 , 0 , 0
Bank Sta=1775.12,1811.86
Exp/Cntr=.3,.1

Type RM Length L Ch R = 1 ,13662.91,1855.1,1925.48,1950.49
XS GIS Cut Line= 2
     1865629.703      391963.553     1862970.807      390079.535
#Sta/Elev= 30
       0  224.17  207.89     221  260.62  218.82  358.42  216.95  407.54  216.69
  498.51  217.75   617.4  217.52  901.12   215.3 1006.83  210.99 1028.07  211.25
 1114.43  207.29 1284.75  204.55  1381.7     204 1397.03  203.84 1411.02  203.98
 1688.26  205.59 1843.53  208.69 1967.75  208.41 2038.83  209.48 2086.66  211.95
 2251.29  216.78 2311.42  217.78 2466.08   223.9 2539.57  225.64 2620.35   228.9
 2668.48  231.51  2677.1  234.87 2779.53  240.15 2995.02  244.51 3258.72  245.61
#Mann= 0 , 0 , 0
Bank Sta=1381.7,1411.02
Exp/Cntr=.3,.1

Type RM Length L Ch R = 1 ,11737.43,982.14,1057.1,1042.11
XS GIS Cut Line= 2
     1866641.119      391500.222     1864732.751      387902.928
#Sta/Elev= 30
       0  223.99  225.54  221.69  364.61  219.09  589.59  219.08  831.86  216.63
 1077.55  215.55 1217.15  217.01 1347.43  215.92  1361.7  214.82 1554.58  211.25
 1602.37  209.43 1637.52  205.57 1647.72  206.53  1701.6  203.98  1717.3  202.12
 1970.92  201.32 1995.01   200.9  2003.5  200.96 2163.88  202.98 2200.21  202.59
 2237.02  205.97 2353.78  212.07 2480.11  212.04 2740.08  214.78 2858.97  218.01
 2946.16  218.56 3415.93  217.33 3515.42  220.46 3661.61  227.61 4072.15  234.99
#Mann= 0 , 0 , 0
Bank Sta=1970.92,2003.5
Exp/Cntr=.3,.1

Type RM Length L Ch R = 1 ,10680.33,373.7,378.55,388.57
XS GIS Cut Line= 2
     1867070.346      391148.692     1866381.334      388444.975
#Sta/Elev= 30
       0  218.59  155.84  217.51  278.49  214.69  311.45  214.88  360.69  216.38
  411.47  216.35  473.83  217.35  618.03  215.92  822.23  216.03  975.17  214.92
 1107.48  211.55 1282.14   203.8 1324.09  204.36 1590.16  201.93 1676.23   200.4
 1713.14  200.73 1743.83  200.68 1781.52  199.99  1843.2  200.94 2048.18  200.43
 2095.04  201.17 2262.84  205.93 2286.29  209.41 2300.52  213.14 2369.27  218.07
 2447.78  221.96 2506.99  222.96 2672.93  227.48 2702.73  229.01 2790.13  230.71
#Mann= 0 , 0 , 0
Bank Sta=1713.14,1743.83
Exp/Cntr=.3,.1

Type RM Length L Ch R = 1 ,10301.78,288.36,311.42,318.02
XS GIS Cut Line= 2
     1867349.439      391131.248     1866861.026      388671.738
#Sta/Elev= 30
       0  216.81  104.85  215.85  193.55  216.64  333.78  214.09  464.49  213.82
  515.67   214.3  567.42  213.93  620.87  214.19   756.1  212.72  899.68  213.21
 1088.61   208.5  1224.6  208.36  1335.1  206.98 1375.24     205 1406.64  202.68
 1441.44  202.27 1488.28  200.72 1609.75  199.84 1672.53  200.18 1702.62  199.81
 1722.88  199.61 2083.52  200.96 2129.32  204.75 2147.53  205.47  2205.7  209.91
 2249.17  211.77 2353.83  212.61 2439.12  216.14 2456.89  216.42 2507.54   218.9
#Mann= 0 , 0 , 0
Bank Sta=1672.53,1702.62
Exp/Cntr=.3,.1

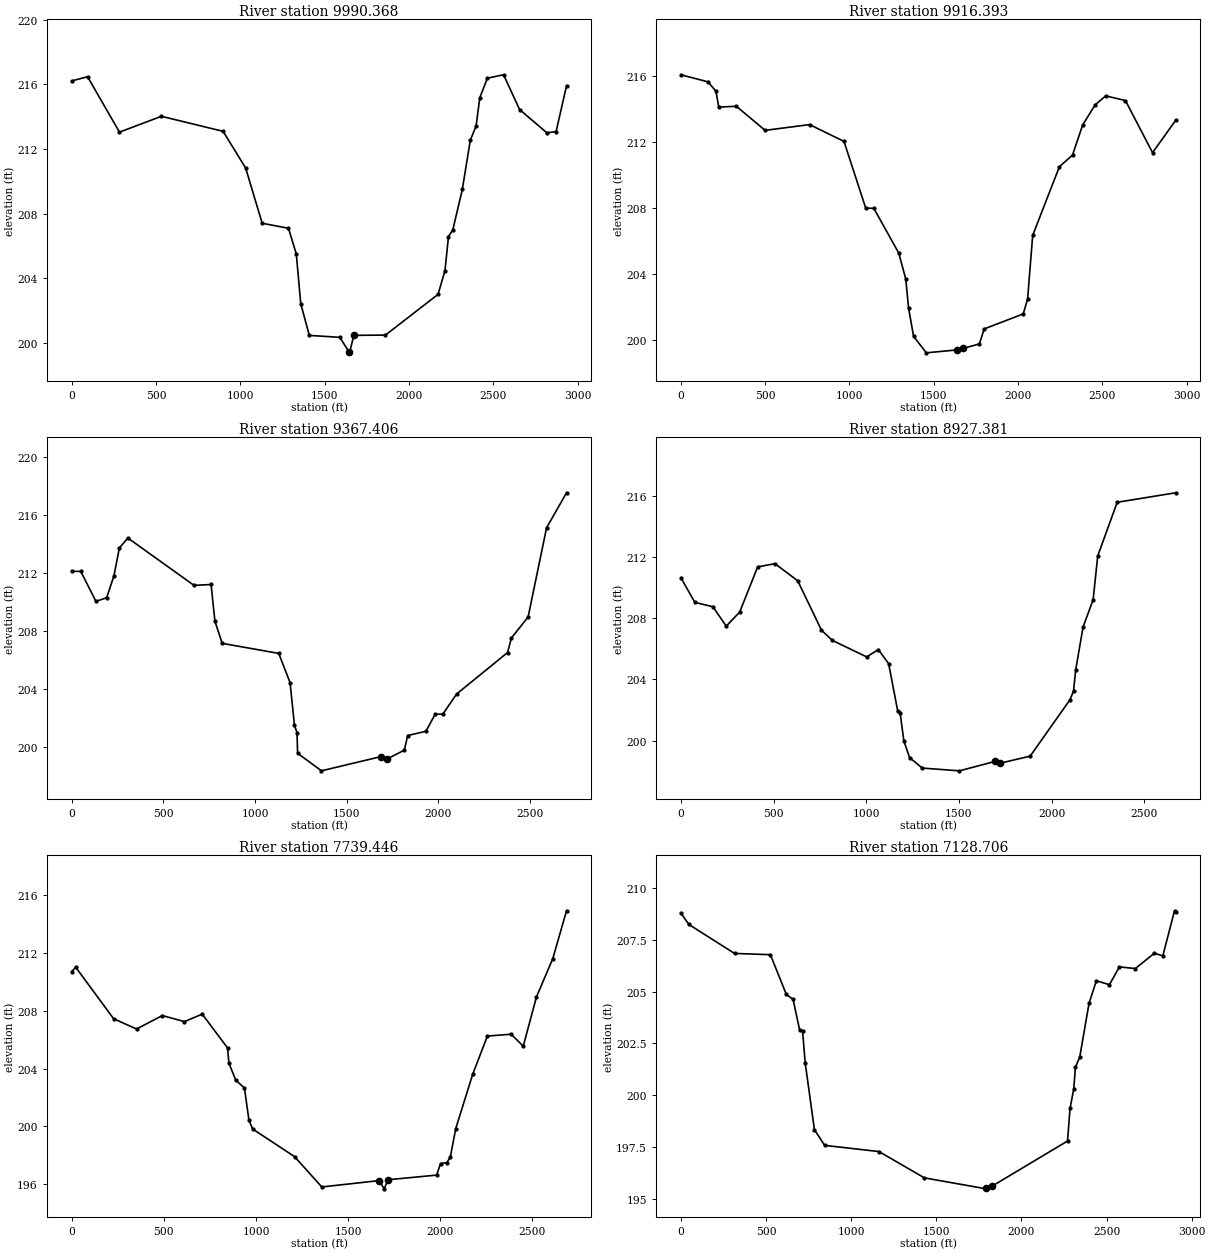
Type RM Length L Ch R = 1 ,9990.368,72.83,73.98,74.66
XS GIS Cut Line= 4
     1867487.172      391108.329     1867351.373      389770.112
     1867245.787      388938.395     1867144.732       388193.79
#Sta/Elev= 30
    -.75  216.21   93.06  216.47  282.59  213.04  531.33  214.02   897.1  213.09
 1030.92  210.82 1128.88   207.4 1284.83  207.09 1331.36   205.5 1357.63  202.43
 1408.43  200.46 1589.27  200.34  1642.8  199.46 1647.31  199.38 1672.15  200.46
 1860.13  200.48 2172.12     203 2213.08  204.46 2233.94  206.57  2259.6  206.99
 2316.05  209.49 2363.16  212.53 2397.81  213.42 2419.74  215.17 2464.72  216.38
 2560.77  216.59  2655.6  214.44  2817.3     213 2872.34  213.07 2934.16  215.91
#Mann= 3 , 0 , 0
    -.75               0  1642.8               0 1672.15               0
Bank Sta=1642.8,1672.15
Exp/Cntr=.3,.1

Type RM Length L Ch R = 1 ,9916.393,407.11,548.99,410.17
XS GIS Cut Line= 4
     1867560.278      391110.545     1867424.479      389772.328
     1867318.893      388940.611     1867217.839      388196.005
#Sta/Elev= 30
     .75  216.08  161.68  215.65  208.62  215.08  225.05  214.12   329.4  214.17
   500.3  212.71   763.9  213.06  967.95  212.04 1096.76     208 1145.01  207.98
 1292.79  205.27 1334.78  203.68 1350.86  201.94 1380.72  200.22  1456.5  199.22
 1639.56   199.4 1675.38  199.49 1771.15  199.76 1799.39  200.67 2031.15  201.58
 2057.04  202.49 2087.21  206.34 2245.85  210.51 2323.49  211.21 2383.79  213.04
 2458.07  214.26 2520.31   214.8 2637.24  214.52 2798.19  211.36 2935.66  213.32
#Mann= 3 , 0 , 0
     .75               0 1639.56               0 1675.38               0
Bank Sta=1639.56,1675.38
Exp/Cntr=.3,.1

Type RM Length L Ch R = 1 ,9367.406,301.74,440.02,328.22
XS GIS Cut Line= 4
     1867921.773      391073.549     1867895.045       390728.12
     1867811.688      389744.503     1867707.028      388383.923
#Sta/Elev= 30
       0  212.11   49.37   212.1  132.12  210.04  190.56  210.29  230.53  211.81
  259.82  213.71  305.93   214.4  666.95  211.14  759.99   211.2  780.79  208.68
  820.54  207.15 1128.96  206.46 1190.79  204.44 1214.55  201.52  1228.5  201.01
 1231.66  199.59 1361.87  198.38 1686.38  199.36 1718.76  199.19 1813.59   199.8
 1832.05  200.81 1931.51   201.1 1982.01  202.28 2023.67  202.28 2099.11  203.67
 2376.83  206.52 2397.53  207.52 2488.67  208.96 2589.33   215.1  2698.2  217.51
#Mann= 0 , 0 , 0
Bank Sta=1686.38,1718.76
Exp/Cntr=.3,.1

Type RM Length L Ch R = 1 ,8927.381,747.89,1187.94,722.66
XS GIS Cut Line= 4
     1868103.013      391115.931     1868110.921      391005.813
     1868103.599      389204.839     1868103.599      388446.054
#Sta/Elev= 30
       0  210.63   75.23  209.02  172.23  208.74  244.72  207.47   317.1  208.39
  414.18  211.34  507.45  211.55  630.45  210.43  758.32  207.21  816.96  206.54
 1002.54  205.46  1065.2  205.94 1121.01  205.02 1169.89  201.93 1182.72  201.82
 1202.97  199.98 1234.08  198.88 1302.56   198.2 1503.19  198.02 1692.89  198.63
 1719.59  198.51 1884.69  198.98 2099.92  202.67 2118.54  203.23 2130.19   204.6
 2170.09  207.41 2224.61   209.2 2249.17  212.05 2354.33  215.56 2670.17  216.18
#Mann= 0 , 0 , 0
Bank Sta=1692.89,1719.59
Exp/Cntr=.3,.1

Type RM Length L Ch R = 1 ,7739.446,391.1,610.74,475.85
XS GIS Cut Line= 4
     1868962.178      390966.191     1868931.338      390977.058
     1868799.714      388925.011     1868508.399      388404.992
#Sta/Elev= 30
       0  210.71   21.84  211.01  227.37  207.45  351.78  206.74  491.85  207.67
  611.66  207.25   708.1  207.77  845.61  205.43  852.92  204.38  889.68  203.21
  937.33  202.65  961.82  200.42  982.04  199.82 1208.97  197.91 1357.04  195.81
 1668.66  196.25 1695.52  195.68 1716.42  196.31 1980.25  196.63 2001.59  197.43
 2035.16  197.49 2054.34  197.87 2083.86  199.85 2176.44  203.63  2255.7  206.25
 2384.31  206.38 2450.16  205.55 2521.93  208.96 2610.23   211.6 2685.02  214.92
#Mann= 0 , 0 , 0
Bank Sta=1668.66,1716.42
Exp/Cntr=.3,.1

Type RM Length L Ch R = 1 ,7128.706,651.94,726.17,680.59
XS GIS Cut Line= 4
     1869197.633      390947.724     1869208.195      389408.635
     1869291.076      388771.032     1868799.974      388238.378
#Sta/Elev= 30
       0   208.8   46.59  208.25  314.92  206.85  525.51  206.79  619.22  204.87
  658.84  204.63  697.42  203.15  714.54  203.11  730.04  201.56  784.14  198.34
  844.26  197.58 1163.62  197.28 1430.12  196.01 1793.07  195.48 1793.37  195.53
 1829.85  195.62 2271.08  197.79 2285.88  199.37 2307.32  200.29 2317.48  201.36
 2342.59  201.84 2397.36  204.44 2440.55  205.53 2517.21  205.34 2575.62   206.2
 2669.31  206.12 2781.36  206.86 2830.68  206.73 2899.51  208.91 2906.59  208.85
#Mann= 0 , 0 , 0
Bank Sta=1793.37,1829.85
Exp/Cntr=.3,.1

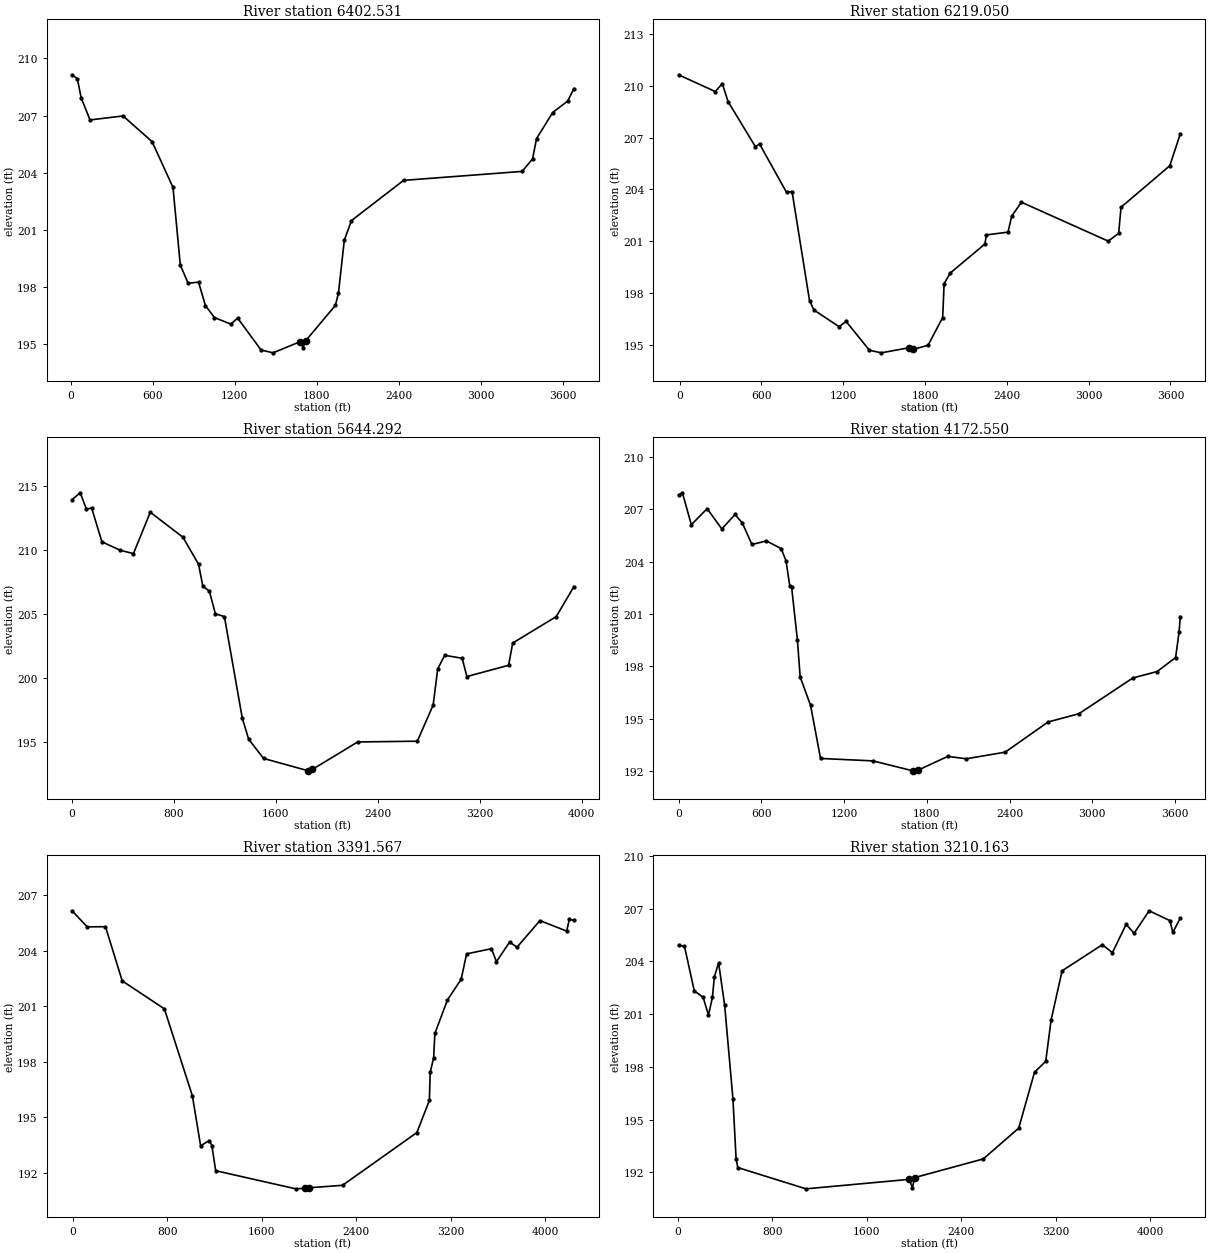
Type RM Length L Ch R = 1 ,6402.531,176.09,183.49,177.69
XS GIS Cut Line= 4
     1869503.772      390773.187     1869655.967      389837.186
     1870340.846      387866.257     1870340.846      387227.037
#Sta/Elev= 30
    8.17  209.14   47.13  208.93   74.39  207.94  139.63  206.77  381.45  206.98
  594.19  205.63  747.06  203.23  800.57  199.16  858.01   198.2  934.27  198.26
  984.62  197.03 1050.82   196.4 1169.65  196.06 1220.79  196.37 1391.95   194.7
 1479.71  194.55 1679.81  195.14 1699.71  194.83 1719.61  195.19 1936.07  197.04
 1958.53  197.68 2001.42  200.46 2053.89  201.49 2435.65   203.6  3303.5  204.07
 3380.03  204.73 3408.87  205.79 3527.19  207.16  3636.8  207.76 3682.22  208.41
#Mann= 3 , 0 , 0
    8.17               0 1679.81               0 1719.61               0
Bank Sta=1679.81,1719.61
Exp/Cntr=.3,.1

Type RM Length L Ch R = 1 ,6219.050,693.99,574.76,527.77
XS GIS Cut Line= 4
     1869674.954      390816.893     1869827.149      389880.892
     1870449.191      388090.792     1870447.539      387253.408
#Sta/Elev= 30
   -8.17  210.63  261.39  209.66  312.95  210.12  355.04  209.08  555.12  206.48
  585.98  206.63   784.1  203.83  824.43  203.88  952.72  197.57  984.62  197.03
 1169.65  196.06 1220.79  196.37 1391.95   194.7 1479.71  194.55 1684.99  194.85
 1714.43  194.75  1822.1  194.99 1929.29  196.59 1940.05  198.55 1984.28  199.16
 2238.75  200.84 2250.56  201.37 2408.49  201.53 2435.93  202.46 2507.02  203.26
 3143.92  201.01 3220.17  201.46 3237.84  202.97 3595.35  205.37 3672.61  207.22
#Mann= 3 , 0 , 0
   -8.17               0 1684.99               0 1714.43               0
Bank Sta=1684.99,1714.43
Exp/Cntr=.3,.1

Type RM Length L Ch R = 1 ,5644.292,1594.63,1471.74,1313.86
XS GIS Cut Line= 3
     1870845.885      391123.156     1870457.718      387853.925
     1870459.686      387206.536
#Sta/Elev= 30
       0  213.95    63.9  214.48  113.14  213.19  153.46   213.3  234.37  210.64
  378.54  209.98   481.9  209.72  613.91  212.96  870.62     211  992.87  208.89
 1026.97  207.16 1077.51  206.79 1125.28  205.01 1196.13  204.79  1336.5  196.83
 1386.64  195.19  1503.6  193.69 1855.54  192.72 1886.57  192.83 2242.09  194.98
 2710.75  195.04 2834.87  197.87  2870.7   200.7  2925.6  201.76 3062.42  201.53
 3099.96   200.1 3426.97  200.98  3459.5  202.72 3801.24  204.79 3939.59  207.13
#Mann= 0 , 0 , 0
Bank Sta=1855.54,1886.57
Exp/Cntr=.3,.1

Type RM Length L Ch R = 1 ,4172.550,794.37,780.98,660.94
XS GIS Cut Line= 2
     1872903.177      390333.226      1870915.33      387286.351
#Sta/Elev= 30
       0  207.83   28.18  207.95    92.7  206.12  207.37  207.04  313.77  205.88
  410.01  206.71  462.41  206.22  532.05  204.99  637.74  205.19  744.28  204.75
  779.38  204.05  806.14  202.63  819.77  202.55  862.02   199.5   881.8   197.4
  957.31  195.77 1029.45  192.73 1409.44  192.59  1699.5  192.02  1739.3  192.07
 1952.46  192.85 2085.69  192.71 2368.22  193.09 2679.53  194.82 2902.36  195.29
 3293.74  197.34 3470.04  197.71 3603.69  198.51 3628.85  199.96 3637.99  200.86
#Mann= 0 , 0 , 0
Bank Sta=1699.5,1739.3
Exp/Cntr=.3,.1

Type RM Length L Ch R = 1 ,3391.567,210.67,181.41,197.95
XS GIS Cut Line= 4
     1873919.302      390245.992     1872767.971      388824.979
     1872521.562      388547.131     1871219.649      386964.742
#Sta/Elev= 30
   -6.22  206.15  122.06  205.28  276.82  205.29  418.54  202.36  775.52  200.85
 1012.53  196.15 1082.22  193.45 1156.13  193.73 1178.11  193.45 1209.96   192.1
  1888.6  191.12 1963.93  191.15 2003.73  191.18 2284.12  191.31 2913.41  194.16
 3019.73   195.9  3026.4  197.41  3055.9  198.21 3066.17  199.52 3172.88  201.33
 3288.79  202.45 3334.81  203.82 3544.89   204.1 3587.76   203.4 3699.19  204.46
 3761.77  204.18  3955.7  205.62 4182.61  205.05 4204.45  205.69 4243.17  205.63
#Mann= 3 , 0 , 0
   -6.22               0 1963.93               0 2003.73               0
Bank Sta=1963.93,2003.73
Exp/Cntr=.3,.1

Type RM Length L Ch R = 1 ,3210.163,699.89,915.78,1002.18
XS GIS Cut Line= 4
     1874057.048      390136.942     1872905.718       388715.93
     1872659.309      388438.082     1871357.395      386855.692
#Sta/Elev= 30
    6.22  204.91   56.45  204.86  139.39  202.33  214.26  201.96  259.85  200.95
  293.05  201.95  309.47  203.11  345.44  203.93  396.93   201.5  466.94  196.18
  493.86  192.77  508.05  192.28 1085.55  191.07 1961.44  191.61 1986.32  191.12
 2006.22  191.71 2586.93  192.77  2886.9  194.52 3020.85   197.7 3115.73  198.32
 3161.31  200.67 3254.52  203.47 3595.21  204.95 3680.59   204.5  3796.7  206.11
 3864.19   205.6 3991.55  206.88 4167.52  206.32 4191.85  205.65 4255.61  206.46
#Mann= 3 , 0 , 0
    6.22               0 1961.44               0 2006.22               0
Bank Sta=1961.44,2006.22
Exp/Cntr=.3,.1