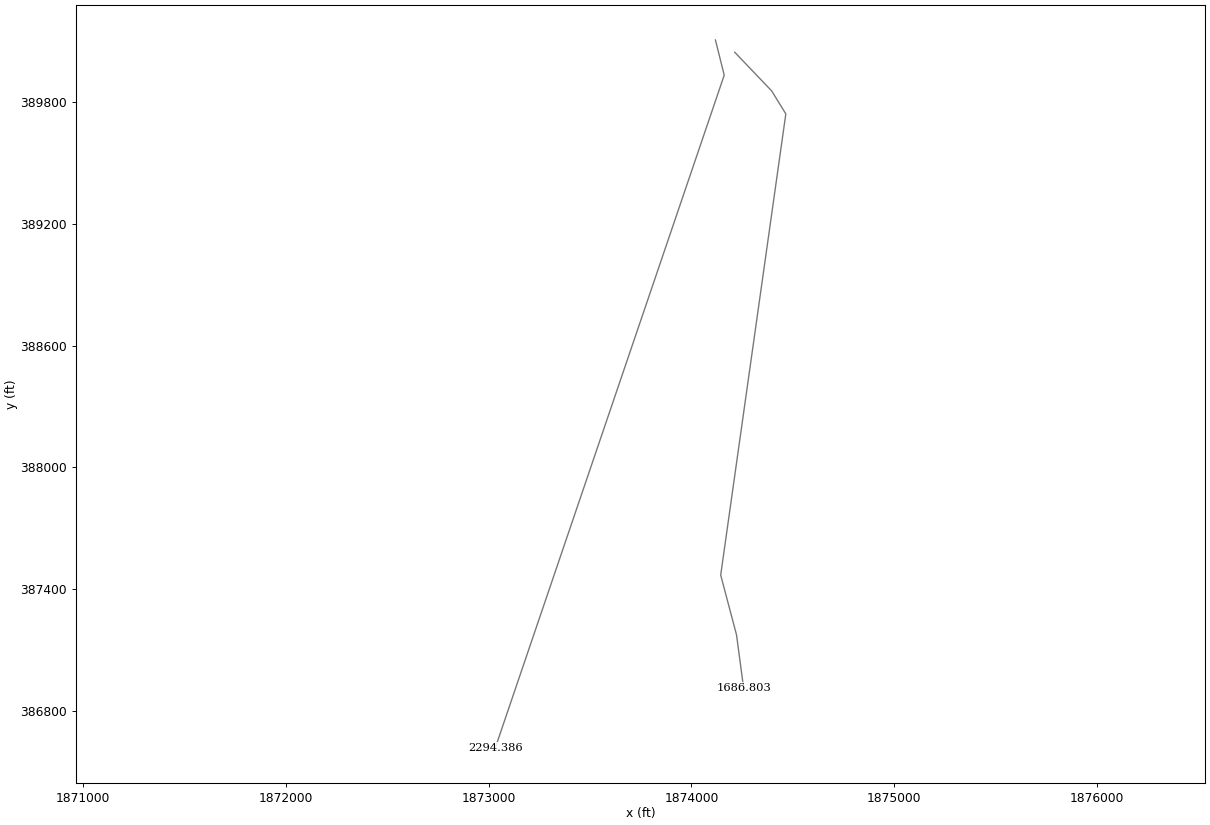
HEC-RAS study jordan.prj: Jordan Creek

--- jordan.g01 (geometry) --- (continued)

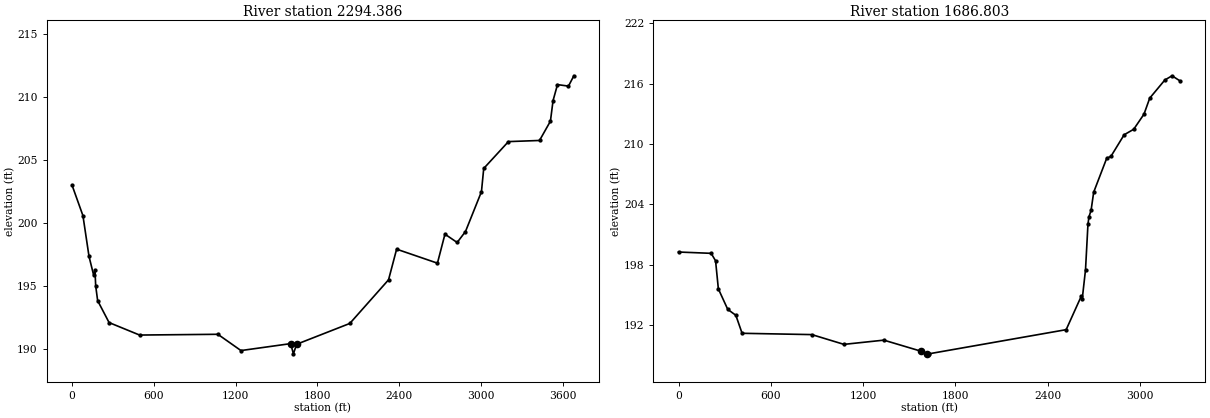
Type RM Length L Ch R = 1 ,2294.386,519.55,607.58,673.53
XS GIS Cut Line= 3
     1874118.455      390107.531     1874161.857       389933.92
     1873033.385      386617.948
#Sta/Elev= 30
       0  203.01   79.69   200.6  124.41  197.36  158.36  195.88  168.14  196.26
   173.3  195.03  187.61  193.86  271.49  192.12  495.41  191.13  1069.7  191.19
 1239.14   189.9 1603.98  190.45 1623.88  189.64 1647.76   190.4 2037.81  192.05
 2321.93  195.51 2381.29  197.94  2680.7  196.83 2735.87  199.13 2825.41  198.47
 2886.58  199.34 3003.71   202.5 3020.32  204.34 3201.59  206.47 3429.79  206.56
 3509.77  208.09 3529.02  209.72 3561.52  210.99 3642.11  210.87 3681.68  211.69
#Mann= 0 , 0 , 0
Bank Sta=1603.98,1647.76
Exp/Cntr=.3,.1

Type RM Length L Ch R = 1 ,1686.803,448.25,1686.8,798.95
XS GIS Cut Line= 6
     1874213.941      390046.767     1874396.232      389855.795
     1874465.677      389742.948     1874144.496      387468.642
     1874222.621      387173.503     1874257.344      386913.087
#Sta/Elev= 30
       0  199.27  211.97  199.14  240.68   198.4  258.84  195.61  320.06  193.57
  372.42  192.99  413.07   191.2  866.47  191.07 1075.06   190.1 1334.51  190.52
 1574.13  189.43 1612.44  189.17 1625.96  189.16  2519.4  191.56 2618.38  194.91
 2623.53  194.56 2645.17  197.51 2661.04  202.02 2667.44  202.76 2681.29   203.4
 2698.26  205.21 2783.14  208.59 2810.07  208.76 2896.15  210.91 2958.46  211.46
 3025.31  212.96 3062.51  214.55 3160.73  216.35 3207.53  216.77 3261.41  216.24
#Mann= 0 , 0 , 0
Bank Sta=1574.13,1612.44
Exp/Cntr=.3,.1

Chan Stop Cuts=-1
Chan Mod River=Jordan_Creek
Chan Mod Reach=01
Chan Mod RS=72842.67,0,619.43,964.06,978.73,,,297.13,,,,,,297.13,,,,,,297.13,,,
Chan Mod RS=71878.61,0,983.71,1118.55,1113.35,,,297.12,,,,,,297.12,,,,,,297.12,,,
Chan Mod RS=70760.06,0,858.19,924.35,734.94,,,295.8,,,,,,295.8,,,,,,295.8,,,
Chan Mod RS=69835.71,0,713.19,679.23,662.76,,,292.5,,,,,,292.5,,,,,,292.5,,,
Chan Mod RS=69156.48,0,1252.03,1193.66,991.24,,,288.35,,,,,,288.35,,,,,,288.35,,,
Chan Mod RS=67962.83,0,1134.32,1158.5,1125.45,,,289.85,,,,,,289.85,,,,,,289.85,,,
Chan Mod RS=66804.32,0,532.94,627,733.63,,,284.93,,,,,,284.93,,,,,,284.93,,,
Chan Mod RS=66177.32,0,567.08,614.58,660.73,,,282.29,,,,,,282.29,,,,,,282.29,,,
Chan Mod RS=65562.75,0,438.46,470.78,478.01,,,280.89,,,,,,280.89,,,,,,280.89,,,
Chan Mod RS=65091.96,0,931.33,979.16,955.29,,,281.17,,,,,,281.17,,,,,,281.17,,,
Chan Mod RS=64112.81,0,255.48,235.83,222.18,,,277.19,,,,,,277.19,,,,,,277.19,,,
Chan Mod RS=63876.98,0,121.73,111.21,116.47,,,276.98,,,,,,276.98,,,,,,276.98,,,
Chan Mod RS=63765.77,0,694.36,706.65,677.38,,,276.01,,,,,,276.01,,,,,,276.01,,,
Chan Mod RS=63059.12,0,793.72,776.78,673.81,,,275.24,,,,,,275.24,,,,,,275.24,,,
Chan Mod RS=62282.35,0,782.43,850.47,741.08,,,274.71,,,,,,274.71,,,,,,274.71,,,
Chan Mod RS=61431.88,0,432.17,436.13,424.8,,,270.86,,,,,,270.86,,,,,,270.86,,,
Chan Mod RS=60995.75,0,720.64,750.49,783.07,,,269.71,,,,,,269.71,,,,,,269.71,,,
Chan Mod RS=60245.25,0,408.21,473.27,450.47,,,268.81,,,,,,268.81,,,,,,268.81,,,
Chan Mod RS=59771.98,0,850.63,802.38,739.07,,,268.16,,,,,,268.16,,,,,,268.16,,,
Chan Mod RS=58969.60,0,839.79,819.56,748.85,,,266.89,,,,,,266.89,,,,,,266.89,,,
Chan Mod RS=58150.04,0,1016.17,1036.44,1002.52,,,265.52,,,,,,265.52,,,,,,265.52,,,
Chan Mod RS=57113.60,0,1520.55,1672.9,1644.62,,,264.64,,,,,,264.64,,,,,,264.64,,,
Chan Mod RS=55440.71,0,1346.35,1435.92,1360,,,262.35,,,,,,262.35,,,,,,262.35,,,
Chan Mod RS=54004.79,0,980.06,1008.26,979.92,,,261.98,,,,,,261.98,,,,,,261.98,,,
Chan Mod RS=52996.53,0,762.99,886.3,835.66,,,259.94,,,,,,259.94,,,,,,259.94,,,
Chan Mod RS=52110.23,0,794.84,851.47,829.46,,,258.18,,,,,,258.18,,,,,,258.18,,,
Chan Mod RS=51258.76,0,852.49,883.11,516.38,,,258.28,,,,,,258.28,,,,,,258.28,,,
Chan Mod RS=50375.65,0,640.09,624.21,522.64,921.65,20,257.86,2,2,,,,257.86,,,,,,257.86,,,
Chan Mod RS=49751.44,0,543.46,507.47,439.45,862.09,20,256.91,2,2,,,,256.91,,,,,,256.91,,,
Chan Mod RS=49243.97,0,438.4,507,484.56,1169.75,20,256.14,2,2,,,,256.14,,,,,,256.14,,,
Chan Mod RS=48736.97,0,272.65,635.45,608.5,1027.75,20,255.36,2,2,,,,255.36,,,,,,255.36,,,
Chan Mod RS=48101.51,0,336.98,411.89,180.76,915.32,20,254.39,2,2,,,,254.39,,,,,,254.39,,,
Chan Mod RS=47689.63,0,216.42,213.52,361.74,835.03,20,253.77,2,2,,,,253.77,,,,,,253.77,,,
Chan Mod RS=47476.11,0,441.63,428.2,381.81,935.28,20,253.44,2,2,,,,253.44,,,,,,253.44,,,
Chan Mod RS=47047.91,0,1122.74,1134.31,1079.26,,,,,,,,,,,,,,,,,,
Chan Mod RS=45913.61,0,705.66,681.64,637.91,,,,,,,,,,,,,,,,,,
Chan Mod RS=45231.97,0,638.19,768.47,859.39,,,,,,,,,,,,,,,,,,
Chan Mod RS=44463.49,0,1469.72,1454.31,1352.06,,,,,,,,,,,,,,,,,,
Chan Mod RS=43009.18,0,395.96,396.3,397.06,,,,,,,,,,,,,,,,,,
Chan Mod RS=42612.88,0,339.86,337.46,318.32,,,,,,,,,,,,,,,,,,
Chan Mod RS=42275.41,0,386.27,413.73,418.36,,,,,,,,,,,,,,,,,,
Chan Mod RS=41861.69,0,240.36,242.24,261.37,,,,,,,,,,,,,,,,,,
Chan Mod RS=41619.45,0,105.22,104.89,106.17,,,,,,,,,,,,,,,,,,
Chan Mod RS=41514.55,0,299.99,295.92,273.79,,,,,,,,,,,,,,,,,,
Chan Mod RS=41218.63,0,758.34,755.13,734.23,,,,,,,,,,,,,,,,,,
Chan Mod RS=40463.49,0,1055.21,1139.6,1136.71,,,,,,,,,,,,,,,,,,
Chan Mod RS=39323.89,0,1234.54,1296.59,1178.82,,,,,,,,,,,,,,,,,,
Chan Mod RS=38027.30,0,656.94,718.28,502.28,,,,,,,,,,,,,,,,,,
Chan Mod RS=37309.02,0,637.89,667.65,527.26,,,,,,,,,,,,,,,,,,
Chan Mod RS=36641.37,0,1548.57,2204.74,1735.22,,,,,,,,,,,,,,,,,,
Chan Mod RS=34436.63,0,1301.38,1428.67,1326.39,,,,,,,,,,,,,,,,,,
Chan Mod RS=33007.95,0,1153.81,1191,1247.61,,,,,,,,,,,,,,,,,,
Chan Mod RS=31816.96,0,1402.44,1474.93,1440.1,,,,,,,,,,,,,,,,,,
Chan Mod RS=30342.03,0,1689.44,1802.7,1883.99,,,,,,,,,,,,,,,,,,
Chan Mod RS=28539.33,0,2048.74,2229.69,1968.02,,,,,,,,,,,,,,,,,,
Chan Mod RS=26309.64,0,2020.86,2554.96,1924.11,,,,,,,,,,,,,,,,,,
Chan Mod RS=23754.68,0,495.45,766.93,611.58,,,,,,,,,,,,,,,,,,
Chan Mod RS=22987.75,0,599.82,668.94,619.75,,,,,,,,,,,,,,,,,,
Chan Mod RS=22318.81,0,589.84,721.13,658.69,,,,,,,,,,,,,,,,,,
Chan Mod RS=21597.68,0,356.74,381.35,391.7,,,,,,,,,,,,,,,,,,
Chan Mod RS=21216.33,0,337.09,354.73,360.32,,,,,,,,,,,,,,,,,,
Chan Mod RS=20861.60,0,163.2,172.77,156.81,,,,,,,,,,,,,,,,,,
Chan Mod RS=20688.83,0,211.44,266.01,254.67,,,,,,,,,,,,,,,,,,
Chan Mod RS=20422.82,0,356.27,387.08,353.88,,,,,,,,,,,,,,,,,,
Chan Mod RS=20035.74,0,355.79,438.9,428.82,,,,,,,,,,,,,,,,,,
Chan Mod RS=19596.85,0,294.02,330.3,326.64,,,,,,,,,,,,,,,,,,
Chan Mod RS=19266.55,0,157.94,158.7,157.18,,,,,,,,,,,,,,,,,,
Chan Mod RS=19107.85,0,307.94,206.28,154.61,,,,,,,,,,,,,,,,,,
Chan Mod RS=18901.57,0,1912.74,2304.93,1743.26,,,,,,,,,,,,,,,,,,
Chan Mod RS=16596.64,0,1630.52,1819.01,1392.81,,,,,,,,,,,,,,,,,,
Chan Mod RS=14777.63,0,1035.16,1114.73,1059.53,,,,,,,,,,,,,,,,,,
Chan Mod RS=13662.91,0,1855.1,1925.48,1950.49,,,,,,,,,,,,,,,,,,
Chan Mod RS=11737.43,0,982.14,1057.1,1042.11,,,,,,,,,,,,,,,,,,
Chan Mod RS=10680.33,0,373.7,378.55,388.57,,,,,,,,,,,,,,,,,,
Chan Mod RS=10301.78,0,288.36,311.42,318.02,,,,,,,,,,,,,,,,,,
Chan Mod RS=9990.368,0,72.83,73.98,74.66,,,,,,,,,,,,,,,,,,
Chan Mod RS=9916.393,0,407.11,548.99,410.17,,,,,,,,,,,,,,,,,,
Chan Mod RS=9367.406,0,301.74,440.02,328.22,,,,,,,,,,,,,,,,,,
Chan Mod RS=8927.381,0,747.89,1187.94,722.66,,,,,,,,,,,,,,,,,,
Chan Mod RS=7739.446,0,391.1,610.74,475.85,,,,,,,,,,,,,,,,,,
Chan Mod RS=7128.706,0,651.94,726.17,680.59,,,,,,,,,,,,,,,,,,
Chan Mod RS=6402.531,0,176.09,183.49,177.69,,,,,,,,,,,,,,,,,,
Chan Mod RS=6219.050,0,693.99,574.76,527.77,,,,,,,,,,,,,,,,,,
Chan Mod RS=5644.292,0,1594.63,1471.74,1313.86,,,,,,,,,,,,,,,,,,
Chan Mod RS=4172.550,0,794.37,780.98,660.94,,,,,,,,,,,,,,,,,,
Chan Mod RS=3391.567,0,210.67,181.41,197.95,,,,,,,,,,,,,,,,,,
Chan Mod RS=3210.163,0,699.89,915.78,1002.18,,,,,,,,,,,,,,,,,,
Chan Mod RS=2294.386,0,519.55,607.58,673.53,,,,,,,,,,,,,,,,,,
Chan Mod RS=1686.803,0,448.25,1686.8,798.95,,,,,,,,,,,,,,,,,,