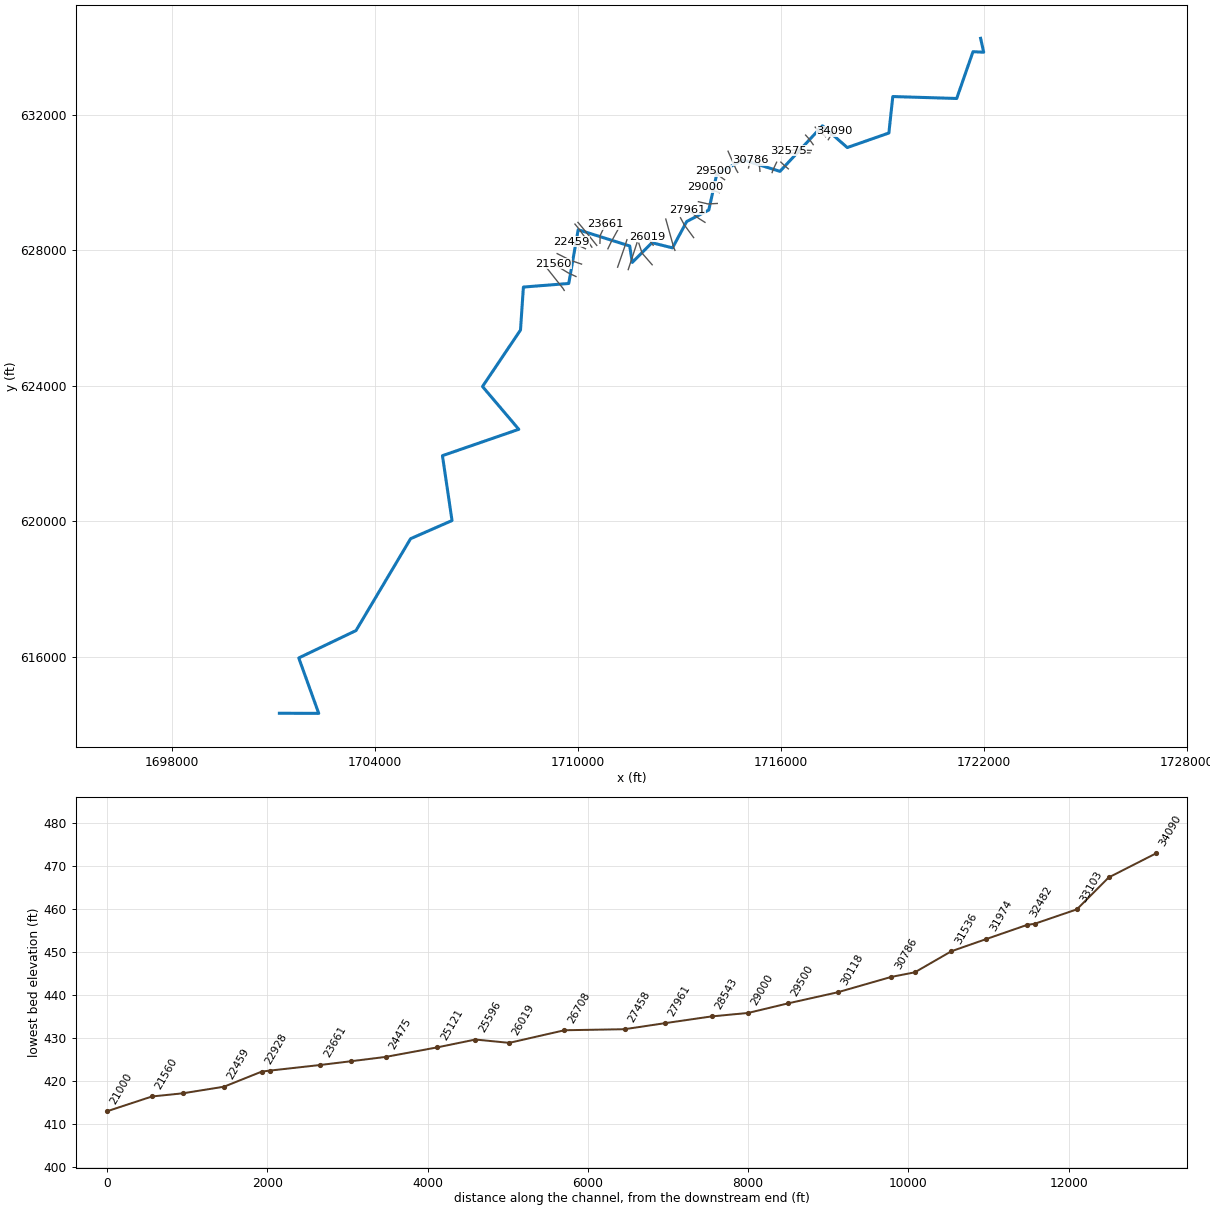
--- Barnes Creek.prj (project) ---

Proj Title=Barnes Creek Limited Detail Study
Current Plan=p01
Default Exp/Contr=0.3,0.1
English Units
Geom File=g01
Flow File=f01
Plan File=p01
Y Axis Title=Elevation
X Axis Title(PF)=Main Channel Distance
X Axis Title(XS)=Station
BEGIN DESCRIPTION:
Barnes Creek
END DESCRIPTION:
DSS Export Rating Curves= 0
DSS Export Rating Curve Sorted= 0
DSS Export Volume Flow Curves= 0
DXF OffsetX= 0
DXF OffsetY= 0
DXF ScaleX= 1
DXF ScaleY= 10

--- Barnes Creek.p01 (plan) ---

Plan Title=100-Year Single
Program Version=3.12
Short Identifier=100Year
Geom File=g01
Flow File=f01
Subcritical Flow
K Sum by GR= 0
Std Step Tol= 0.01
Critical Tol= 0.01
Num of Std Step Trials= 20
Max Error Tol= 0.3
Flow Tol Ratio= 0.001
Split Flow NTrial= 30
Split Flow Tol= 0.02
Split Flow Ratio= 0.02
Log Output Level= 0
Friction Slope Method= 1
Unsteady Friction Slope Method= 2
Unsteady Bridges Friction Slope Method= 1
Parabolic Critical Depth
Global Vel Dist= 0 , 0 , 0
Global Log Level= 0
CheckData=True
Encroach Param=-1 ,10,10, 2
Encroach River=Barnes Creek
Encroach Reach=Reach-1
Encroach Node=34090
       1 4962.26 5030.08
Encroach Node=33500
       1    4853  5021.1
Encroach Node=33103
       1    4902 5056.22
Encroach Node=32575
       1    4969    5031
Encroach Node=32482
       1    4974    5026
Encroach Node=31974
       1    4966    5045
Encroach Node=31536
       1  4976.8  5023.2
Encroach Node=31081
       1 4969.04  5023.2
Encroach Node=30786
       1 4965.92  5023.2
Encroach Node=30118
       1  4974.4 5029.04
Encroach Node=29500
       1 4922.97 5084.26
Encroach Node=29000
       1 4940.74  5025.6
Encroach Node=28543
       1 4966.35  5030.3
Encroach Node=27961
       1 4899.48 5211.37
Encroach Node=27458
       1 4769.37  5025.6
Encroach Node=26708
       1  4964.7  5025.6
Encroach Node=26019
       1  4974.4  5025.6
Encroach Node=25596
       1 4883.93 5061.85
Encroach Node=25121
       1  4974.4 5088.82
Encroach Node=24475
       1 4960.65  5026.2
Encroach Node=24040
       1 4966.82 5094.05
Encroach Node=23661
       1 4952.58 5072.67
Encroach Node=23034
       1  4767.5  5032.5
Encroach Node=22928
       1  4767.5  5032.5
Encroach Node=22459
       1  4946.8  5026.5
Encroach Node=21942
       1 4948.12 5077.23
Encroach Node=21560
       1 4939.81  5026.5
Encroach Node=21000
       1  4973.5  5026.5
Encroach Node=20500
       1  4973.5 5058.65
Encroach Node=19878
       1  4973.5  5026.5
Encroach Node=19500
       1  4973.3 5113.92
Encroach Node=18980
       1 4878.59  5026.7
Encroach Node=18521
       1  4973.3 5030.77
Encroach Node=18000
       1  4982.3    5030
Encroach Node=17500
       1  4982.3    5060
Encroach Node=17027
       1  4982.3 5106.94
Encroach Node=16404
       1  4973.3  5026.7
Encroach Node=15907
       1 4965.46  5026.7
Encroach Node=15404
       1 4968.58  5026.7
Encroach Node=14500
       1    4982    5095
Encroach Node=13745
       1    4973    5027
Encroach Node=13365
       1    4973    5027
Encroach Node=12938
       1 4967.54    5027
Encroach Node=12183
       1 4956.53 5031.65
Encroach Node=11689
       1 4972.32 5036.64
Encroach Node=11000
       1    4973 5033.71
Encroach Node=10500
       1    4973    5027
Encroach Node=10000
       1 4969.75 5090.29
Encroach Node=9292
       1    4410    5028
Encroach Node=8862
       1    4960    5070
Encroach Node=8420
       1    4950    5019
Encroach Node=7902
       1    4970    5019
Encroach Node=7404
       1    4972    5028
Encroach Node=7000
       1    4972    5028
Encroach Node=6317
       1 4968.26 5064.22
Encroach Node=5802
       1  4971.7  5028.3
Encroach Node=5231
       1 4969.83  5028.3
Encroach Node=4913
       1  4958.9  5028.3
Encroach Node=4596
       1  4971.7  5028.3
Encroach Node=4172
       1    4970  5018.3
Encroach Node=3808
       1    4963    5037
Encroach Node=3696
       1    4963    5037
Encroach Node=3259
       1 4955.28  5028.3
Encroach Node=2887
       1 4963.48  5018.3
Encroach Node=2500
       1  4971.7  5028.3
Encroach Node=2000
       1 4971.42 5108.82
Encroach Node=1500
       1  4971.7  5028.3
Encroach Node=768
       1 4898.52 5056.12
Encroach Node=171
       1  4955.6 5102.91
BEGIN DESCRIPTION:
100Year Run
END DESCRIPTION:
Computation Interval=1HOUR
Output Interval=1HOUR
Run HTab= 0
Run UNet= 0
Run PostProcess= 0
UNET Theta= 1
UNET Theta Warmup= 1
UNET ZTol= 0.02
UNET ZSATol= 0.05
UNET MxIter= 20
UNET MaxInSteps= 0
UNET DtIC= 0
UNET DtMin= 0
UNET MaxCRTS= 20
UNET WFStab= 2
UNET SFStab= 1
UNET WFX= 1
UNET SFX= 1
UNET DSS MLevel= 4
UNET DZMax Abort= 100
UNET Convert EG Bridges=-1
UNET Use Existing IB Tables=-1
UNET Froude Reduction=False
UNET Froude Limit= 1
UNET Froude Power= 10
Instantaneous Interval=1HOUR
Write IC File= 0
Echo Input=False
Echo Output=False
Write Detailed= 0
Detailed Automatic Start=False, 10

--- Barnes Creek.f01 (steady flow) ---

Flow Title=100-year Single
Program Version=3.12
Number of Profiles= 2
Profile Names=100-year,100-FW
River Rch & RM=Barnes Creek,Reach-1         ,34090
    3458    3458
River Rch & RM=Barnes Creek,Reach-1         ,33103
    4054    4054
River Rch & RM=Barnes Creek,Reach-1         ,30118
    4687    4687
River Rch & RM=Barnes Creek,Reach-1         ,24475
    4838    4838
River Rch & RM=Barnes Creek,Reach-1         ,23034
    4913    4913
River Rch & RM=Barnes Creek,Reach-1         ,19500
    4965    4965
River Rch & RM=Barnes Creek,Reach-1         ,14500
    5040    5040
River Rch & RM=Barnes Creek,Reach-1         ,9292
    5263    5263
River Rch & RM=Barnes Creek,Reach-1         ,6317
    5335    5335
River Rch & RM=Barnes Creek,Reach-1         ,3259
    5348    5348
River Rch & RM=Barnes Creek,Reach-1         ,768
    5452    5452
Boundary for River Rch & Prof#=Barnes Creek,Reach-1         , 1
Up Type= 0
Dn Type= 3
Dn Slope=0.0019
Boundary for River Rch & Prof#=Barnes Creek,Reach-1         , 2
Up Type= 0
Dn Type= 3
Dn Slope=0.0019
DSS Import GetInterval= 0
DSS Import GetPeak= 0
DSS Import FillOption= 0

--- Barnes Creek.g01 (geometry) ---

Geom Title=Existing Conditions
Program Version=3.12

River Reach=Barnes Creek    ,Reach-1
Reach XY= 30
      1721906.27       634266.66      1721997.22       633855.93
      1721681.27       633871.65      1721199.83       632489.62
      1719311.74       632546.69      1719195.41       631469.37
      1717966.35       631039.45      1717232.85       631682.75
      1715978.62       630336.41      1714891.18       630675.28
      1714112.27        630265.6      1713874.55       629193.33
      1713222.09       628854.46      1712802.29       628075.55
      1712195.34       628227.28      1711613.69       627645.63
      1711537.82       628131.18      1710015.41       628611.68
      1709737.23       627023.51       1708396.9        626917.3
      1708310.91       625647.78      1707188.07       623978.69
      1708260.34       622714.22      1706004.53       621935.31
      1706287.77       620018.39      1705063.77       619482.26
      1703450.45       616767.65      1701759.25       615958.57
       1702349.2       614320.75      1701186.84       614324.38

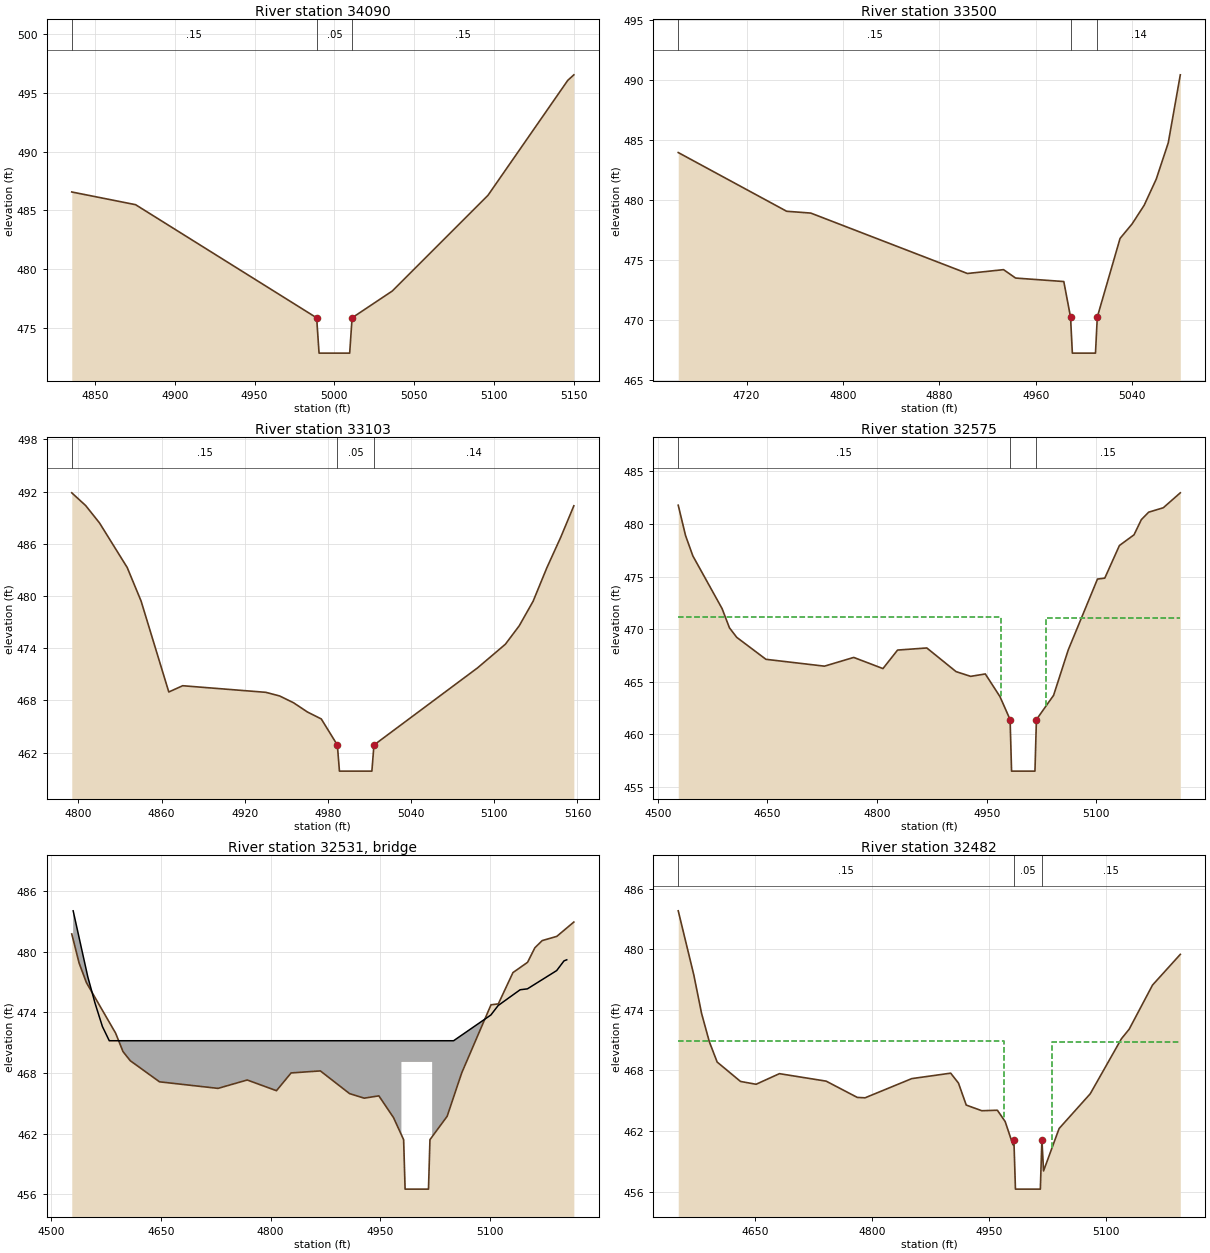
Type RM Length L Ch R = 1 ,34090   ,590,590,590
BEGIN DESCRIPTION:
Barnes Creek 68.0
END DESCRIPTION:
XS GIS Cut Line= 3
      1717405.39       631271.41      1717486.31       631410.49
       1717592.5       631521.74
#Sta/Elev= 10
  4835.4  486.56  4875.4  485.48  4988.9  475.86  4990.4  472.86  5009.6  472.86
  5011.1  475.86  5036.3  478.14  5096.3  486.28  5146.3  496.05  5150.1  496.52
#Mann= 3 ,-1 , 0
  4835.4     .15       0  4988.9     .05       0  5011.1     .15       0
Bank Sta=4988.9,5011.1
Exp/Cntr=0.3,0.1

Type RM Length L Ch R = 1 ,33500   ,397,397,397
BEGIN DESCRIPTION:
Barnes Creek 67.0
END DESCRIPTION:
XS GIS Cut Line= 3
      1717324.52        631359.9      1717076.16       631587.25
      1717018.98       631643.19
#Sta/Elev= 17
  4663.3  483.97  4753.3  479.08  4773.3  478.93  4903.3   473.9  4933.3  474.22
  4943.3  473.52  4983.3  473.23  4988.9  470.27  4990.4  467.27  5009.6  467.27
  5011.1  470.27    5030  476.82    5040  478.03    5050  479.58    5060  481.75
    5070  484.78    5080  490.44
#Mann= 3 ,-1 , 0
  4663.3     .15       0  4988.9     .05       0  5011.1     .14       0
Bank Sta=4988.9,5011.1
Exp/Cntr=0.3,0.1

Type RM Length L Ch R = 1 ,33103   ,528,528,528
BEGIN DESCRIPTION:
Barnes Creek 66.0
END DESCRIPTION:
XS GIS Cut Line= 3
      1716960.43       631124.76      1716841.58       631289.13
      1716735.39       631407.96
#Sta/Elev= 23
  4795.2  491.86  4805.2   490.4  4815.2   488.4  4835.2  483.27  4845.2  479.42
  4865.2  468.96  4875.2  469.68  4935.2  468.92  4945.2   468.5  4955.2  467.72
  4965.2  466.66  4975.2  465.86  4986.8  462.86  4988.3  459.86  5011.7  459.86
  5013.2  462.86    5088  471.74    5108  474.45    5118  476.57    5128  479.39
    5138  483.27    5148  486.77  5157.4  490.37
#Mann= 3 ,-1 , 0
  4795.2     .15       0  4986.8     .05       0  5013.2     .14       0
Bank Sta=4986.8,5013.2
Exp/Cntr=0.5,0.3

Type RM Length L Ch R = 1 ,32575   ,93,93,93
BEGIN DESCRIPTION:
FLINT-HILL-RD-US
END DESCRIPTION:
XS GIS Cut Line= 3
      1716903.32       630954.57      1716430.29       630972.81
      1716218.84       630944.69
#Sta/Elev= 30
  4528.1  481.78  4538.1   478.9  4548.1  476.96  4588.1  471.95  4598.1  470.13
  4608.1  469.22  4648.1  467.13  4728.1  466.48  4768.1  467.31  4808.1  466.25
  4828.1  468.01  4868.1  468.21  4908.1  465.96  4928.1  465.51  4948.1  465.74
  4968.1  463.59    4982   461.4    4984   456.5    5016   456.5    5018   461.4
  5041.5  463.71  5061.5  468.02  5101.5  474.76  5111.5  474.85  5131.5  477.95
  5151.5  478.97  5161.5  480.41  5171.5  481.12  5191.5  481.54  5214.8  482.96
#Mann= 3 ,-1 , 0
  4528.1     .15       0    4982     .05       0    5018     .15       0
#XS Ineff= 2 , 0
       0    4969   471.2    5031       0  471.03
Permanent Ineff=
       F       F
Bank Sta=4982,5018
Exp/Cntr=0.5,0.3

Type RM Length L Ch R = 3 ,32531   ,,,
BEGIN DESCRIPTION:
FLINT-HILL-RD-TOR
Structure ID: LDS_BAC_03
Approximate Survey Structure
END DESCRIPTION:
Bridge Culvert--1,0,-1,-1, 0
Deck Dist Width WeirC Skew NumUp NumDn MinLoCord MaxHiCord MaxSubmerge Is_Ogee
33.5,21,3,0, 17, 17, , , 0.95, 0, 1,1,,
    4530    4550    4560    4570  4579.4    4979    4979    5021    5021  5050.3
  5101.3  5111.3  5141.3  5151.3  5191.3  5201.3  5205.1
  484.07  477.54   474.9  472.61   471.2   471.2   471.2   471.2   471.2   471.2
  473.75  474.69  476.25  476.34  478.15  479.11  479.22
   436.5   436.5   436.5   436.5   436.5   436.5   469.1   469.1   436.5   436.5
   436.5   436.5   436.5   436.5   436.5   436.5   436.5
    4530    4550    4560    4570  4579.4    4979    4979    5021    5021  5050.3
  5101.3  5111.3  5141.3  5151.3  5191.3  5201.3  5205.1
  484.07  477.54   474.9  472.61   471.2   471.2   471.2   471.2   471.2   471.2
  473.75  474.69  476.25  476.34  478.15  479.11  479.22
   436.5   436.5   436.5   436.5   436.5   436.5   469.1   469.1   436.5   436.5
   436.5   436.5   436.5   436.5   436.5   436.5   436.5
BR Coef= 1 , 1 , 0 ,1.25, 0 ,,,0.8,0,2,0,
WSPro=,,,, 1 ,,,, 0 ,,,, 0 ,,,,-1 ,-1 ,-1 , 0 , 0 , 0 , 0 , 0
BC Design=,, 0 ,, 0 ,,,,,,
BC HTab HWMax=483.07

Type RM Length L Ch R = 1 ,32482   ,508,508,508
BEGIN DESCRIPTION:
FLINT-HILL-RD-DS
END DESCRIPTION:
XS GIS Cut Line= 3
      1716864.38       630881.61      1716415.09       630883.19
      1716221.11       630857.28
#Sta/Elev= 30
  4550.8   483.8  4570.8  477.46  4580.8  473.64  4590.8  470.83  4600.8  468.83
  4630.8  466.91  4650.8  466.63  4680.8  467.68  4740.8  466.94  4780.8  465.33
  4790.8  465.29  4850.8  467.19  4900.8  467.73  4910.8  466.75  4920.8  464.57
  4940.8  464.01  4960.8  464.06  4970.8  462.94  4980.8  460.64    4982  461.15
    4984  456.25    5016  456.25    5018  461.15  5020.1  458.05  5040.1  462.25
  5080.1  465.69  5120.1  471.13  5130.1  472.08  5160.1  476.45  5195.8  479.49
#Mann= 3 ,-1 , 0
  4550.8     .15       0    4982     .05       0    5018     .15       0
#XS Ineff= 2 , 0
       0    4969  470.91    5031       0  470.81
Permanent Ineff=
       F       F
Bank Sta=4982,5018
Exp/Cntr=0.5,0.3

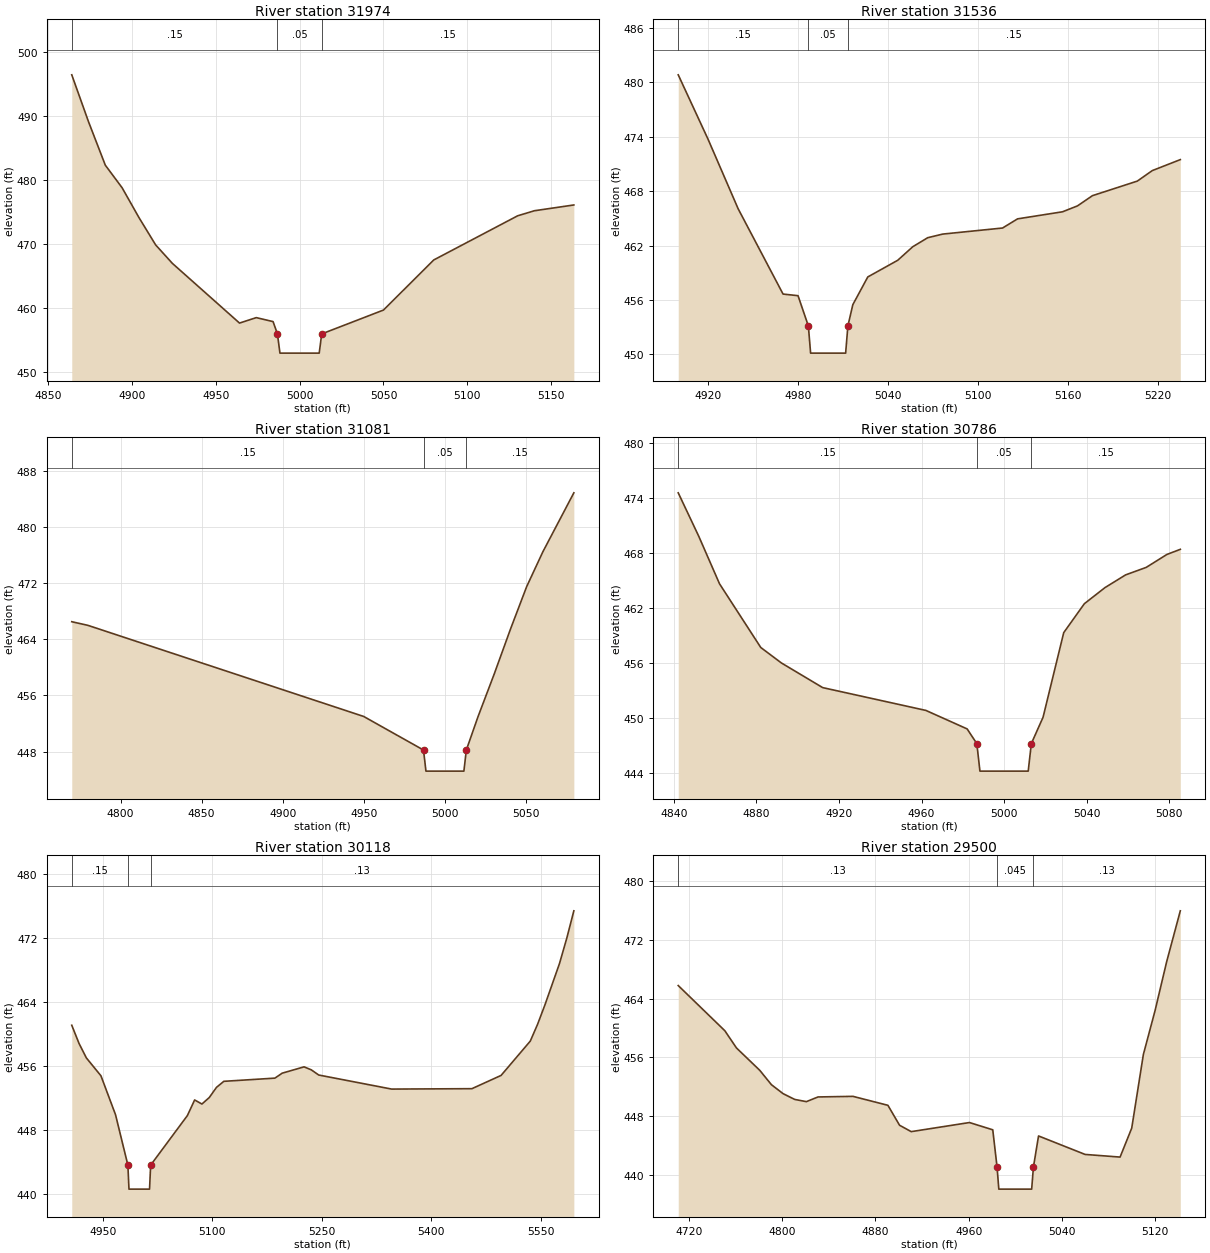
Type RM Length L Ch R = 1 ,31974   ,438,438,438
BEGIN DESCRIPTION:
Barnes Creek 64.0
END DESCRIPTION:
XS GIS Cut Line= 3
      1716225.54       630409.06      1716122.19       630497.21
       1716003.6       630609.72
#Sta/Elev= 19
  4864.2   496.4  4874.2  489.07  4884.2   482.3  4894.2  478.78  4904.2  474.15
  4914.2  469.86  4924.2  466.97  4964.2  457.66  4974.2  458.51  4984.2  457.89
  4986.8  455.97  4988.3  452.97  5011.7  452.97  5013.2  455.97    5050  459.69
    5080  467.51    5130   474.4    5140  475.19  5163.5  476.09
#Mann= 3 ,-1 , 0
  4864.2     .15       0  4986.8     .05       0  5013.2     .15       0
Bank Sta=4986.8,5013.2
Exp/Cntr=0.3,0.1

Type RM Length L Ch R = 1 ,31536   ,455,455,455
BEGIN DESCRIPTION:
Barnes Creek 63.0
END DESCRIPTION:
XS GIS Cut Line= 3
      1715745.24       630299.61      1715777.15       630390.81
        1715879.       630606.67
#Sta/Elev= 23
  4899.9  480.84  4919.9   473.7  4939.9  466.06  4969.9  456.64  4979.9  456.46
  4986.8  453.12  4988.3  450.12  5011.7  450.12  5013.2  453.12  5016.5  455.47
  5026.5  458.53  5046.5  460.37  5056.5  461.86  5066.5  462.86  5076.5  463.26
  5116.5  463.93  5126.5  464.94  5156.5  465.72  5166.5  466.37  5176.5   467.5
  5206.5  469.11  5216.5  470.27  5235.2  471.48
#Mann= 3 ,-1 , 0
  4899.9     .15       0  4986.8     .05       0  5013.2     .15       0
Bank Sta=4986.8,5013.2
Exp/Cntr=0.3,0.1

Type RM Length L Ch R = 1 ,31081   ,295,295,295
BEGIN DESCRIPTION:
Barnes Creek 62.0
END DESCRIPTION:
XS GIS Cut Line= 3
      1715386.52       630337.56      1715365.24       630567.13
      1715363.72       630646.16
#Sta/Elev= 13
  4769.9  466.49  4779.9  465.97  4949.9  453.01  4986.8  448.23  4988.3  445.23
  5011.7  445.23  5013.2  448.23  5020.4  452.97  5030.4  459.05  5040.4  465.42
  5050.4  471.48  5060.4  476.44  5079.5  484.83
#Mann= 3 ,-1 , 0
  4769.9     .15       0  4986.8     .05       0  5013.2     .15       0
Bank Sta=4986.8,5013.2
Exp/Cntr=0.3,0.1

Type RM Length L Ch R = 1 ,30786   ,668,668,668
BEGIN DESCRIPTION:
Barnes Creek 61.0
END DESCRIPTION:
XS GIS Cut Line= 3
      1715049.09       630436.41        1715081.       630589.93
      1715108.36       630671.99
#Sta/Elev= 20
  4842.1  474.55  4852.1  469.78  4862.1  464.62  4882.1  457.66  4892.1  455.97
  4912.1  453.28  4962.1  450.79  4982.1  448.77  4986.8  447.16  4988.3  444.16
  5011.7  444.16  5013.2  447.16  5018.9  450.05  5028.9  459.28  5038.9  462.44
  5048.9   464.2  5058.9  465.59  5068.9  466.41  5078.9  467.82  5085.4  468.38
#Mann= 3 ,-1 , 0
  4842.1     .15       0  4986.8     .05       0  5013.2     .15       0
Bank Sta=4986.8,5013.2
Exp/Cntr=0.3,0.1

Type RM Length L Ch R = 1 ,30118   ,618,618,618
BEGIN DESCRIPTION:
Barnes Creek 60.0
END DESCRIPTION:
XS GIS Cut Line= 3
      1714731.08       630306.77      1714685.95       630382.78
      1714443.71       630931.38
#Sta/Elev= 29
  4907.5  461.08  4917.5   458.8  4927.5     457  4947.5  454.76  4967.5  449.89
  4984.4  443.59  4985.9  440.59  5014.1  440.59  5015.6  443.59  5065.9  449.78
  5075.9  451.74  5085.9  451.23  5095.9  452.04  5105.9  453.32  5115.9  454.07
  5185.9  454.47  5195.9  455.09  5225.9  455.88  5235.9   455.5  5245.9  454.86
  5345.9   453.1  5455.9  453.15  5495.9  454.81  5535.9   459.1  5545.9   461.2
  5555.9  463.61  5575.9  468.79  5585.9  471.96  5595.6  475.39
#Mann= 3 ,-1 , 0
  4907.5     .15       0  4984.4    .045       0  5015.6     .13       0
Bank Sta=4984.4,5015.6
Exp/Cntr=0.3,0.1

Type RM Length L Ch R = 1 ,29500   ,500,500,500
BEGIN DESCRIPTION:
Barnes Creek 59.0
END DESCRIPTION:
XS GIS Cut Line= 3
      1714341.55       630088.31      1714106.73        630257.3
      1713997.19       630347.18
#Sta/Elev= 27
  4710.7  465.78  4750.7  459.62  4760.7  457.27  4780.7  454.22  4790.7  452.26
  4800.7  451.04  4810.7  450.25  4820.7  449.95  4830.7  450.59  4860.7  450.67
  4890.7  449.45  4900.7  446.73  4910.7  445.86  4960.7   447.1  4980.7  446.11
  4984.4  441.02  4985.9  438.02  5014.1  438.02  5015.6  441.02    5020  445.27
    5060  442.75    5090  442.39    5100  446.34    5110  456.39    5120  462.35
    5130  469.04  5141.7  475.97
#Mann= 3 ,-1 , 0
  4710.7     .13       0  4984.4    .045       0  5015.6     .13       0
Bank Sta=4984.4,5015.6
Exp/Cntr=0.3,0.1

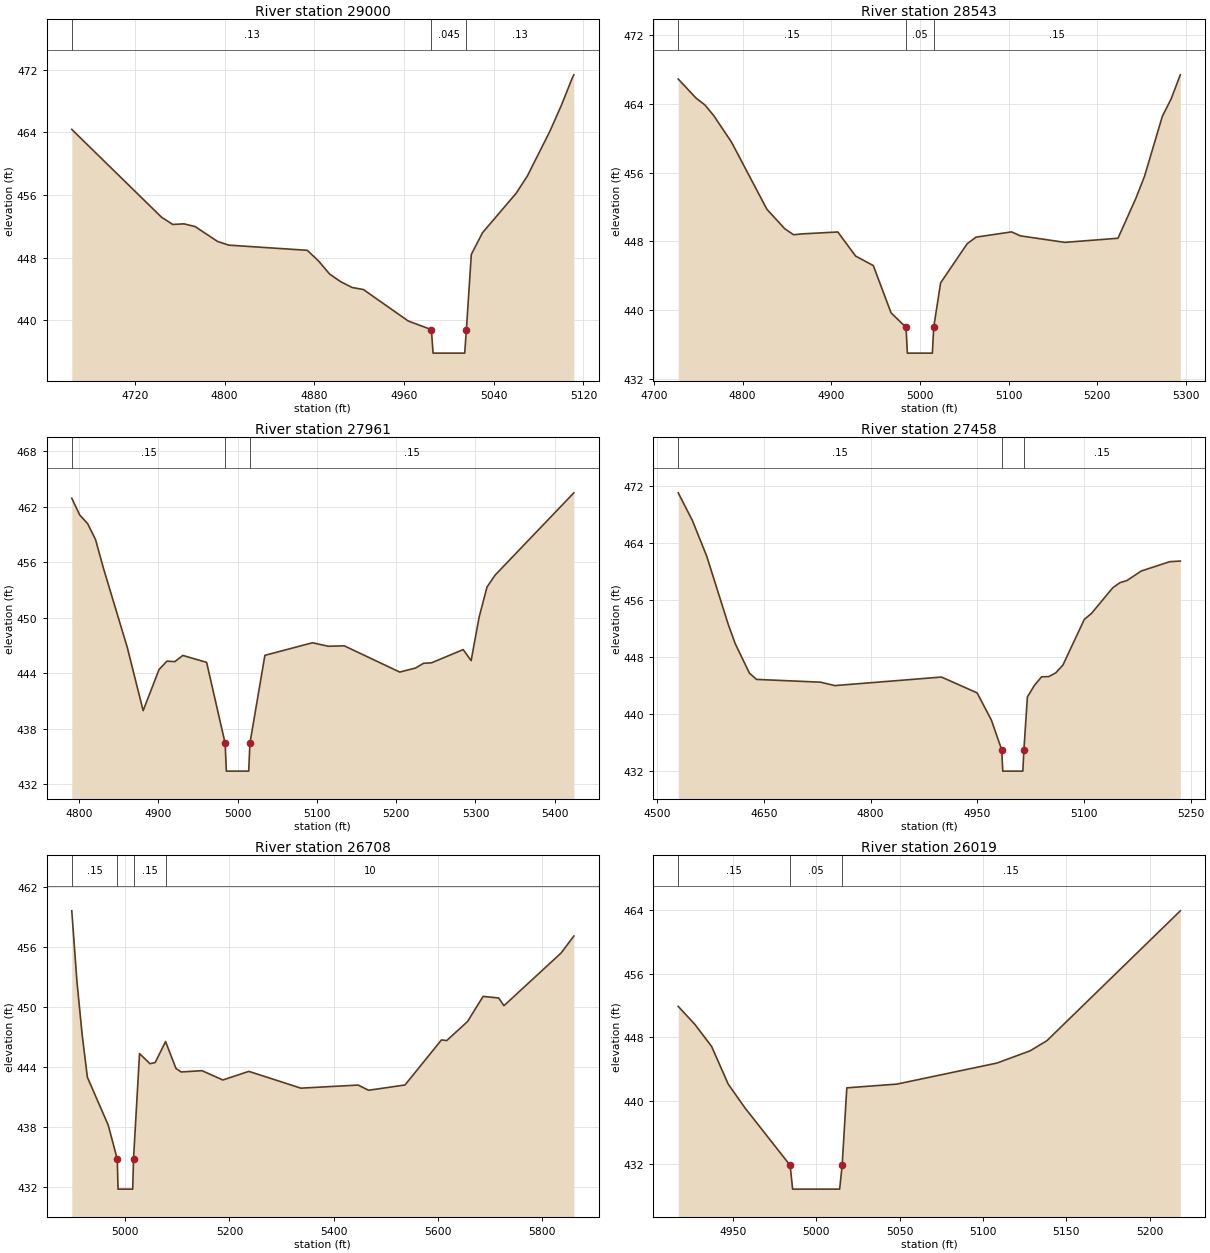
Type RM Length L Ch R = 1 ,29000   ,457,457,457
BEGIN DESCRIPTION:
Barnes Creek 58.0
END DESCRIPTION:
XS GIS Cut Line= 3
      1714187.21       629708.29      1713870.37       629820.75
      1713771.56       629872.18
#Sta/Elev= 26
  4663.8  464.36  4743.8  453.15  4753.8  452.22  4763.8   452.3  4773.8  451.95
  4793.8  450.05  4803.8  449.58  4873.8  448.92  4883.8  447.56  4893.8  445.87
  4903.8  444.89  4913.8  444.17  4923.8  443.91  4963.8  439.89  4984.4  438.79
  4985.9  435.79  5014.1  435.79  5015.6  438.79    5020   448.4    5030  451.17
    5060  456.21    5070  458.42    5090  464.11    5100  467.34    5110  470.93
  5111.4  471.33
#Mann= 3 ,-1 , 0
  4663.8     .13       0  4984.4    .045       0  5015.6     .13       0
Bank Sta=4984.4,5015.6
Exp/Cntr=0.3,0.1

Type RM Length L Ch R = 1 ,28543   ,582,582,582
BEGIN DESCRIPTION:
Barnes Creek 57.0
END DESCRIPTION:
XS GIS Cut Line= 3
      1714125.49       629387.67      1713849.96       629373.42
      1713567.37       629439.91
#Sta/Elev= 30
  4727.5  466.88  4747.5  464.67  4757.5  463.87  4767.5  462.63  4787.5  459.55
  4827.5  451.72  4847.5  449.47  4857.5  448.76  4867.5  448.86  4907.5  449.08
  4927.5  446.28  4947.5  445.17  4967.5  439.67  4984.4  437.98  4985.9  434.98
  5014.1  434.98  5015.6  437.98  5023.4  443.16  5053.4  447.72  5063.4  448.48
  5103.4  449.09  5113.4  448.63  5163.4  447.87  5223.4  448.35  5243.4  452.95
  5253.4  455.58  5273.4  462.53  5283.4  464.58  5293.4  467.29  5293.7  467.37
#Mann= 3 ,-1 , 0
  4727.5     .15       0  4984.4     .05       0  5015.6     .15       0
Bank Sta=4984.4,5015.6
Exp/Cntr=0.3,0.1

Type RM Length L Ch R = 1 ,27961   ,503,503,503
BEGIN DESCRIPTION:
Barnes Creek 56.0
END DESCRIPTION:
XS GIS Cut Line= 3
      1713762.09       628829.55      1713581.59       628943.55
      1713251.47       629202.42
#Sta/Elev= 30
    4791  462.92    4801  461.11    4811  460.17    4821  458.44    4831  455.33
    4861  446.78    4881  439.95    4901  444.39    4911   445.3    4921  445.25
    4931  445.92    4961  445.17  4984.4  436.41  4985.9  433.41  5014.1  433.41
  5015.6  436.41  5034.5  445.93  5094.5  447.29  5114.5  446.91  5134.5  446.96
  5204.5  444.12  5224.5  444.56  5234.5  445.07  5244.5  445.12  5284.5  446.55
  5294.5  445.36  5304.5  450.03  5314.5  453.31  5324.5  454.58    5424   463.5
#Mann= 3 ,-1 , 0
    4791     .15       0  4984.4     .05       0  5015.6     .15       0
Bank Sta=4984.4,5015.6
Exp/Cntr=0.3,0.1

Type RM Length L Ch R = 1 ,27458   ,750,750,750
BEGIN DESCRIPTION:
Barnes Creek 55.0
END DESCRIPTION:
XS GIS Cut Line= 3
       1713427.2       628378.33      1713149.35        628758.3
      1713037.71       628964.95
#Sta/Elev= 30
  4529.8  471.09  4549.8  467.18  4569.8  462.21  4599.8   452.7  4609.8  449.93
  4629.8  445.78  4639.8  444.89  4729.8   444.5  4749.8  444.02  4899.8  445.22
  4949.8     443  4969.8   439.2  4984.4  435.01  4985.9  432.01  5014.1  432.01
  5015.6  435.01  5020.5  442.43  5030.5  444.07  5040.5  445.26  5050.5  445.28
  5060.5  445.82  5070.5  446.92  5100.5  453.32  5110.5  454.15  5140.5  457.76
  5150.5  458.47  5160.5  458.78  5180.5  460.11  5220.5  461.42  5235.4  461.51
#Mann= 3 ,-1 , 0
  4529.8     .15       0  4984.4     .05       0  5015.6     .15       0
Bank Sta=4984.4,5015.6
Exp/Cntr=0.3,0.1

Type RM Length L Ch R = 1 ,26708   ,689,689,689
BEGIN DESCRIPTION:
Barnes Creek 54.0
END DESCRIPTION:
XS GIS Cut Line= 3
      1712874.95       628001.81      1712836.41       628094.31
      1712603.89       628926.74
#Sta/Elev= 30
    4897  459.61    4907  452.51    4917   447.2    4927  442.96    4967  438.18
  4984.4  434.77  4985.9  431.77  5014.1  431.77  5015.6  434.77  5027.2  445.33
  5047.2  444.32  5057.2  444.43  5077.2  446.53  5097.2  443.84  5107.2  443.49
  5147.2  443.62  5187.2  442.69  5237.2  443.55  5337.2  441.87  5447.2  442.18
  5467.2  441.66  5537.2  442.19  5607.2   446.7  5617.2  446.63  5657.2  448.53
  5687.2  451.05  5717.2  450.89  5727.2  450.12  5837.2   455.4  5861.5  457.09
#Mann= 4 ,-1 , 0
    4897     .15       0  4984.4     .05       0  5015.6     .15       0
  5077.2      10       0
Bank Sta=4984.4,5015.6
Exp/Cntr=0.3,0.1

Type RM Length L Ch R = 1 ,26019   ,423,423,423
BEGIN DESCRIPTION:
Barnes Creek 52.0
END DESCRIPTION:
XS GIS Cut Line= 3
      1712230.25       628152.67      1712187.49       628221.56
      1712065.94       628404.95
#Sta/Elev= 15
  4917.3  451.86  4927.3  449.59  4937.3  446.82  4947.3  442.06  4957.3  439.08
  4984.4  431.84  4985.9  428.84  5014.1  428.84  5015.6  431.84  5018.4   441.6
  5048.4  442.07  5108.4  444.72  5128.4  446.27  5138.4  447.54  5218.4   463.9
#Mann= 3 ,-1 , 0
  4917.3     .15       0  4984.4     .05       0  5015.6     .15       0
Bank Sta=4984.4,5015.6
Exp/Cntr=0.3,0.1

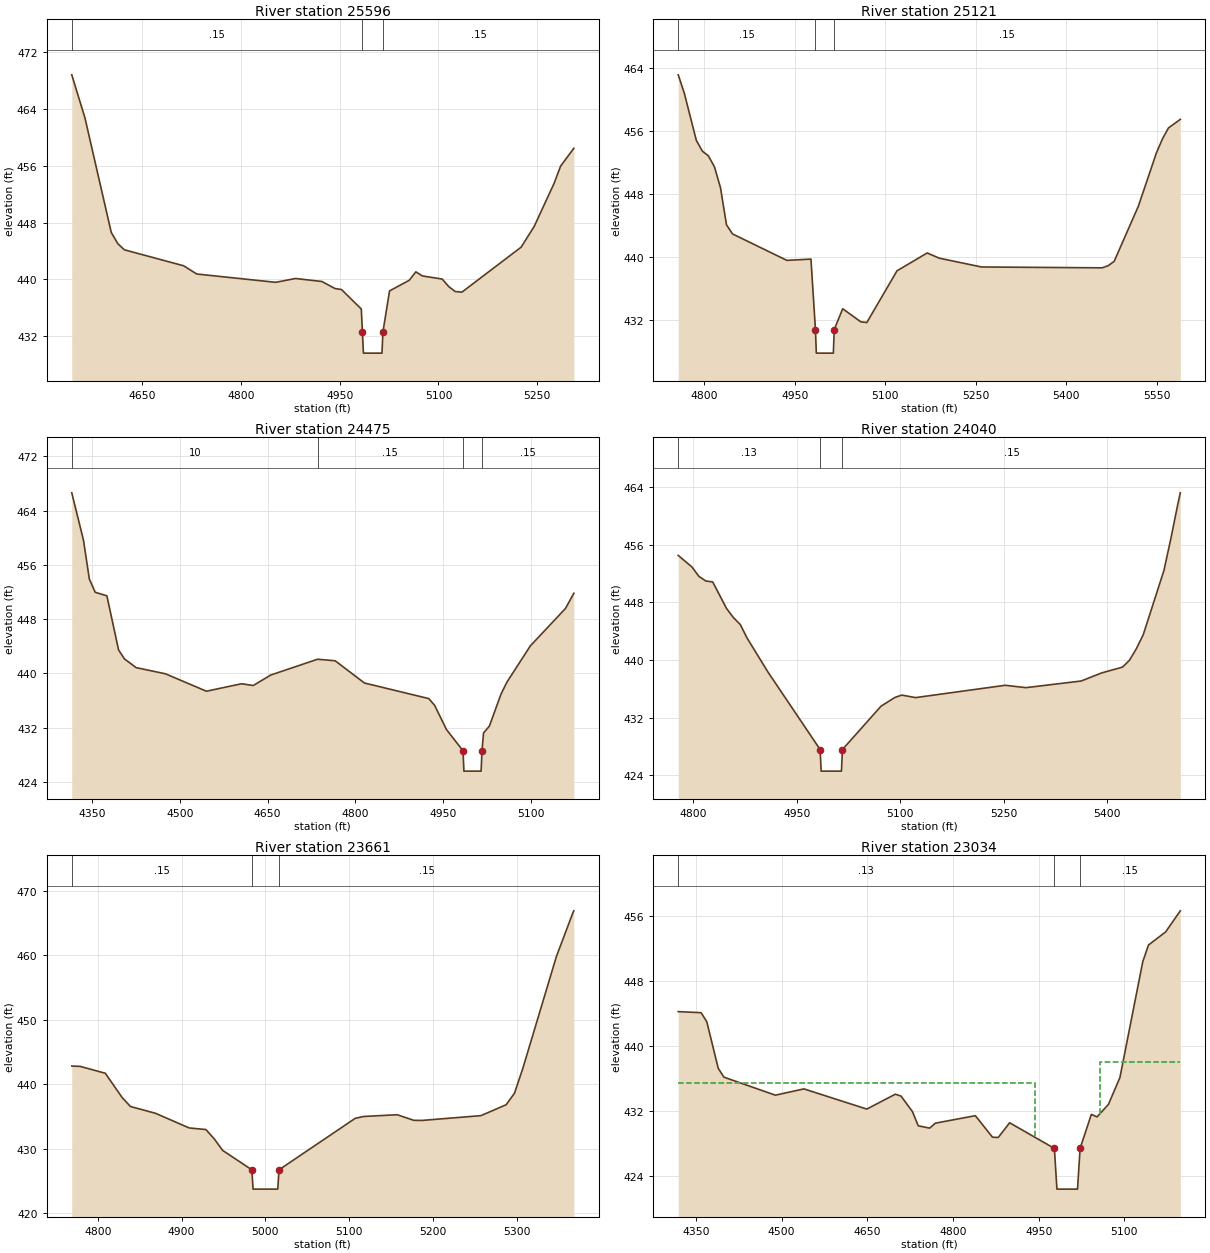
Type RM Length L Ch R = 1 ,25596   ,475,475,475
BEGIN DESCRIPTION:
Barnes Creek 51.0
END DESCRIPTION:
XS GIS Cut Line= 3
      1712201.73       627575.58      1711904.87       627917.56
       1711807.5       628212.02
#Sta/Elev= 30
  4542.7   468.8  4562.7  462.75  4602.7  446.61  4612.7  445.02  4622.7  444.16
  4712.7  441.91  4732.7  440.75  4852.7  439.58  4882.7  440.12  4922.7   439.7
  4942.7  438.71  4952.7  438.56  4982.7  435.82  4984.4  432.61  4985.9  429.61
  5014.1  429.61  5015.6  432.61  5025.6  438.37  5055.6  439.87  5065.6  441.06
  5075.6  440.48  5105.6  440.04  5115.6  438.98  5125.6  438.28  5135.6   438.2
  5225.6  444.53  5245.6  447.48  5275.6   453.5  5285.6  455.95  5305.7  458.46
#Mann= 3 ,-1 , 0
  4542.7     .15       0  4984.4     .05       0  5015.6     .15       0
Bank Sta=4984.4,5015.6
Exp/Cntr=0.3,0.1

Type RM Length L Ch R = 1 ,25121   ,646,646,646
BEGIN DESCRIPTION:
Barnes Creek 50.0
END DESCRIPTION:
XS GIS Cut Line= 3
      1711493.98       627433.02      1711569.99       627663.44
      1711752.87       628223.93
#Sta/Elev= 30
    4757  463.16    4767  460.84    4787  454.83    4797  453.46    4807  452.86
    4817  451.47    4827  448.83    4837   444.1    4847  442.94    4937  439.58
    4977  439.74  4984.4  430.79  4985.9  427.79  5014.1  427.79  5015.6  430.79
  5029.6  433.43  5059.6  431.77  5069.6  431.68  5119.6  438.25  5169.6  440.52
  5189.6  439.86  5259.6  438.74  5459.6  438.63  5469.6   438.9  5479.6  439.46
  5519.6  446.45  5549.6  453.24  5559.6  455.02  5569.6  456.41  5589.2   457.5
#Mann= 3 ,-1 , 0
    4757     .15       0  4984.4     .05       0  5015.6     .15       0
Bank Sta=4984.4,5015.6
Exp/Cntr=0.3,0.1

Type RM Length L Ch R = 1 ,24475   ,435,435,435
BEGIN DESCRIPTION:
Barnes Creek 49.0
END DESCRIPTION:
XS GIS Cut Line= 3
      1711180.51       627504.35      1711403.75       628150.31
      1711455.99       628316.55
#Sta/Elev= 30
  4315.4  466.63  4335.4  459.65  4345.4  453.92  4355.4  451.96  4375.4  451.43
  4395.4  443.44  4405.4  442.13  4425.4  440.84  4475.4  439.93  4545.4  437.36
  4605.4  438.46  4625.4   438.2  4655.4  439.75  4735.4  442.08  4765.4  441.85
  4815.4  438.57  4925.4  436.27  4935.4  435.26  4955.4  431.72  4983.8  428.57
  4985.3  425.57  5014.7  425.57  5016.2  428.57  5018.8  431.19  5028.8  432.21
  5048.8  436.96  5058.8   438.7  5098.8  444.05  5158.8  449.57  5173.1  451.81
#Mann= 4 ,-1 , 0
  4315.4      10       0  4735.4     .15       0  4983.8     .05       0
  5016.2     .15       0
Bank Sta=4983.8,5016.2
Exp/Cntr=0.3,0.1

Type RM Length L Ch R = 1 ,24040   ,379,379,379
BEGIN DESCRIPTION:
Barnes Creek 48.0
END DESCRIPTION:
XS GIS Cut Line= 3
      1710893.15       628048.22       1710990.5       628250.06
      1711232.75       628691.81
#Sta/Elev= 30
  4778.1  454.49  4798.1  452.87  4808.1  451.58  4818.1  450.94  4828.1  450.81
  4848.1  447.13  4858.1  445.86  4868.1  444.89  4878.1  442.99  4908.1  438.32
  4983.8  427.56  4985.3  424.56  5014.7  424.56  5016.2  427.56  5072.2  433.58
  5092.2  434.78  5102.2  435.11  5122.2  434.76  5252.2  436.47  5282.2  436.14
  5362.2  437.06  5392.2  438.19  5422.2  438.99  5432.2  439.93  5442.2  441.53
  5452.2  443.47  5482.2  452.38  5492.2  456.77  5502.2   461.5    5506  463.17
#Mann= 3 ,-1 , 0
  4778.1     .13       0  4983.8     .05       0  5016.2     .15       0
Bank Sta=4983.8,5016.2
Exp/Cntr=0.3,0.1

Type RM Length L Ch R = 1 ,23661   ,627,627,627
BEGIN DESCRIPTION:
Barnes Creek 47.0
END DESCRIPTION:
XS GIS Cut Line= 3
      1710658.01       628212.06      1710665.13       628440.06
      1710824.27       628774.96
#Sta/Elev= 26
    4769  442.81    4779  442.76    4809  441.69    4829  437.94    4839  436.53
    4869  435.47    4909   433.2    4929  432.95    4939   431.5    4949  429.71
  4983.8   426.7  4985.3   423.7  5014.7   423.7  5016.2   426.7  5107.1  434.69
  5117.1  434.98  5157.1  435.25  5177.1  434.38  5187.1  434.37  5257.1  435.11
  5287.1   436.8  5297.1  438.59  5307.1  442.47  5347.1  459.82  5367.1  466.72
  5367.9  466.91
#Mann= 3 ,-1 , 0
    4769     .15       0  4983.8     .05       0  5016.2     .15       0
Bank Sta=4983.8,5016.2
Exp/Cntr=0.5,0.3

Type RM Length L Ch R = 1 ,23034   ,106,106,106
BEGIN DESCRIPTION:
SR-1134-US
END DESCRIPTION:
XS GIS Cut Line= 3
        1710565.       628148.17      1710135.38       628679.17
      1710008.73       628828.31
#Sta/Elev= 30
  4319.2   444.2  4359.2  444.07  4369.2  442.96  4389.2  437.24  4399.2  436.15
  4489.2  433.94  4539.2  434.71  4649.2  432.23  4699.2  434.06  4709.2  433.82
  4729.2  431.91  4739.2  430.18  4759.2  429.89  4769.2   430.5  4839.2  431.42
  4869.2  428.78  4879.2  428.74  4899.2  430.55  4977.5   427.4    4982   422.4
    5018   422.4  5022.5   427.4  5042.2  431.58  5052.2  431.27  5072.2  432.82
  5092.2   436.1  5132.2  450.33  5142.2  452.38  5172.2  453.99  5197.9  456.58
#Mann= 3 ,-1 , 0
  4319.2     .13       0  4977.5     .05       0  5022.5     .15       0
#XS Ineff= 2 , 0
       0  4943.5  435.45  5056.5       0  437.99
Permanent Ineff=
       F       F
Bank Sta=4977.5,5022.5
Exp/Cntr=0.5,0.3

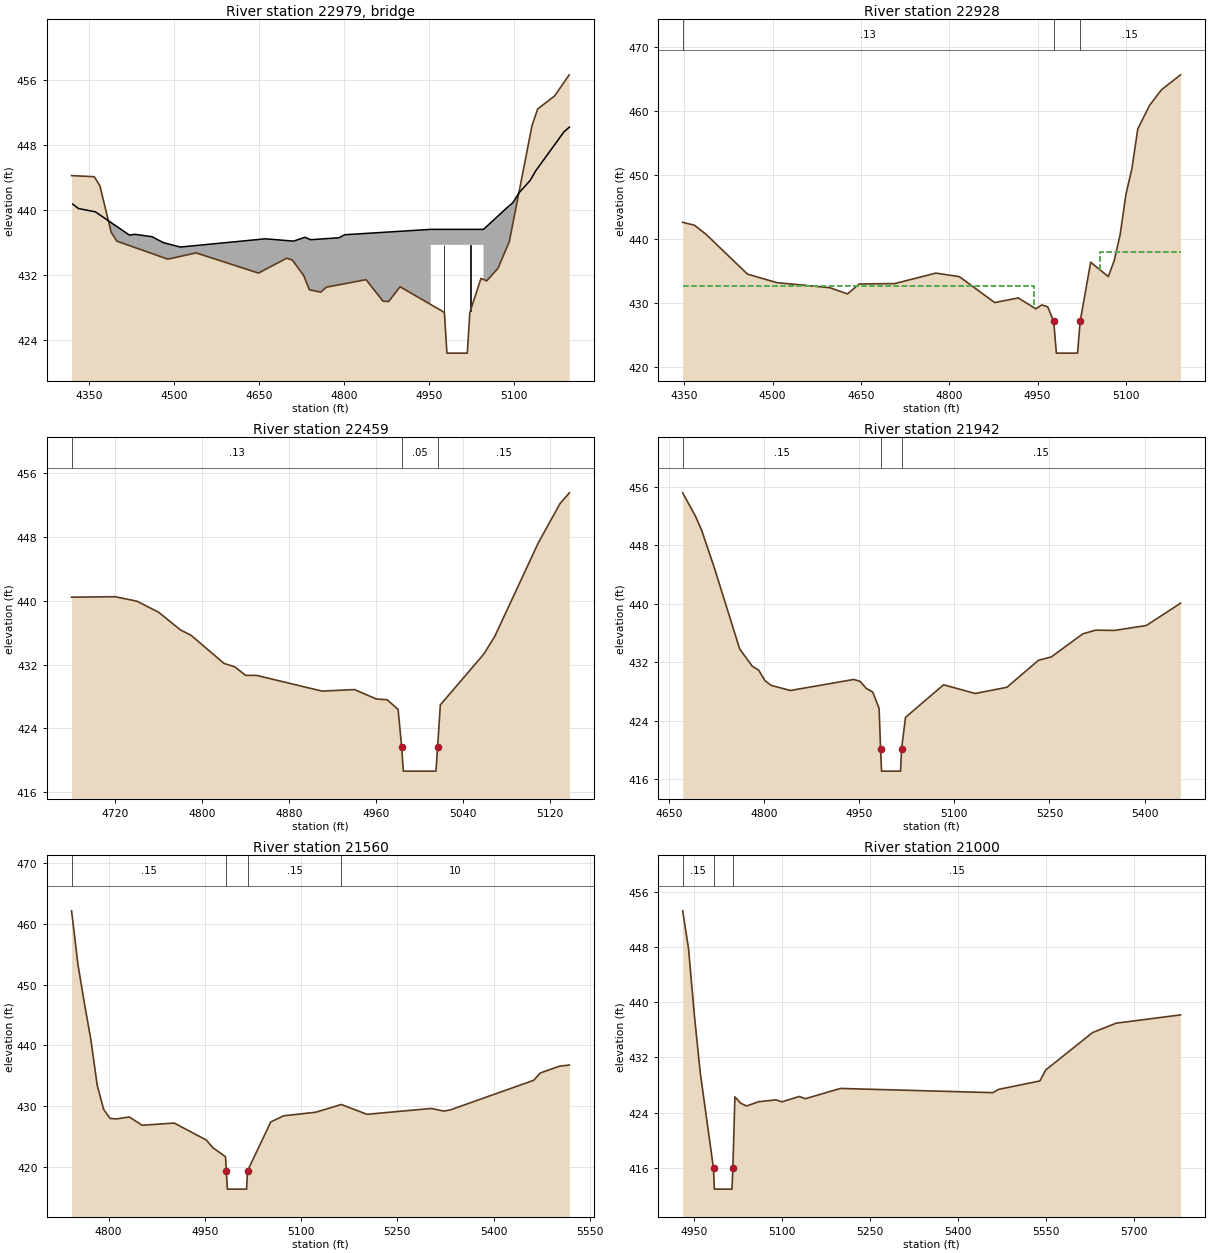
Type RM Length L Ch R = 3 ,22979   ,,,
BEGIN DESCRIPTION:
SR-1134-TOR
Structure ID: LDS_BAC_02
Approximate Survey Structure
END DESCRIPTION:
Bridge Culvert--1,0,-1,-1, 0
Deck Dist Width WeirC Skew NumUp NumDn MinLoCord MaxHiCord MaxSubmerge Is_Ogee
44.5,21,3,0, 25, 25, , , 0.95, 0, 1,1,,
  4321.3  4331.3  4361.3  4421.3  4431.3  4461.3  4481.3  4511.3  4661.3  4711.3
  4731.3  4741.3  4791.3  4801.3  4953.5  4953.5  5046.5  5046.5  5088.8  5098.8
  5108.8  5128.8  5138.8  5188.8  5198.3
   440.7  440.16  439.75   436.9  436.99   436.7  435.97  435.43  436.44  436.16
  436.63  436.33  436.57  436.94   437.6   437.6   437.6   437.6  440.31   440.9
  442.05  443.59  444.79  449.59  450.16
   402.4   402.4   402.4   402.4   402.4   402.4   402.4   402.4   402.4   402.4
   402.4   402.4   402.4   402.4   402.4   435.7   435.7   402.4   402.4   402.4
   402.4   402.4   402.4   402.4   402.4
  4321.3  4331.3  4361.3  4421.3  4431.3  4461.3  4481.3  4511.3  4661.3  4711.3
  4731.3  4741.3  4791.3  4801.3  4953.5  4953.5  5046.5  5046.5  5088.8  5098.8
  5108.8  5128.8  5138.8  5188.8  5198.3
   440.7  440.16  439.75   436.9  436.99   436.7  435.97  435.43  436.44  436.16
  436.63  436.33  436.57  436.94   437.6   437.6   437.6   437.6  440.31   440.9
  442.05  443.59  444.79  449.59  450.16
   402.4   402.4   402.4   402.4   402.4   402.4   402.4   402.4   402.4   402.4
   402.4   402.4   402.4   402.4   402.4   435.7   435.7   402.4   402.4   402.4
   402.4   402.4   402.4   402.4   402.4
Pier Skew, UpSta & Num, DnSta & Num=  ,4976.8, 2 ,4976.8, 2 , 0 , 0 , 0 ,0,0
       1       1
  427.43   435.7
       1       1
   427.3   435.7
Pier Skew, UpSta & Num, DnSta & Num=  ,5023.3, 2 ,5023.3, 2 , 0 , 0 , 0 ,0,0
       1       1
  427.59   435.7
       1       1
  427.56   435.7
BR Coef= 1 , 1 , 0 ,1.25, 0 ,,,0.8,0,2,0,
WSPro=,,,, 1 ,,,, 0 ,,,, 0 ,,,,-1 ,-1 ,-1 , 0 , 0 , 0 , 0 , 0
BC Design=,, 0 ,, 0 ,,,,,,
BC HTab HWMax=456.58

Type RM Length L Ch R = 1 ,22928   ,469,469,469
BEGIN DESCRIPTION:
SR-1134-DS
END DESCRIPTION:
XS GIS Cut Line= 3
      1710420.06       628096.78      1710042.59       628629.68
      1709919.89       628778.08
#Sta/Elev= 30
  4347.3  442.61  4367.3  442.15  4387.3  440.71  4457.3  434.51  4507.3  433.17
  4597.3  432.38  4627.3  431.41  4647.3  432.97  4707.3  433.02  4777.3  434.66
  4817.3  434.11  4877.3  430.06  4917.3  430.78  4947.3  429.08  4957.3  429.69
  4967.3  429.39  4977.5  427.15    4982  422.15    5018  422.15  5022.5  427.15
  5040.3  436.36  5070.3  434.12  5080.3  436.62  5090.3  440.65  5100.3  447.06
  5110.3  450.97  5120.3   457.2  5140.3  460.89  5160.3  463.31  5192.9  465.67
#Mann= 3 ,-1 , 0
  4347.3     .13       0  4977.5     .05       0  5022.5     .15       0
#XS Ineff= 2 , 0
       0  4943.5  432.71  5056.5       0  437.96
Permanent Ineff=
       F       F
Bank Sta=4977.5,5022.5
Exp/Cntr=0.5,0.3

Type RM Length L Ch R = 1 ,22459   ,517,517,517
BEGIN DESCRIPTION:
Barnes Creek 45.0
END DESCRIPTION:
XS GIS Cut Line= 3
      1710229.98       628050.19      1709942.23       628187.49
      1709821.03       628254.66
#Sta/Elev= 25
  4680.2  440.47  4720.2  440.53  4740.2  439.97  4760.2  438.58  4780.2  436.37
  4790.2  435.67  4820.2  432.17  4830.2  431.73  4840.2  430.66  4850.2  430.66
  4910.2  428.69  4940.2  428.88  4960.2   427.7  4970.2   427.6  4980.2  426.39
  4983.5  421.65    4985  418.65    5015  418.65  5016.5  421.65    5019  426.96
    5059  433.34    5069  435.55    5109  447.28    5129  452.22  5137.6  453.56
#Mann= 3 ,-1 , 0
  4680.2     .13       0  4983.5     .05       0  5016.5     .15       0
Bank Sta=4983.5,5016.5
Exp/Cntr=0.3,0.1

Type RM Length L Ch R = 1 ,21942   ,382,382,382
BEGIN DESCRIPTION:
Barnes Creek 44.0
END DESCRIPTION:
XS GIS Cut Line= 3
      1710114.61       627595.86      1709800.53        627702.5
      1709394.45       627905.55
#Sta/Elev= 30
  4671.1  455.18  4691.1  452.03  4701.1  450.05  4721.1  444.93  4761.1  433.82
  4781.1  431.45  4791.1  430.92  4801.1  429.47  4811.1  428.83  4841.1  428.14
  4941.1  429.65  4951.1  429.39  4961.1  428.41  4971.1  427.92  4981.1   425.7
  4983.5  420.11    4985  417.11    5015  417.11  5016.5  420.11  5022.8  424.46
  5082.8  428.92  5132.8  427.73  5182.8  428.58  5232.8  432.28  5252.8  432.73
  5302.8   435.9  5322.8  436.39  5352.8  436.36  5402.8  437.03  5456.8  440.08
#Mann= 3 ,-1 , 0
  4671.1     .15       0  4983.5     .05       0  5016.5     .15       0
Bank Sta=4983.5,5016.5
Exp/Cntr=0.3,0.1

Type RM Length L Ch R = 1 ,21560   ,560,560,560
BEGIN DESCRIPTION:
Barnes Creek 43.0
END DESCRIPTION:
XS GIS Cut Line= 3
      1709950.05       627228.67      1709714.53       627340.04
      1709274.46       627608.47
#Sta/Elev= 30
  4742.2  462.13  4752.2   453.3  4762.2  446.95  4772.2  441.01  4782.2  433.45
  4792.2  429.49  4802.2     428  4812.2  427.92  4832.2  428.24  4852.2  426.88
  4902.2  427.24  4952.2  424.46  4962.2  423.22  4982.2   421.7  4983.5  419.38
    4985  416.38    5015  416.38  5016.5  419.38  5052.7  427.43  5072.7  428.43
  5122.7  429.02  5162.7  430.29  5202.7  428.68  5302.7  429.64  5322.7  429.21
  5332.7  429.41  5462.7  434.28  5472.7  435.47  5502.7  436.59  5518.2  436.78
#Mann= 4 ,-1 , 0
  4742.2     .15       0  4983.5     .05       0  5016.5     .15       0
  5162.7      10       0
Bank Sta=4983.5,5016.5
Exp/Cntr=0.3,0.1

Type RM Length L Ch R = 1 ,21000   ,500,500,500
BEGIN DESCRIPTION:
Barnes Creek 42.0
END DESCRIPTION:
XS GIS Cut Line= 3
      1709603.16       626817.78      1709567.26       626876.82
      1709082.73       627487.95
#Sta/Elev= 24
  4930.9  453.22  4940.9  447.78  4950.9  438.09  4960.9   429.8  4983.5  415.95
    4985  412.95    5015  412.95  5016.5  415.95    5020   426.3    5030  425.38
    5040  424.98    5060  425.59    5090  425.87    5100  425.58    5130  426.36
    5140  426.03    5200  427.52    5460  426.91    5470  427.39    5540   428.6
    5550  430.19    5630  435.61    5670  436.96  5779.9  438.16
#Mann= 3 ,-1 , 0
  4930.9     .15       0  4983.5     .05       0  5016.5     .15       0
Bank Sta=4983.5,5016.5
Exp/Cntr=0.3,0.1