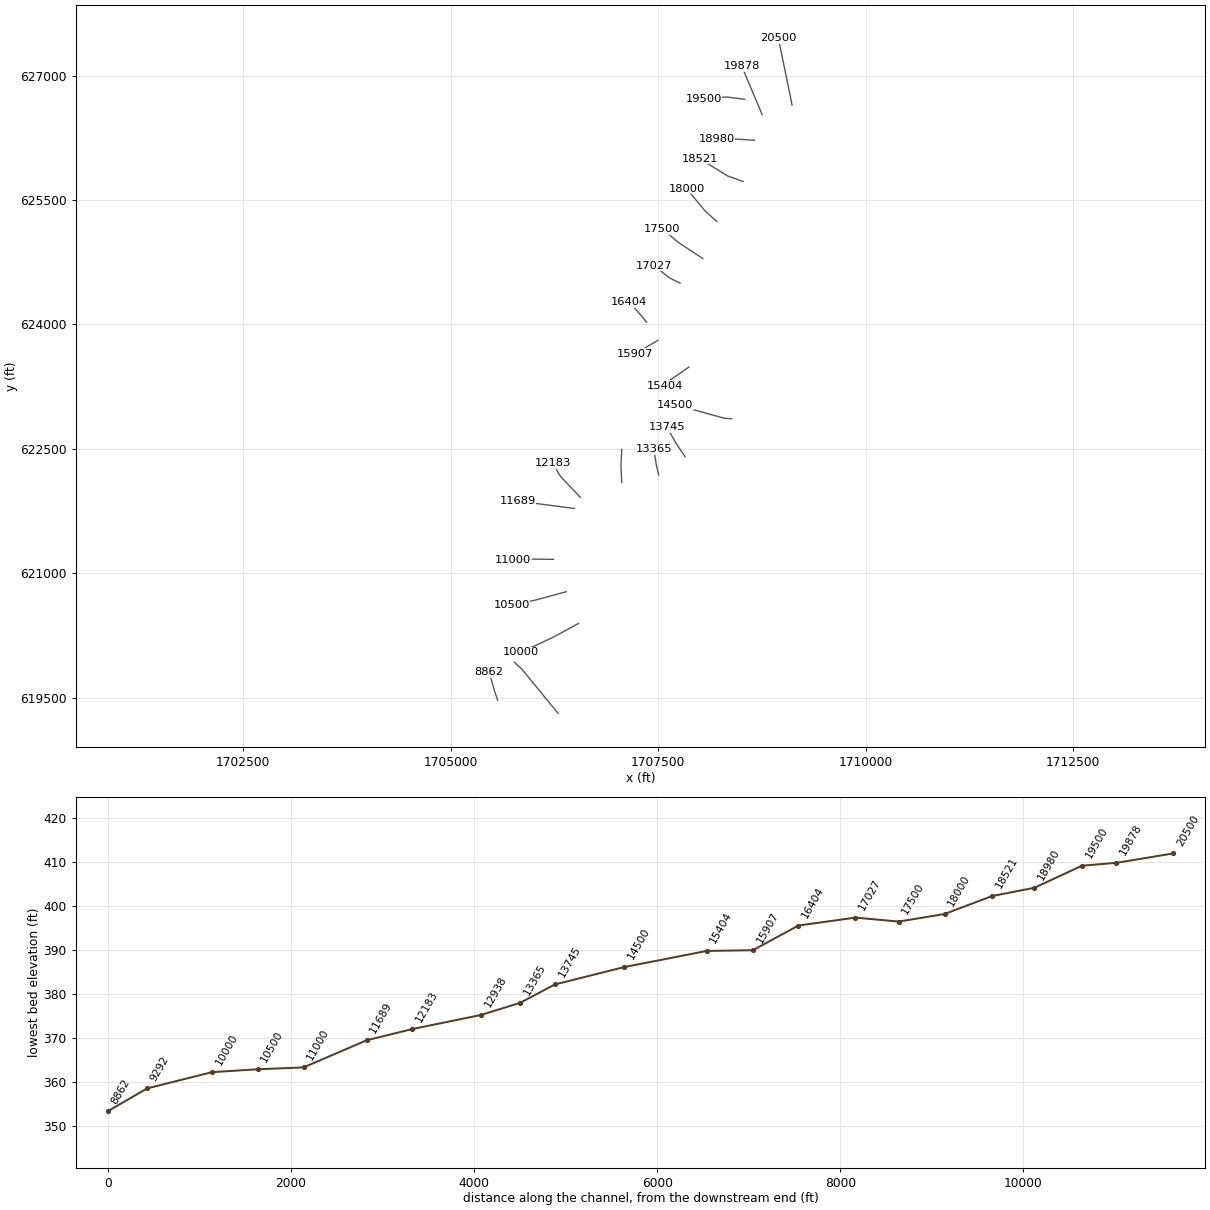
HEC-RAS study Barnes Creek.prj: Barnes Creek Limited Detail Study

--- Barnes Creek.g01 (geometry) --- (continued)

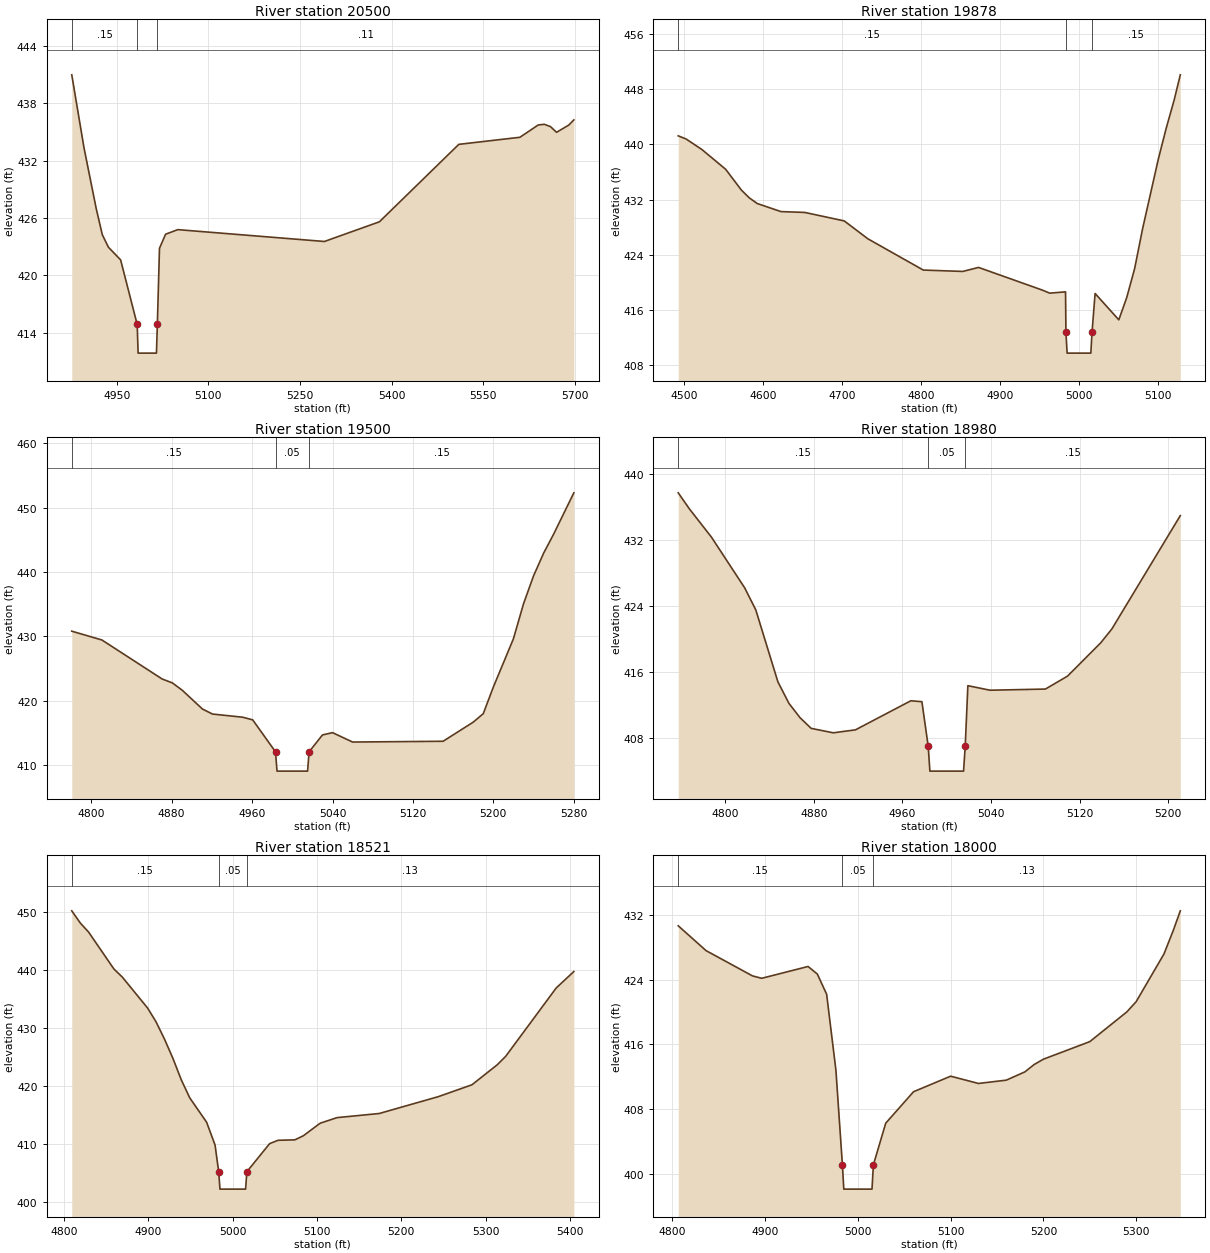
Type RM Length L Ch R = 1 ,20500   ,622,622,622
BEGIN DESCRIPTION:
Barnes Creek 41.0
END DESCRIPTION:
XS GIS Cut Line= 3
      1709113.78       626646.12      1709090.15       626767.44
      1708949.43       627451.41
#Sta/Elev= 23
  4876.4     441  4896.4  433.37  4916.4     427  4926.4  424.26  4936.4  422.95
  4956.4  421.62  4983.5  414.86    4985  411.86    5015  411.86  5016.5  414.86
    5020  422.84    5030  424.31    5050  424.79    5290  423.55    5380  425.61
    5510  433.72    5610  434.46    5640  435.75    5650  435.82    5660  435.58
    5670  434.98    5690  435.74  5698.3  436.28
#Mann= 3 ,-1 , 0
  4876.4     .15       0  4983.5     .05       0  5016.5     .11       0
Bank Sta=4983.5,5016.5
Exp/Cntr=0.3,0.1

Type RM Length L Ch R = 1 ,19878   ,378,378,378
BEGIN DESCRIPTION:
Barnes Creek 40.0
END DESCRIPTION:
XS GIS Cut Line= 3
      1708754.05        626531.1      1708556.84       626998.58
      1708509.36       627117.26
#Sta/Elev= 30
    4493  441.24    4503  440.78    4523  439.25    4553  436.39    4573  433.36
    4583  432.23    4593  431.42    4623  430.25    4653  430.13    4703   428.9
    4733   426.3    4803  421.77    4853  421.57    4873  422.15    4953  418.89
    4963  418.42    4983  418.61  4983.5  412.72    4985  409.72    5015  409.72
  5016.5  412.72  5020.4  418.37  5050.4  414.55  5060.4  417.78  5070.4  421.97
  5080.4  427.72  5100.4  437.87  5110.4  442.36  5120.4  446.43  5128.2  450.09
#Mann= 3 ,-1 , 0
    4493     .15       0  4983.5     .05       0  5016.5     .15       0
Bank Sta=4983.5,5016.5
Exp/Cntr=0.3,0.1

Type RM Length L Ch R = 1 ,19500   ,520,520,520
BEGIN DESCRIPTION:
Barnes Creek 39.0
END DESCRIPTION:
XS GIS Cut Line= 3
      1708544.09       626715.54      1708326.56       626744.07
      1708047.41       626721.03
#Sta/Elev= 26
  4780.6  430.81  4810.6  429.44  4870.6  423.37  4880.6  422.78  4890.6  421.62
  4910.6  418.71  4920.6  417.93  4950.6  417.44  4960.6  417.03  4983.3  412.06
  4984.8  409.06  5015.2  409.06  5016.7  412.06    5030  414.68    5040  415.04
    5060  413.58    5150   413.7    5180  416.67    5190  417.99    5200  422.12
    5220  429.63    5230  435.05    5240   439.4    5250  442.92    5260  445.89
  5280.1  452.31
#Mann= 3 ,-1 , 0
  4780.6     .15       0  4983.3     .05       0  5016.7     .15       0
Bank Sta=4983.3,5016.7
Exp/Cntr=0.3,0.1

Type RM Length L Ch R = 1 ,18980   ,459,459,459
BEGIN DESCRIPTION:
Barnes Creek 38.0
END DESCRIPTION:
XS GIS Cut Line= 3
      1708659.09       626222.52      1708418.06       626237.13
      1708206.24        626235.3
#Sta/Elev= 24
  4757.6  437.75  4767.6  435.82  4787.6  432.38  4817.6  426.24  4827.6  423.58
  4847.6  414.85  4857.6  412.24  4867.6  410.51  4877.6  409.22  4897.6  408.68
  4917.6  409.04  4967.6  412.56  4977.6  412.45  4983.3  407.04  4984.8  404.04
  5015.2  404.04  5016.7  407.04  5019.1  414.39  5039.1  413.84  5089.1  413.98
  5109.1  415.55  5139.1  419.59  5149.1  421.26  5210.9  434.99
#Mann= 3 ,-1 , 0
  4757.6     .15       0  4983.3     .05       0  5016.7     .15       0
Bank Sta=4983.3,5016.7
Exp/Cntr=0.3,0.1

Type RM Length L Ch R = 1 ,18521   ,521,521,521
BEGIN DESCRIPTION:
Barnes Creek 37.0
END DESCRIPTION:
XS GIS Cut Line= 3
      1708525.01         625725.      1708341.37       625789.76
       1707999.9       625999.75
#Sta/Elev= 30
    4809  450.17    4819  448.09    4829   446.5    4859  440.14    4869  438.74
    4899   433.4    4909  431.02    4919  428.05    4929  424.73    4939     421
    4949  417.91    4969  413.71    4979  409.77  4983.3  405.18  4984.8  402.18
  5015.2  402.18  5016.7  405.18  5043.7  410.02  5053.7   410.6  5073.7  410.68
  5083.7  411.38  5103.7  413.55  5123.7  414.51  5173.7  415.22  5243.7  418.12
  5283.7  420.17  5313.7  423.62  5323.7  425.07  5383.7  436.87  5404.6   439.7
#Mann= 3 ,-1 , 0
    4809     .15       0  4983.3     .05       0  5016.7     .13       0
Bank Sta=4983.3,5016.7
Exp/Cntr=0.3,0.1

Type RM Length L Ch R = 1 ,18000   ,500,500,500
BEGIN DESCRIPTION:
Barnes Creek 36.0
END DESCRIPTION:
XS GIS Cut Line= 3
      1708206.21       625241.98      1708063.29       625372.72
      1707841.06         625640.
#Sta/Elev= 26
  4806.3  430.64  4836.3  427.57  4886.3  424.45  4896.3  424.15  4946.3  425.61
  4956.3  424.67  4966.3  422.18  4976.3   412.8  4983.3  401.09  4984.8  398.09
  5015.2  398.09  5016.7  401.09    5030  406.24    5060  410.13    5100  412.05
    5130  411.15    5160  411.56    5180  412.58    5190  413.49    5200  414.15
    5250  416.32    5290     420    5300  421.26    5330  427.16    5340  430.06
  5347.6  432.49
#Mann= 3 ,-1 , 0
  4806.3     .15       0  4983.3     .05       0  5016.7     .13       0
Bank Sta=4983.3,5016.7
Exp/Cntr=0.3,0.1

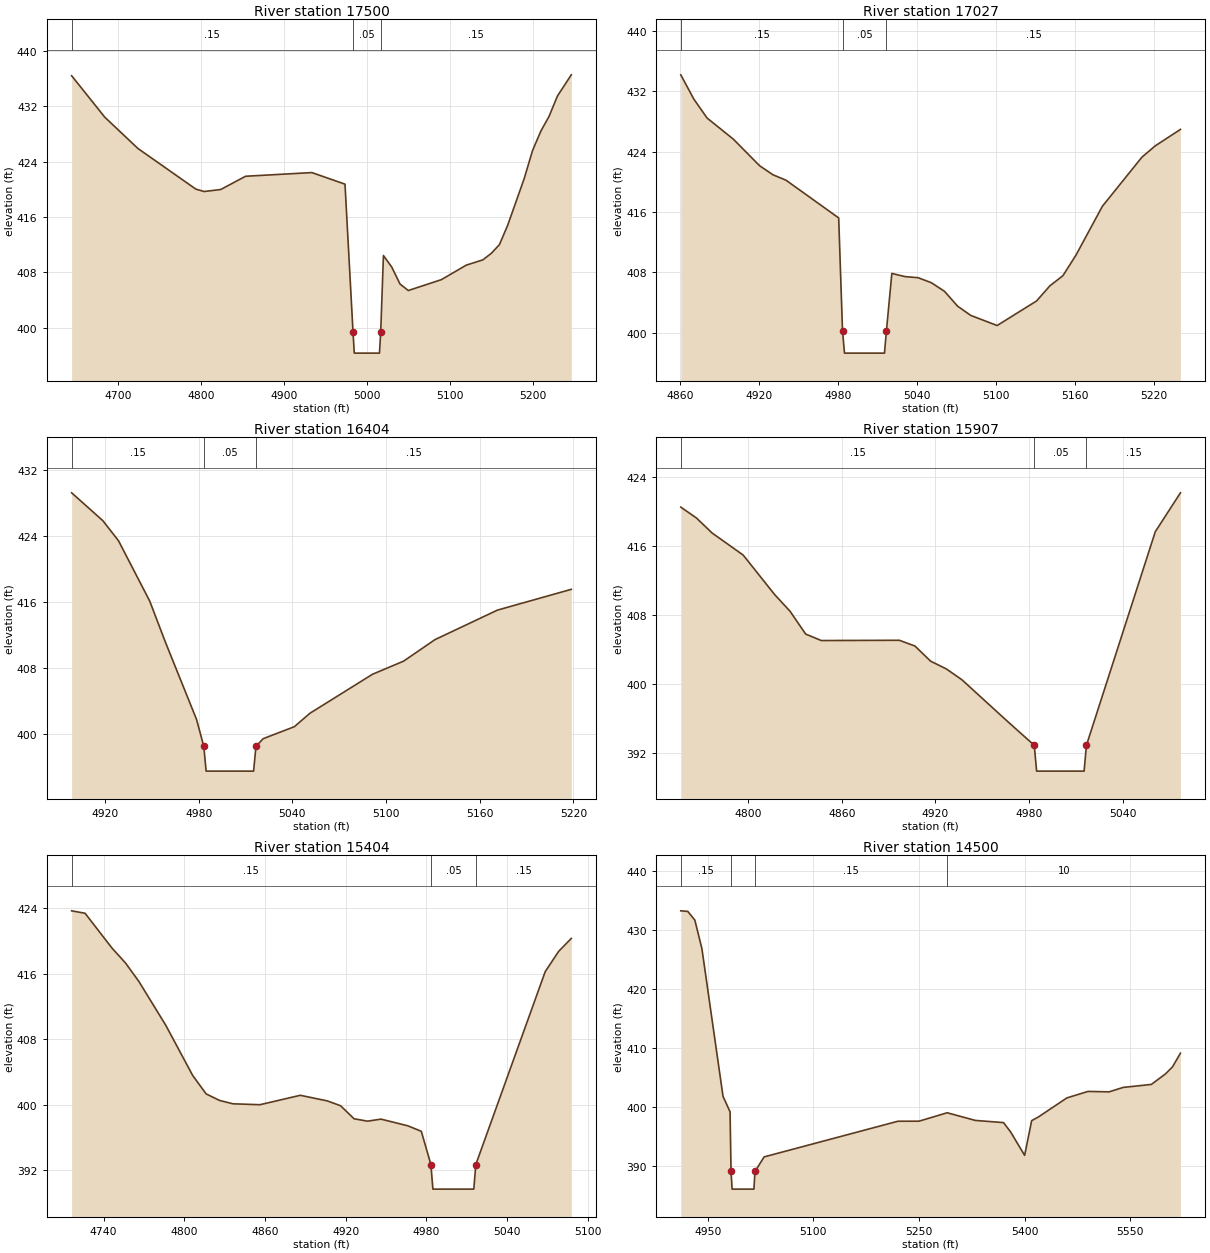
Type RM Length L Ch R = 1 ,17500   ,473,473,473
BEGIN DESCRIPTION:
Barnes Creek 35.0
END DESCRIPTION:
XS GIS Cut Line= 3
      1708038.25       624794.58      1707741.24       624991.59
      1707552.54       625150.65
#Sta/Elev= 29
  4643.6  436.38  4683.6   430.4  4723.6  425.89  4793.6  420.02  4803.6  419.68
  4823.6  419.97  4853.6  421.88  4933.6  422.41  4973.6  420.74  4983.3  399.37
  4984.8  396.37  5015.2  396.37  5016.7  399.37    5020  410.45    5030  408.79
    5040  406.34    5050   405.4    5090  406.97    5120  409.06    5140  409.82
    5150  410.74    5160  412.01    5170  414.81    5190  421.57    5200  425.59
    5210  428.38    5220  430.53    5230  433.44  5246.8  436.51
#Mann= 3 ,-1 , 0
  4643.6     .15       0  4983.3     .05       0  5016.7     .15       0
Bank Sta=4983.3,5016.7
Exp/Cntr=0.3,0.1

Type RM Length L Ch R = 1 ,17027   ,623,623,623
BEGIN DESCRIPTION:
Barnes Creek 34.0
END DESCRIPTION:
XS GIS Cut Line= 3
      1707764.34       624498.77      1707638.35       624560.85
      1707450.29       624708.75
#Sta/Elev= 28
  4860.4  434.18  4870.4  430.94  4880.4  428.45  4900.4  425.64  4920.4  422.11
  4930.4  420.93  4940.4   420.2  4980.4   415.2  4983.3  400.27  4984.8  397.27
  5015.2  397.27  5016.7  400.27  5020.8  407.84  5030.8  407.42  5040.8  407.27
  5050.8  406.61  5060.8  405.47  5070.8  403.49  5080.8  402.27  5100.8  400.93
  5130.8  404.19  5140.8  406.18  5150.8  407.54  5160.8  410.29  5180.8  416.75
  5210.8  423.25  5220.8  424.74  5240.1  426.94
#Mann= 3 ,-1 , 0
  4860.4     .15       0  4983.3     .05       0  5016.7     .15       0
Bank Sta=4983.3,5016.7
Exp/Cntr=0.3,0.1

Type RM Length L Ch R = 1 ,16404   ,497,497,497
BEGIN DESCRIPTION:
Barnes Creek 33.0
END DESCRIPTION:
XS GIS Cut Line= 3
      1707360.79       624025.85      1707296.89       624106.18
      1707152.66       624268.66
#Sta/Elev= 18
  4898.7  429.21  4918.7  425.83  4928.7   423.4  4948.7  416.08  4958.7  411.12
  4978.7  401.72  4983.3  398.47  4984.8  395.47  5015.2  395.47  5016.7  398.47
  5021.3   399.4  5041.3  400.86  5051.3  402.49  5091.3  407.21  5111.3  408.81
  5131.3  411.41  5171.3  414.99  5218.6  417.51
#Mann= 3 ,-1 , 0
  4898.7     .15       0  4983.3     .05       0  5016.7     .15       0
Bank Sta=4983.3,5016.7
Exp/Cntr=0.3,0.1

Type RM Length L Ch R = 1 ,15907   ,503,503,503
BEGIN DESCRIPTION:
Barnes Creek 32.0
END DESCRIPTION:
XS GIS Cut Line= 3
      1707495.88       623808.51      1707285.93       623684.37
      1707220.21       623646.03
#Sta/Elev= 20
  4756.9  420.55  4766.9  419.29  4776.9  417.55  4796.9  414.97  4816.9  410.41
  4826.9  408.44  4836.9  405.79  4846.9  405.04  4896.9  405.07  4906.9   404.4
  4916.9  402.64  4926.9  401.75  4936.9  400.49  4966.9  395.52  4983.3  392.86
  4984.8  389.86  5015.2  389.86  5016.7  392.86  5060.8  417.69  5076.9  422.21
#Mann= 3 ,-1 , 0
  4756.9     .15       0  4983.3     .05       0  5016.7     .15       0
Bank Sta=4983.3,5016.7
Exp/Cntr=0.3,0.1

Type RM Length L Ch R = 1 ,15404   ,904,904,904
BEGIN DESCRIPTION:
Barnes Creek 31.0
END DESCRIPTION:
XS GIS Cut Line= 3
      1707872.08       623487.16      1707640.18       623326.47
      1707581.72       623258.88
#Sta/Elev= 26
  4716.2  423.69  4726.2  423.39  4746.2  419.14  4756.2  417.33  4766.2  415.06
  4786.2  409.71  4806.2  403.58  4816.2  401.33  4826.2  400.53  4836.2  400.12
  4856.2  400.01  4886.2  401.16  4906.2  400.48  4916.2  399.88  4926.2  398.29
  4936.2     398  4946.2  398.25  4966.2  397.43  4976.2  396.76  4983.3   392.7
  4984.8   389.7  5015.2   389.7  5016.7   392.7  5068.3  416.26  5078.3  418.74
  5087.7  420.32
#Mann= 3 ,-1 , 0
  4716.2     .15       0  4983.3     .05       0  5016.7     .15       0
Bank Sta=4983.3,5016.7
Exp/Cntr=0.3,0.1

Type RM Length L Ch R = 1 ,14500   ,755,755,755
BEGIN DESCRIPTION:
Barnes Creek 29.0
END DESCRIPTION:
XS GIS Cut Line= 3
      1708387.29       622862.89      1708299.08       622868.69
       1707700.2       623034.08
#Sta/Elev= 28
  4911.6  433.25  4921.6  433.15  4931.6  431.67  4941.6  426.84  4971.6  401.77
  4981.6  399.14    4983  389.02  4984.5  386.02  5015.5  386.02    5017  389.02
    5030  391.49    5220  397.54    5250  397.55    5290  398.98    5330  397.68
    5370  397.31    5380  395.75    5400  391.75    5410  397.64    5420   398.3
    5460   401.5    5490   402.6    5520  402.53    5540  403.28    5580  403.79
    5600  405.57    5610  406.76  5621.3  409.09
#Mann= 4 ,-1 , 0
  4911.6     .15       0    4983     .05       0    5017     .15       0
    5290      10       0
Bank Sta=4983,5017
Exp/Cntr=0.3,0.1

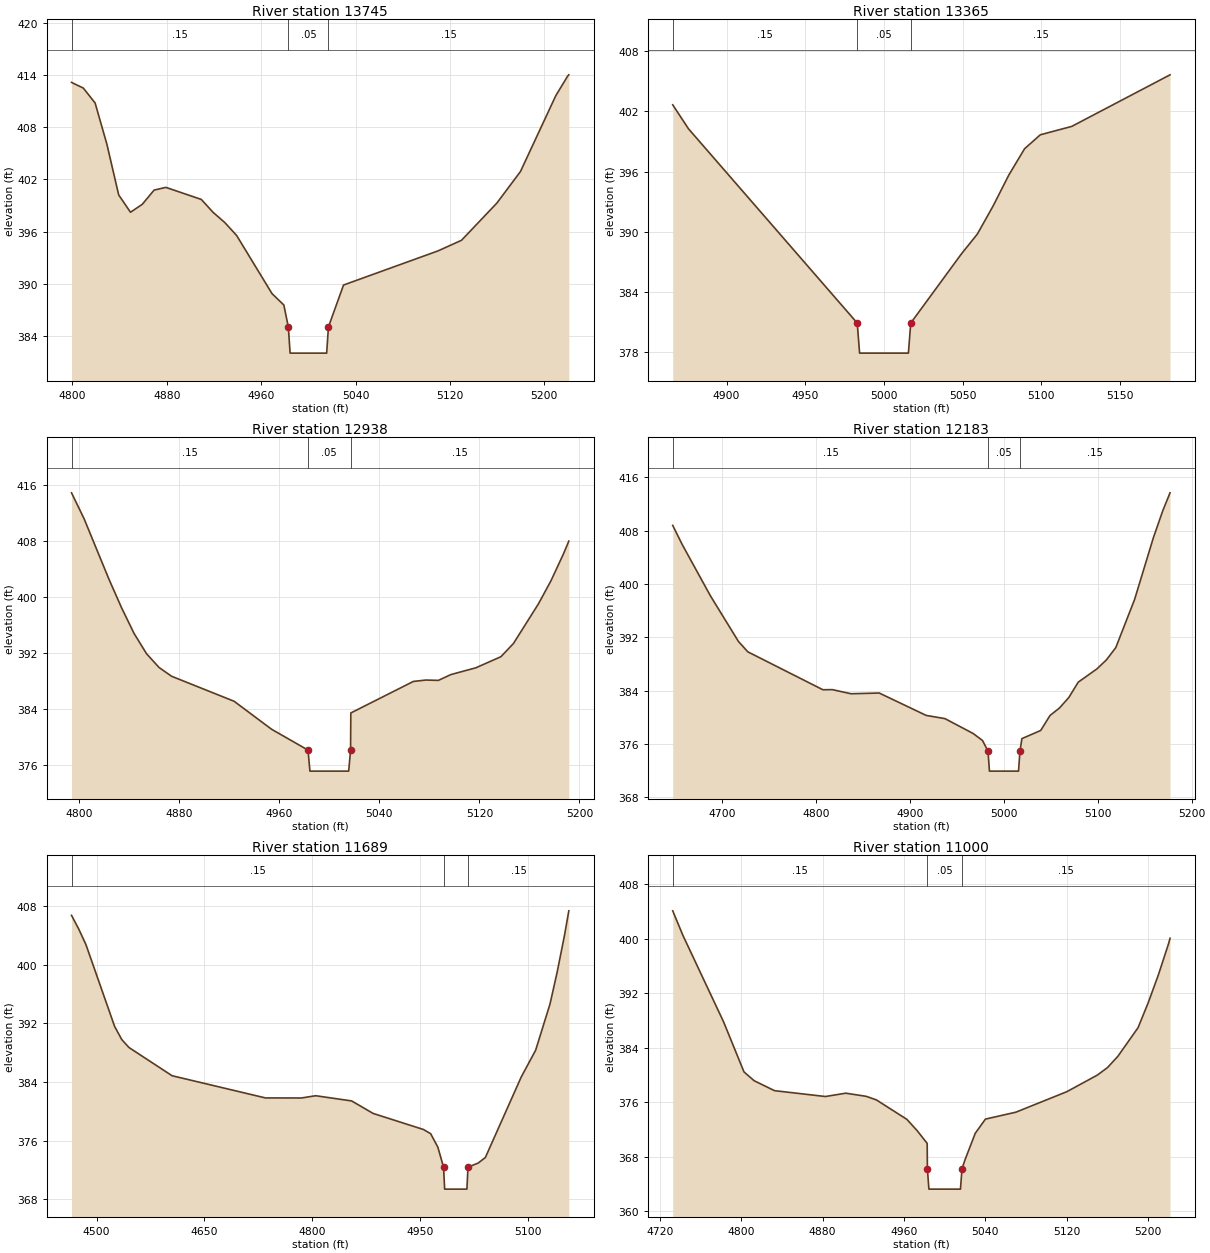
Type RM Length L Ch R = 1 ,13745   ,380,380,380
BEGIN DESCRIPTION:
Barnes Creek 28.0
END DESCRIPTION:
XS GIS Cut Line= 3
      1707825.74       622404.11      1707718.47        622561.6
      1707604.33       622762.49
#Sta/Elev= 27
  4799.2  413.13  4809.2  412.48  4819.2  410.77  4829.2  406.03  4839.2  400.22
  4849.2  398.24  4859.2  399.15  4869.2  400.78  4879.2  401.09  4909.2  399.71
  4919.2  398.23  4929.2  397.05  4939.2  395.57  4969.2   388.9  4979.2   387.6
    4983  385.08  4984.5  382.08  5015.5  382.08    5017  385.08  5029.8  389.89
  5109.8   393.8  5129.8  395.02  5159.8  399.29  5179.8  402.91  5209.8  411.62
  5219.8  413.85  5220.8     414
#Mann= 3 ,-1 , 0
  4799.2     .15       0    4983     .05       0    5017     .15       0
Bank Sta=4983,5017
Exp/Cntr=0.3,0.1

Type RM Length L Ch R = 1 ,13365   ,427,427,427
BEGIN DESCRIPTION:
Barnes Creek 27.0
END DESCRIPTION:
XS GIS Cut Line= 3
       1707506.2       622184.95      1707476.52       622315.09
      1707449.13       622495.44
#Sta/Elev= 14
  4865.8  402.66  4875.8  400.27    4983   380.9  4984.5   377.9  5015.5   377.9
    5017   380.9  5049.3  387.82  5059.3  389.77  5069.3  392.57  5079.3  395.66
  5089.3  398.28  5099.3  399.67  5119.3  400.51  5181.7  405.65
#Mann= 3 ,-1 , 0
  4865.8     .15       0    4983     .05       0    5017     .15       0
Bank Sta=4983,5017
Exp/Cntr=0.3,0.1

Type RM Length L Ch R = 1 ,12938   ,755,755,755
BEGIN DESCRIPTION:
Barnes Creek 26.0
END DESCRIPTION:
XS GIS Cut Line= 3
      1707061.11       622095.98      1707051.98       622299.11
      1707061.11       622493.16
#Sta/Elev= 26
  4793.9  414.87  4803.9  411.19  4823.9  402.51  4833.9  398.47  4843.9   394.8
  4853.9   391.9  4863.9  389.94  4873.9  388.69  4923.9  385.12  4953.9  381.12
    4983  378.15  4984.5  375.15  5015.5  375.15    5017  378.15  5017.2  383.45
  5067.2  387.95  5077.2  388.15  5087.2   388.1  5097.2  388.93  5117.2   389.9
  5137.2  391.48  5147.2  393.36  5167.2  399.02  5177.2  402.31  5187.2  406.15
  5191.5  407.98
#Mann= 3 ,-1 , 0
  4793.9     .15       0    4983     .05       0    5017     .15       0
Bank Sta=4983,5017
Exp/Cntr=0.3,0.1

Type RM Length L Ch R = 1 ,12183   ,494,494,494
BEGIN DESCRIPTION:
Barnes Creek 25.0
END DESCRIPTION:
XS GIS Cut Line= 3
      1706561.27       621915.62      1706319.29       622171.29
      1706232.57       622326.48
#Sta/Elev= 30
  4647.1  408.79  4657.1  405.95  4687.1  398.26  4717.1  391.38  4727.1  389.82
  4807.1  384.13  4817.1  384.15  4837.1  383.53  4867.1  383.64  4917.1  380.28
  4937.1   379.8  4967.1  377.57  4977.1  376.52    4983  374.92  4984.5  371.92
  5015.5  371.92    5017  374.92  5019.1   376.8  5039.1  378.02  5049.1  380.28
  5059.1  381.39  5069.1  382.97  5079.1  385.27  5099.1  387.27  5109.1  388.61
  5119.1  390.45  5139.1  397.66  5159.1  406.92  5169.1  410.97  5176.9  413.68
#Mann= 3 ,-1 , 0
  4647.1     .15       0    4983     .05       0    5017     .15       0
Bank Sta=4983,5017
Exp/Cntr=0.3,0.1

Type RM Length L Ch R = 1 ,11689   ,689,689,689
BEGIN DESCRIPTION:
Barnes Creek 24.0
END DESCRIPTION:
XS GIS Cut Line= 3
      1706490.43       621780.99      1705958.65       621849.46
      1705803.49       621867.71
#Sta/Elev= 27
    4465  406.76    4475   404.9    4485  402.79    4525   391.6    4535   389.8
    4545  388.72    4605  384.87    4735  381.84    4785  381.83    4805  382.14
    4855  381.43    4885  379.72    4955  377.53    4965  376.96    4975  375.13
    4983  372.39  4984.5  369.39  5015.5  369.39    5017  372.39  5031.2  372.95
  5041.2  373.71  5091.2  384.71  5111.2  388.35  5131.2  394.66  5141.2  399.03
  5151.2  403.94  5157.4  407.38
#Mann= 3 ,-1 , 0
    4465     .15       0    4983     .05       0    5017     .15       0
Bank Sta=4983,5017
Exp/Cntr=0.3,0.1

Type RM Length L Ch R = 1 ,11000   ,500,500,500
BEGIN DESCRIPTION:
Barnes Creek 22.0
END DESCRIPTION:
XS GIS Cut Line= 3
      1706239.44       621166.99      1705972.25       621169.99
      1705750.92        621164.7
#Sta/Elev= 30
  4732.8  404.13  4742.8  400.52  4782.8   387.8  4802.8  380.46  4812.8  379.16
  4832.8   377.7  4882.8  376.84  4902.8  377.33  4922.8  376.87  4932.8  376.35
  4962.8  373.49  4972.8  371.85  4982.8  369.95    4983  366.23  4984.5  363.23
  5015.5  363.23    5017  366.23    5020  367.55    5030  371.43    5040  373.52
    5070  374.54    5120  377.55    5150  379.99    5160   381.1    5170  382.72
    5190  386.96    5200  390.64    5210  394.74    5220  399.32  5221.4   400.1
#Mann= 3 ,-1 , 0
  4732.8     .15       0    4983     .05       0    5017     .15       0
Bank Sta=4983,5017
Exp/Cntr=0.3,0.1

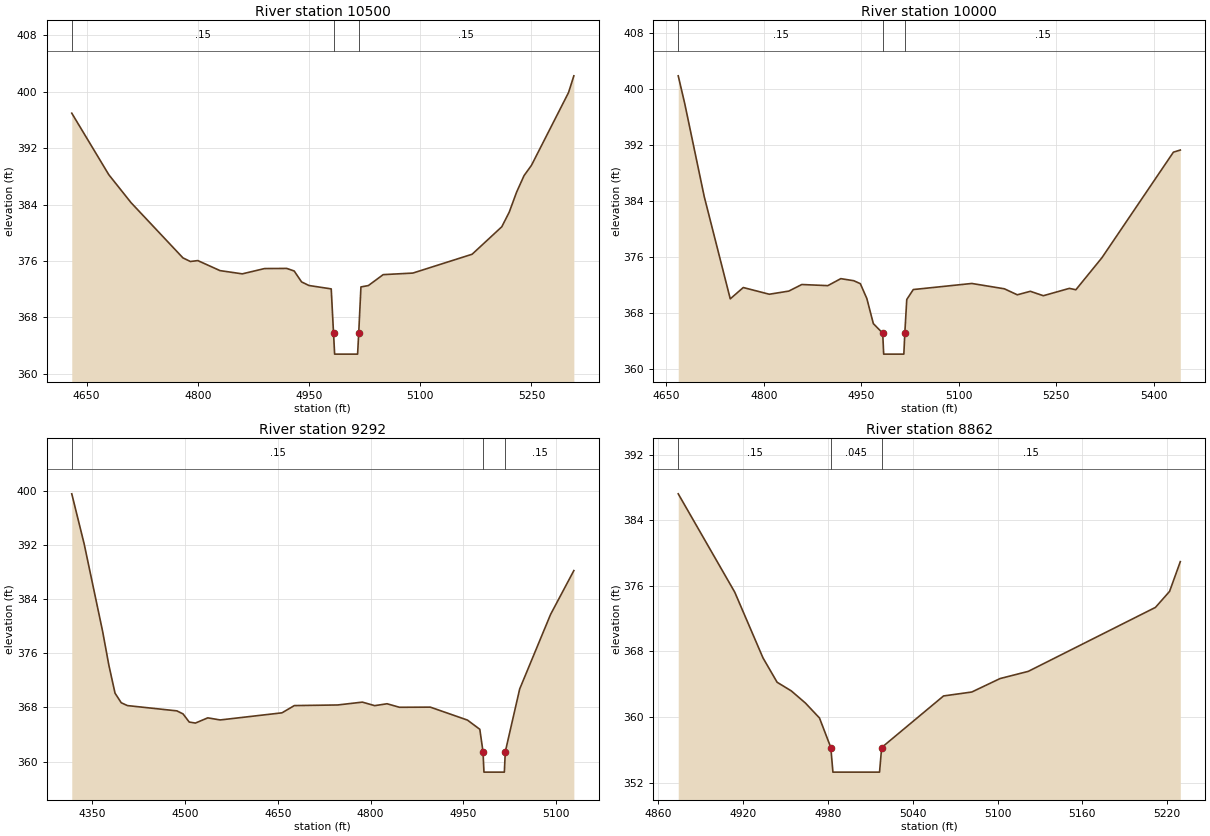
Type RM Length L Ch R = 1 ,10500   ,500,500,500
BEGIN DESCRIPTION:
Barnes Creek 21.0
END DESCRIPTION:
XS GIS Cut Line= 3
       1706392.3       620776.67      1706035.37       620678.81
      1705734.96       620614.62
#Sta/Elev= 30
  4629.9  396.94  4679.9  388.22  4709.9  384.26  4779.9  376.44  4789.9  375.93
  4799.9  376.06  4829.9  374.64  4859.9  374.18  4889.9  374.93  4919.9  374.95
  4929.9  374.59  4939.9  373.04  4949.9  372.53  4979.9  372.05    4983  365.81
  4984.5  362.81  5015.5  362.81    5017  365.81    5020  372.33    5030  372.52
    5050  374.07    5090  374.29    5170  376.96    5210  380.85    5220  382.91
    5230  385.76    5240  388.09    5250  389.55    5300  399.85  5307.2  402.23
#Mann= 3 ,-1 , 0
  4629.9     .15       0    4983    .045       0    5017     .15       0
Bank Sta=4983,5017
Exp/Cntr=0.3,0.1

Type RM Length L Ch R = 1 ,10000   ,708,708,708
BEGIN DESCRIPTION:
Barnes Creek 20.0
END DESCRIPTION:
XS GIS Cut Line= 3
      1706538.37       620393.19      1706247.91       620233.63
      1705849.13       620046.29
#Sta/Elev= 30
  4668.6  401.93  4678.6  397.96  4708.6  384.66  4748.6  370.05  4768.6  371.67
  4808.6  370.71  4838.6  371.16  4858.6   372.1  4898.6  371.94  4918.6  372.94
  4938.6  372.64  4948.6  372.22  4958.6   370.1  4968.6  366.51    4983  365.15
  4984.5  362.15  5015.5  362.15    5017  365.15    5020  369.96    5030  371.38
    5120  372.25    5170  371.49    5190  370.63    5210  371.13    5230   370.5
    5270  371.55    5280  371.35    5320  375.92    5430  391.02  5440.6  391.32
#Mann= 3 ,-1 , 0
  4668.6     .15       0    4983    .045       0    5017     .15       0
Bank Sta=4983,5017
Exp/Cntr=0.3,0.1

Type RM Length L Ch R = 1 ,9292    ,430,430,430
BEGIN DESCRIPTION:
Barnes Creek 19.0
END DESCRIPTION:
XS GIS Cut Line= 3
      1706294.21       619308.99      1705860.51       619838.57
      1705766.93        619925.3
#Sta/Elev= 30
  4316.8  399.53  4336.8  392.16  4366.8  379.19  4376.8  374.24  4386.8  370.11
  4396.8   368.7  4406.8  368.28  4486.8   367.5  4496.8  367.05  4506.8  365.85
  4516.8   365.7  4536.8  366.47  4556.8  366.16  4656.8  367.21  4676.8  368.28
  4746.8  368.37  4786.8  368.79  4806.8  368.27  4826.8  368.55  4846.8  368.03
  4896.8  368.05  4956.8  366.14  4976.8  364.78    4982  361.46  4983.5  358.46
  5016.5  358.46    5018  361.46  5041.3  370.73  5091.3  381.74  5128.9   388.2
#Mann= 3 ,-1 , 0
  4316.8     .15       0    4982    .045       0    5018     .15       0
Bank Sta=4982,5018
Exp/Cntr=0.3,0.1

Type RM Length L Ch R = 1 ,8862    ,442,442,442
BEGIN DESCRIPTION:
Barnes Creek 18.0
END DESCRIPTION:
XS GIS Cut Line= 3
      1705566.07       619466.49      1705524.98       619587.49
      1705463.35        619806.6
#Sta/Elev= 18
    4874  387.21    4914  375.22    4934   367.2    4944  364.23    4954  363.18
    4964   361.7    4974  359.87    4982  356.27  4983.5  353.27  5016.5  353.27
    5018  356.27  5061.8  362.56  5081.8  363.04  5101.8  364.68  5121.8  365.56
  5211.8  373.36  5221.8  375.31  5229.4  378.94
#Mann= 3 ,-1 , 0
    4874     .15       0    4982    .045       0    5018     .15       0
Bank Sta=4982,5018
Exp/Cntr=0.3,0.1