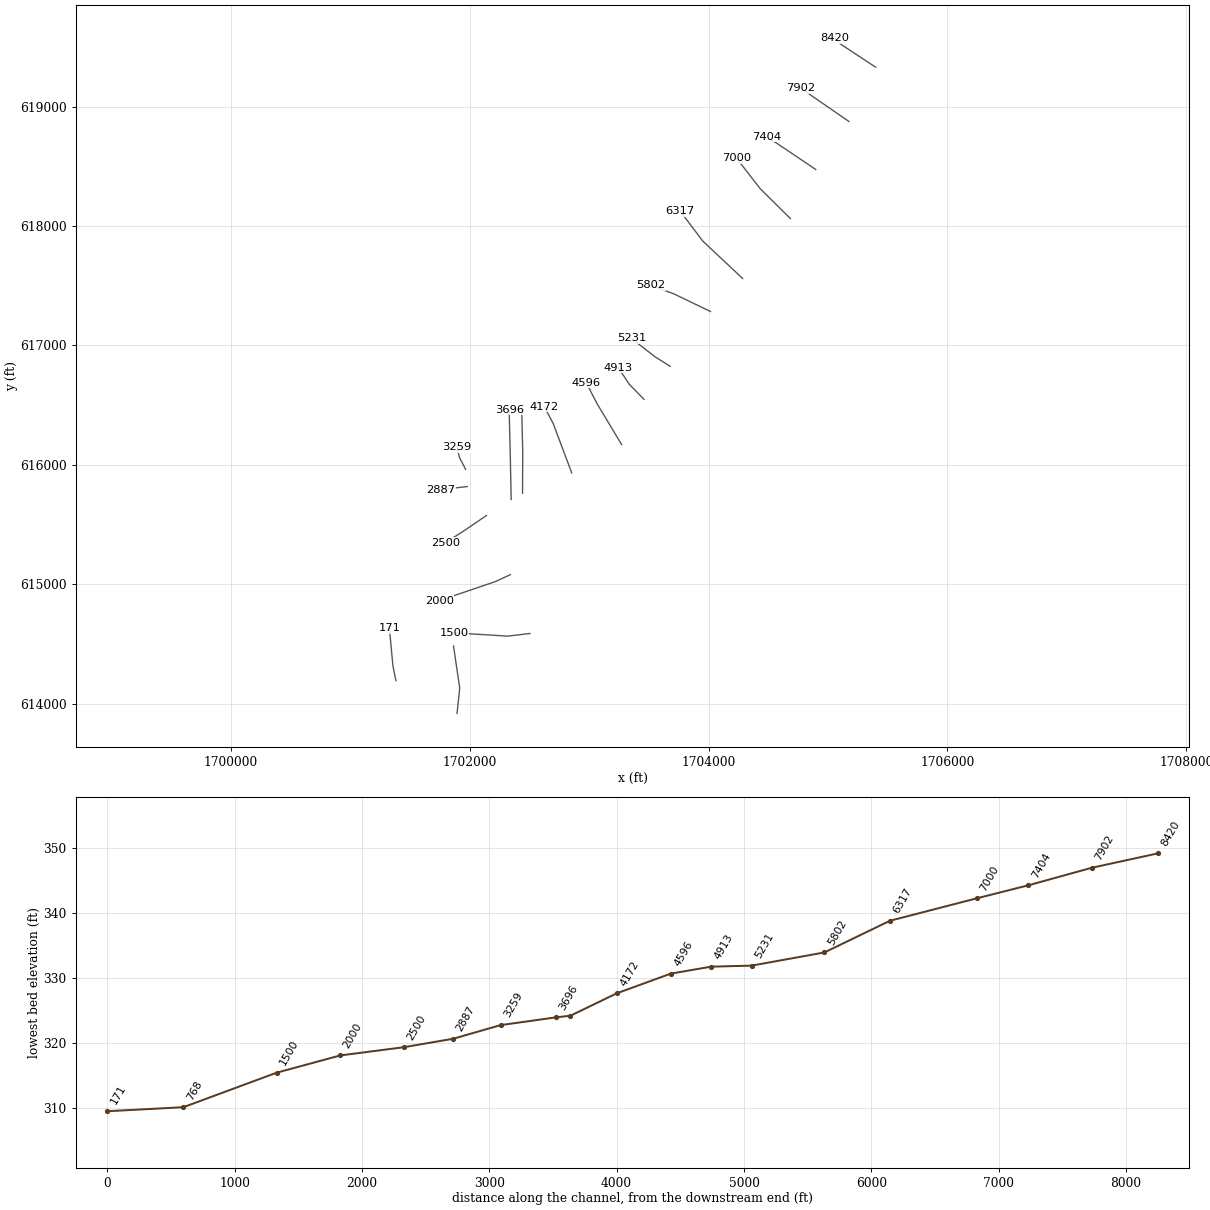
HEC-RAS study Barnes Creek.prj: Barnes Creek Limited Detail Study

--- Barnes Creek.g01 (geometry) --- (continued)

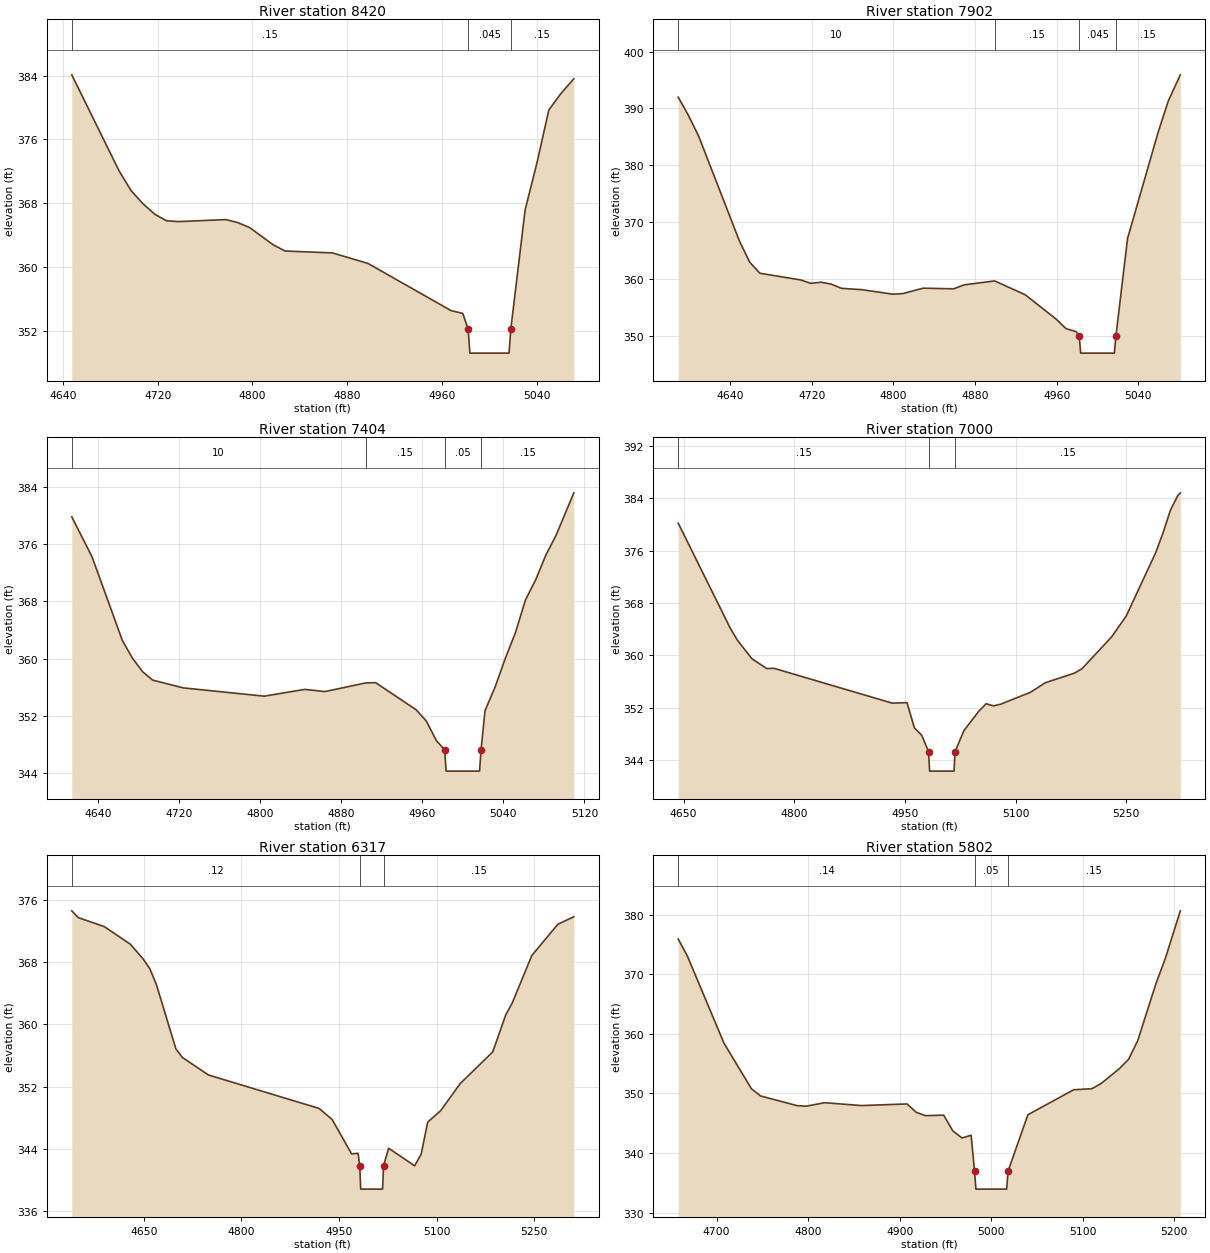
Type RM Length L Ch R = 1 ,8420    ,518,518,518
BEGIN DESCRIPTION:
Barnes Creek 17.0
END DESCRIPTION:
XS GIS Cut Line= 3
       1705399.4       619329.59      1705104.99       619523.58
      1705052.47       619571.54
#Sta/Elev= 25
  4647.5   384.1  4687.5  372.03  4697.5  369.59  4707.5  367.94  4717.5  366.62
  4727.5  365.79  4737.5  365.69  4777.5  365.94  4787.5  365.57  4797.5  364.95
  4817.5  362.78  4827.5     362  4867.5  361.76  4897.5  360.44  4967.5  354.53
  4977.5  354.17    4982  352.19  4983.5  349.19  5016.5  349.19    5018  352.19
  5030.1  367.16  5040.1  373.08  5050.1  379.69  5060.1  381.72  5071.2  383.61
#Mann= 3 ,-1 , 0
  4647.5     .15       0    4982    .045       0    5018     .15       0
Bank Sta=4982,5018
Exp/Cntr=0.3,0.1

Type RM Length L Ch R = 1 ,7902    ,498,498,498
BEGIN DESCRIPTION:
Barnes Creek 16.0
END DESCRIPTION:
XS GIS Cut Line= 3
      1705175.78       618875.32      1704837.94       619108.16
      1704771.77       619156.08
#Sta/Elev= 30
  4589.1  391.98  4599.1  388.79  4609.1  385.15  4649.1  366.68  4659.1  362.98
  4669.1  361.03  4709.1  359.85  4719.1  359.25  4729.1  359.45  4739.1  359.11
  4749.1  358.37  4769.1  358.14  4799.1  357.35  4809.1  357.45  4829.1   358.4
  4859.1  358.29  4869.1  358.98  4899.1  359.68  4929.1  357.25  4959.1  353.01
  4969.1  351.29  4979.1  350.75    4982  349.98  4983.5  346.98  5016.5  346.98
    5018  349.98  5029.4  367.14  5059.4  385.84  5069.4  391.35  5081.1  395.92
#Mann= 4 ,-1 , 0
  4589.1      10       0  4899.1     .15       0    4982    .045       0
    5018     .15       0
Bank Sta=4982,5018
Exp/Cntr=0.3,0.1

Type RM Length L Ch R = 1 ,7404    ,404,404,404
BEGIN DESCRIPTION:
Barnes Creek 15.0
END DESCRIPTION:
XS GIS Cut Line= 3
      1704897.25       618473.65      1704575.45       618690.46
      1704484.14       618747.53
#Sta/Elev= 28
  4613.9  379.84  4633.9  374.25  4663.9  362.53  4673.9  360.05  4683.9  358.17
  4693.9     357  4723.9  355.92  4803.9  354.76  4843.9  355.71  4863.9   355.4
  4903.9  356.61  4913.9  356.65  4953.9  352.86  4963.9  351.29  4973.9  348.54
    4982  347.28  4983.5  344.28  5016.5  344.28    5018  347.28  5021.9  352.73
  5031.9  356.06  5041.9  360.03  5051.9  363.63  5061.9  368.24  5071.9  371.02
  5081.9  374.47  5091.9   377.2  5109.6  383.19
#Mann= 4 ,-1 , 0
  4613.9      10       0  4903.9     .15       0    4982     .05       0
    5018     .15       0
Bank Sta=4982,5018
Exp/Cntr=0.3,0.1

Type RM Length L Ch R = 1 ,7000    ,683,683,683
BEGIN DESCRIPTION:
Barnes Creek 14.0
END DESCRIPTION:
XS GIS Cut Line= 3
      1704685.01       618062.77      1704431.31       618314.23
      1704233.07       618569.49
#Sta/Elev= 30
  4642.8  380.21  4712.8  364.26  4722.8  362.34  4742.8  359.46  4762.8  357.97
  4772.8     358  4932.8  352.68  4952.8  352.76  4962.8  348.91  4972.8  347.76
    4982  345.28  4983.5  342.28  5016.5  342.28    5018  345.28    5030  348.48
    5050  351.43    5060  352.59    5070  352.26    5080  352.53    5120  354.33
    5140  355.79    5180  357.28    5190  357.95    5230   362.8    5250  366.02
    5290  375.74    5300  378.79    5310  382.26    5320  384.47  5323.2  384.85
#Mann= 3 ,-1 , 0
  4642.8     .15       0    4982     .05       0    5018     .15       0
Bank Sta=4982,5018
Exp/Cntr=0.3,0.1

Type RM Length L Ch R = 1 ,6317    ,515,515,515
BEGIN DESCRIPTION:
Barnes Creek 13.0
END DESCRIPTION:
XS GIS Cut Line= 3
      1704285.54       617560.65      1703952.33       617873.32
      1703762.86       618124.42
#Sta/Elev= 30
  4539.2  374.61  4549.2  373.74  4589.2  372.58  4629.2  370.32  4649.2  368.39
  4659.2  367.16  4669.2  365.14  4699.2  356.86  4709.2  355.75  4749.2   353.5
  4919.2   349.2  4939.2  347.79  4969.2  343.35  4979.2  343.43  4981.7  341.82
  4983.2  338.82  5016.8  338.82  5018.3  341.82  5026.1  344.08  5066.1  341.82
  5076.1  343.32  5086.1  347.44  5106.1  348.91  5136.1   352.4  5186.1  356.47
  5206.1  361.24  5216.1  362.77  5246.1  368.86  5286.1  372.88  5310.7  373.85
#Mann= 3 ,-1 , 0
  4539.2     .12       0  4981.7     .05       0  5018.3     .15       0
Bank Sta=4981.7,5018.3
Exp/Cntr=0.3,0.1

Type RM Length L Ch R = 1 ,5802    ,571,571,571
BEGIN DESCRIPTION:
Barnes Creek 12.0
END DESCRIPTION:
XS GIS Cut Line= 3
      1704016.22       617284.44       1703708.1        617432.8
      1703514.08       617503.56
#Sta/Elev= 30
    4658   375.9    4668  373.04    4708  358.42    4738  350.77    4748  349.57
    4788  347.94    4798  347.86    4818  348.44    4858  347.96    4908  348.23
    4918  346.83    4928  346.27    4948  346.35    4958  343.71    4968  342.52
    4978  342.98  4981.7  336.94  4983.2  333.94  5016.8  333.94  5018.3  336.94
    5040  346.42    5090  350.61    5110  350.79    5120  351.66    5140  354.16
    5150  355.72    5160  358.86    5180  368.47    5190  372.58  5206.5  380.63
#Mann= 3 ,-1 , 0
    4658     .14       0  4981.7     .05       0  5018.3     .15       0
Bank Sta=4981.7,5018.3
Exp/Cntr=0.3,0.1

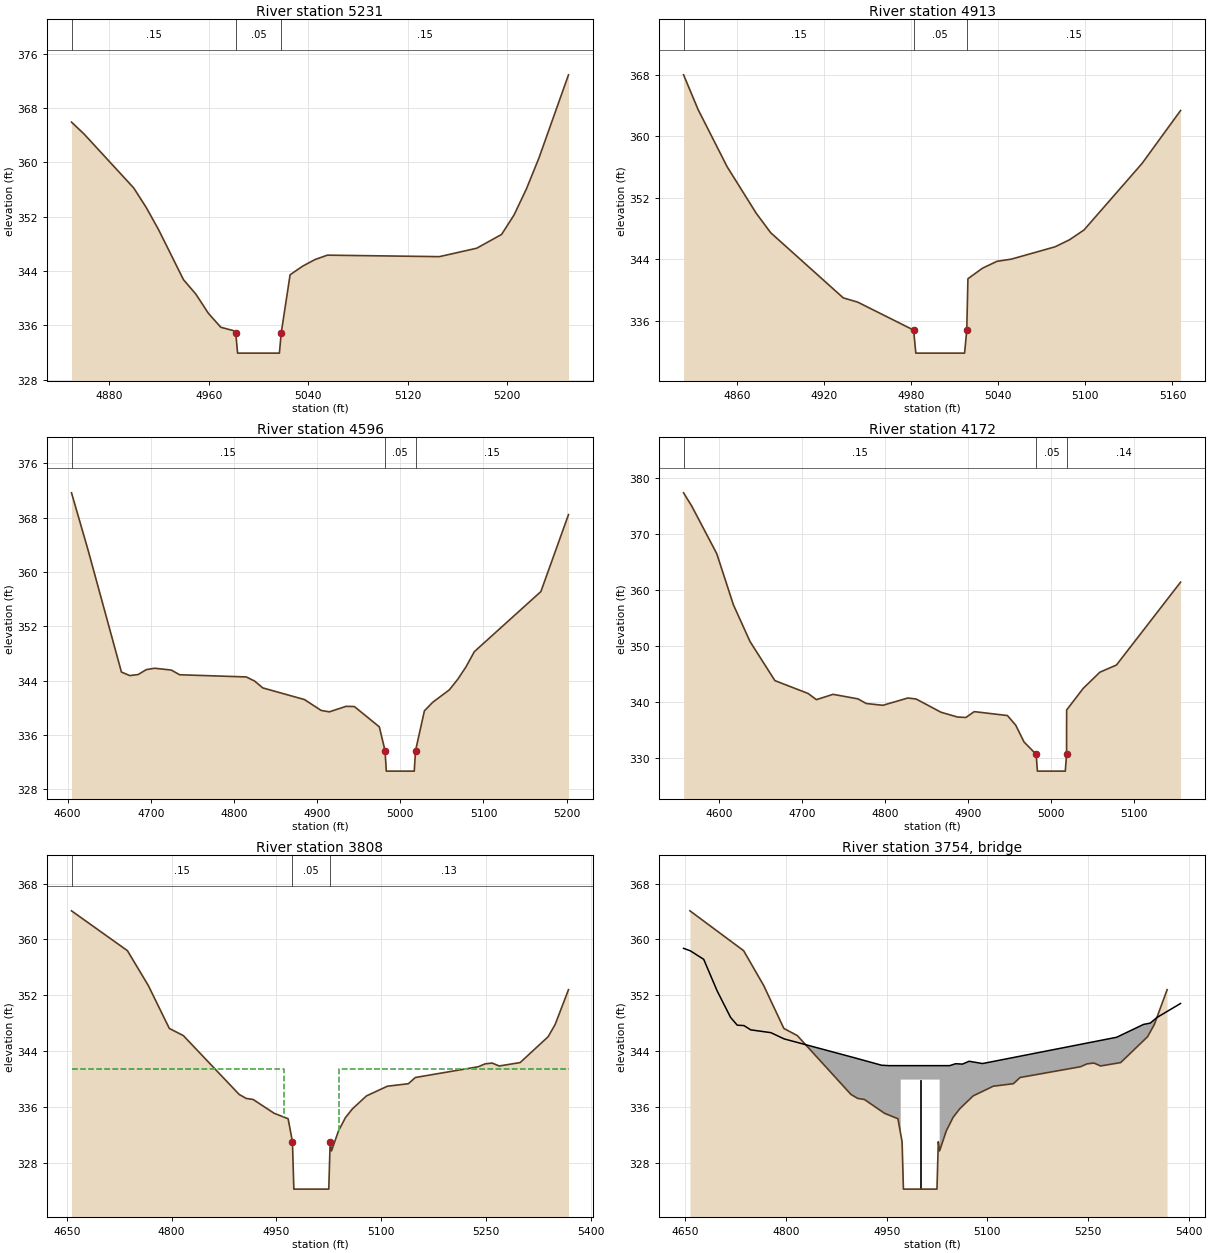
Type RM Length L Ch R = 1 ,5231    ,318,318,318
BEGIN DESCRIPTION:
Barnes Creek 11.0
END DESCRIPTION:
XS GIS Cut Line= 3
      1703678.46       616825.63      1703555.17       616903.26
      1703354.33       617058.45
#Sta/Elev= 25
  4849.7  365.93  4859.7   364.2  4899.7  356.24  4909.7  353.38  4919.7  350.09
  4939.7  342.73  4949.7  340.59  4959.7  337.78  4969.7  335.72  4979.7  335.23
  4981.7  334.91  4983.2  331.91  5016.8  331.91  5018.3  334.91  5025.4  343.45
  5035.4  344.71  5045.4  345.69  5055.4  346.34  5145.4  346.12  5175.4  347.36
  5195.4  349.39  5205.4  352.25  5215.4  356.11  5225.4  360.63  5249.2   372.9
#Mann= 3 ,-1 , 0
  4849.7     .15       0  4981.7     .05       0  5018.3     .15       0
Bank Sta=4981.7,5018.3
Exp/Cntr=0.3,0.1

Type RM Length L Ch R = 1 ,4913    ,317,317,317
BEGIN DESCRIPTION:
Barnes Creek 10.0
END DESCRIPTION:
XS GIS Cut Line= 3
       1703459.3       616549.47      1703336.05         616675.
      1703244.76       616814.22
#Sta/Elev= 20
  4823.2  368.01  4833.2  363.49  4853.2  356.04  4873.2  349.99  4883.2  347.44
  4933.2  338.95  4943.2  338.39  4981.7  334.75  4983.2  331.75  5016.8  331.75
  5018.3  334.75  5019.1  341.44  5029.1  342.81  5039.1  343.71  5049.1     344
  5079.1   345.6  5089.1  346.52  5099.1   347.8  5139.1  356.47  5165.6  363.36
#Mann= 3 ,-1 , 0
  4823.2     .15       0  4981.7     .05       0  5018.3     .15       0
Bank Sta=4981.7,5018.3
Exp/Cntr=0.3,0.1

Type RM Length L Ch R = 1 ,4596    ,424,424,424
BEGIN DESCRIPTION:
Barnes Creek 9.0
END DESCRIPTION:
XS GIS Cut Line= 3
      1703272.15       616170.55      1703068.99       616508.38
      1702975.39       616688.73
#Sta/Elev= 30
  4604.8  371.66  4624.8  363.19  4664.8  345.27  4674.8  344.75  4684.8   344.9
  4694.8  345.63  4704.8  345.83  4724.8  345.56  4734.8  344.87  4814.8  344.55
  4824.8  343.95  4834.8  342.93  4884.8  341.22  4904.8  339.62  4914.8  339.41
  4934.8  340.22  4944.8  340.19  4974.8   337.2  4981.7  333.68  4983.2  330.68
  5016.8  330.68  5018.3  333.68    5029  339.56    5039  340.82    5059  342.65
    5069  344.19    5079  346.04    5089  348.27    5169  357.12  5202.2  368.45
#Mann= 3 ,-1 , 0
  4604.8     .15       0  4981.7     .05       0  5018.3     .15       0
Bank Sta=4981.7,5018.3
Exp/Cntr=0.3,0.1

Type RM Length L Ch R = 1 ,4172    ,364,364,364
BEGIN DESCRIPTION:
Barnes Creek 8.0
END DESCRIPTION:
XS GIS Cut Line= 3
      1702854.43       615933.21      1702699.23       616346.32
       1702626.2       616485.53
#Sta/Elev= 30
  4557.1  377.37  4567.1  374.96  4597.1  366.49  4617.1  357.37  4637.1  350.81
  4667.1  343.82  4707.1  341.52  4717.1  340.42  4737.1  341.37  4767.1  340.56
  4777.1  339.73  4797.1  339.41  4827.1  340.71  4837.1  340.54  4867.1  338.17
  4887.1  337.31  4897.1  337.24  4907.1  338.28  4947.1  337.58  4957.1  335.86
  4967.1  332.86  4981.7  330.65  4983.2  327.65  5016.8  327.65  5018.3  330.65
  5018.4  338.57  5038.4  342.44  5058.4  345.32  5078.4  346.61  5155.6  361.41
#Mann= 3 ,-1 , 0
  4557.1     .15       0  4981.7     .05       0  5018.3     .14       0
Bank Sta=4981.7,5018.3
Exp/Cntr=0.5,0.3

Type RM Length L Ch R = 1 ,3808    ,112,112,112
BEGIN DESCRIPTION:
SR-1303-US
END DESCRIPTION:
XS GIS Cut Line= 3
      1702442.53       615763.57      1702444.41       616105.66
      1702435.22       616474.75
#Sta/Elev= 30
  4656.8  364.09  4736.8  358.38  4766.8  353.37  4796.8  347.23  4816.8  346.21
  4896.8  337.77  4906.8   337.2  4916.8  337.05  4946.8  335.07  4966.8  334.29
    4973     331    4975   324.2    5025   324.2    5027     331  5028.9  329.68
  5038.9  332.54  5048.9  334.46  5058.9  335.71  5078.9  337.56  5108.9  338.95
  5138.9  339.31  5148.9   340.2  5238.9  341.74  5248.9  342.16  5258.9  342.27
  5268.9  341.85  5298.9  342.34  5338.9  346.04  5348.9  347.78  5368.1  352.79
#Mann= 3 ,-1 , 0
  4656.8     .15       0    4973     .05       0    5027     .13       0
#XS Ineff= 2 , 0
       0    4961  341.36    5039       0  341.36
Permanent Ineff=
       F       F
Bank Sta=4973,5027
Exp/Cntr=0.5,0.3

Type RM Length L Ch R = 3 ,3754    ,,,
BEGIN DESCRIPTION:
SR-1303-TOR
Structure ID: LDS_BAC_01
Approximate Survey Structure
END DESCRIPTION:
Bridge Culvert--1,0,-1,-1, 0
Deck Dist Width WeirC Skew NumUp NumDn MinLoCord MaxHiCord MaxSubmerge Is_Ogee
43.5,21,3,0, 27, 27, , , 0.95, 0, 1,1,,
  4647.3  4657.3  4677.3  4697.3  4717.3  4727.3  4737.3  4747.3  4777.3  4797.3
  4902.4  4942.4    4953    4971    4971    5029    5029  5043.9  5052.9  5062.9
  5072.9  5092.9  5292.9  5332.9  5342.9  5352.9  5388.1
  358.71  358.36  357.14  352.62  348.82   347.7  347.64  347.03  346.63  345.73
  343.02  341.96   341.9   341.9   341.9   341.9   341.9   341.9  342.18  342.12
  342.53   342.2  345.97  347.81     348   348.8  350.81
   304.2   304.2   304.2   304.2   304.2   304.2   304.2   304.2   304.2   304.2
   304.2   304.2   304.2   304.2   339.9   339.9   304.2   304.2   304.2   304.2
   304.2   304.2   304.2   304.2   304.2   304.2   304.2
  4647.3  4657.3  4677.3  4697.3  4717.3  4727.3  4737.3  4747.3  4777.3  4797.3
  4902.4  4942.4    4953    4971    4971    5029    5029  5043.9  5052.9  5062.9
  5072.9  5092.9  5292.9  5332.9  5342.9  5352.9  5388.1
  358.71  358.36  357.14  352.62  348.82   347.7  347.64  347.03  346.63  345.73
  343.02  341.96   341.9   341.9   341.9   341.9   341.9   341.9  342.18  342.12
  342.53   342.2  345.97  347.81     348   348.8  350.81
   304.2   304.2   304.2   304.2   304.2   304.2   304.2   304.2   304.2   304.2
   304.2   304.2   304.2   304.2   339.9   339.9   304.2   304.2   304.2   304.2
   304.2   304.2   304.2   304.2   304.2   304.2   304.2
Pier Skew, UpSta & Num, DnSta & Num=  ,5000, 2 ,5000, 2 , 0 , 0 , 0 ,0,0
     1.5     1.5
   324.2   339.9
     1.5     1.5
  323.95   339.9
BR Coef= 1 , 1 , 0 ,1.25, 0 ,,,0.8,0,2,0,
WSPro=,,,, 1 ,,,, 0 ,,,, 0 ,,,,-1 ,-1 ,-1 , 0 , 0 , 0 , 0 , 0
BC Design=,, 0 ,, 0 ,,,,,,
BC HTab HWMax=364.09

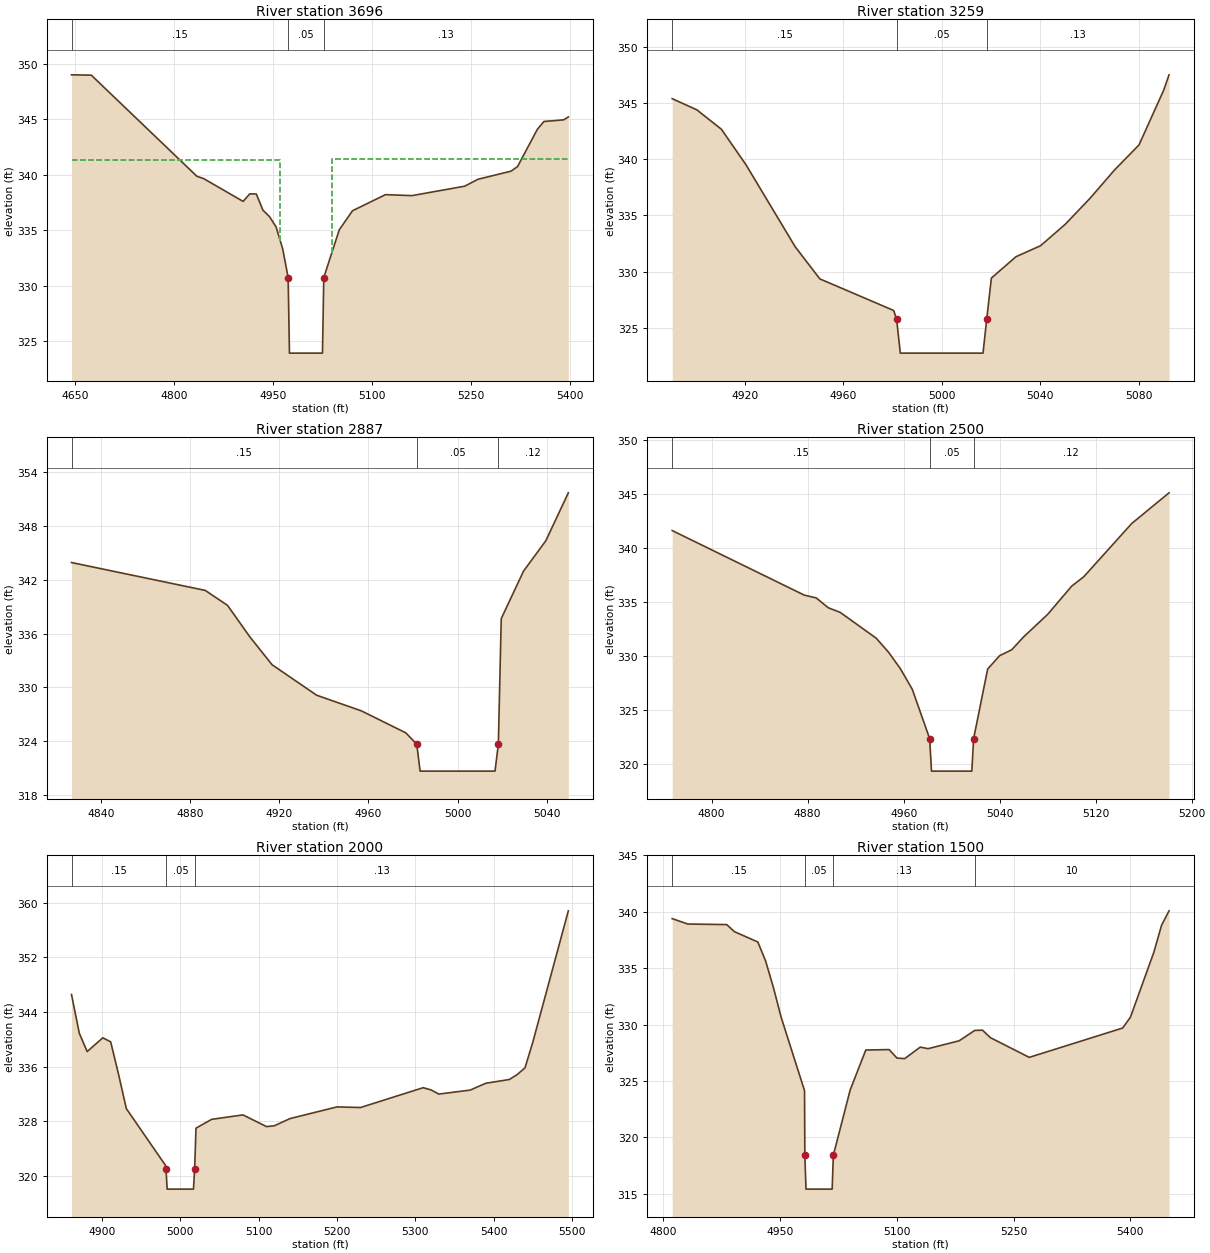
Type RM Length L Ch R = 1 ,3696    ,437,437,437
BEGIN DESCRIPTION:
SR-1303-DS
END DESCRIPTION:
XS GIS Cut Line= 3
      1702347.55       615709.99      1702340.24       616065.57
       1702330.5        616462.5
#Sta/Elev= 27
  4644.8  348.99  4674.8  348.96  4834.8  339.86  4844.8  339.66  4904.8   337.6
  4914.8  338.28  4924.8  338.27  4934.8  336.81  4944.8  336.23  4954.8   335.3
  4964.8  333.32    4973  330.75    4975  323.95    5025  323.95    5027  330.75
  5050.5  335.05  5070.5  336.76  5120.5  338.21  5160.5  338.12  5240.5  338.97
  5260.5  339.59  5310.5  340.32  5320.5  340.73  5350.5  344.08  5360.5  344.79
  5390.5  344.94  5397.5   345.2
#Mann= 3 ,-1 , 0
  4644.8     .15       0    4973     .05       0    5027     .13       0
#XS Ineff= 2 , 0
       0    4961  341.33    5039       0  341.46
Permanent Ineff=
       F       F
Bank Sta=4973,5027
Exp/Cntr=0.5,0.3

Type RM Length L Ch R = 1 ,3259    ,372,372,372
BEGIN DESCRIPTION:
Barnes Creek 7.0
END DESCRIPTION:
XS GIS Cut Line= 3
      1701966.35       615962.77      1701915.35       616059.87
      1701892.17       616149.13
#Sta/Elev= 20
  4890.5  345.37  4900.5  344.38  4910.5  342.65  4920.5  339.49  4940.5   332.2
  4950.5  329.35  4980.5  326.54  4981.7  325.75  4983.2  322.75  5016.8  322.75
  5018.3  325.75  5020.2  329.42  5030.2  331.32  5040.2   332.3  5050.2   334.2
  5060.2  336.49  5070.2  339.02  5080.2  341.26  5090.2  346.11  5092.4  347.49
#Mann= 3 ,-1 , 0
  4890.5     .15       0  4981.7     .05       0  5018.3     .13       0
Bank Sta=4981.7,5018.3
Exp/Cntr=0.3,0.1

Type RM Length L Ch R = 1 ,2887    ,387,387,387
BEGIN DESCRIPTION:
Barnes Creek 6.0
END DESCRIPTION:
XS GIS Cut Line= 3
      1701979.14       615818.63      1701807.49       615798.91
      1701758.73        615787.3
#Sta/Elev= 17
  4826.8  343.93  4886.8  340.82  4896.8  339.15  4906.8  335.64  4916.8  332.52
  4936.8  329.12  4956.8  327.38  4976.8  324.92  4981.7  323.65  4983.2  320.65
  5016.8  320.65  5018.3  323.65  5019.6  337.67  5029.6  342.97  5039.6  346.36
  5049.6  351.66  5049.7  351.71
#Mann= 3 ,-1 , 0
  4826.8     .15       0  4981.7     .05       0  5018.3     .12       0
Bank Sta=4981.7,5018.3
Exp/Cntr=0.3,0.1

Type RM Length L Ch R = 1 ,2500    ,500,500,500
BEGIN DESCRIPTION:
Barnes Creek 5.0
END DESCRIPTION:
XS GIS Cut Line= 3
      1702140.36       615576.23      1701947.84       615445.34
      1701795.16       615347.94
#Sta/Elev= 22
  4767.2   341.6  4877.2  335.63  4887.2  335.37  4897.2  334.46  4907.2  334.03
  4937.2  331.64  4947.2  330.38  4957.2  328.84  4967.2  326.92  4981.7  322.35
  4983.2  319.35  5016.8  319.35  5018.3  322.35    5030  328.79    5040  330.03
    5050  330.57    5060  331.77    5080  333.85    5100  336.46    5110  337.32
    5150  342.25  5181.1  345.09
#Mann= 3 ,-1 , 0
  4767.2     .15       0  4981.7     .05       0  5018.3     .12       0
Bank Sta=4981.7,5018.3
Exp/Cntr=0.3,0.1

Type RM Length L Ch R = 1 ,2000    ,500,500,500
BEGIN DESCRIPTION:
Barnes Creek 4.0
END DESCRIPTION:
XS GIS Cut Line= 3
      1702341.17       615081.72      1702215.33       615022.92
      1701746.19       614864.06
#Sta/Elev= 30
  4861.1  346.55  4871.1  340.87  4881.1  338.21  4901.1  340.22  4911.1  339.63
  4921.1  334.91  4931.1  329.86  4981.1  321.55  4981.7  321.08  4983.2  318.08
  5016.8  318.08  5018.3  321.08    5020     327    5040  328.29    5080  328.94
    5110  327.23    5120  327.35    5140   328.4    5200  330.11    5230  330.02
    5310  332.92    5320   332.6    5330  331.99    5370  332.57    5390  333.57
    5420  334.12    5430  334.84    5440  335.83    5450   339.6  5495.3   358.8
#Mann= 3 ,-1 , 0
  4861.1     .15       0  4981.7     .05       0  5018.3     .13       0
Bank Sta=4981.7,5018.3
Exp/Cntr=0.3,0.1

Type RM Length L Ch R = 1 ,1500    ,732,732,732
BEGIN DESCRIPTION:
Barnes Creek 3.0
END DESCRIPTION:
XS GIS Cut Line= 3
      1702505.56       614588.61      1702318.17       614566.38
      1701869.42       614594.05
#Sta/Elev= 30
  4811.3   339.4  4831.3  338.92  4881.3  338.87  4891.3  338.24  4921.3  337.33
  4931.3  335.65  4941.3   333.3  4951.3  330.65  4981.3  324.15  4981.7  318.42
  4983.2  315.42  5016.8  315.42  5018.3  318.42    5040  324.22    5060  327.75
    5090  327.79    5100  327.04    5110  326.99    5130  328.01    5140  327.87
    5180  328.57    5200  329.49    5210  329.51    5220  328.85    5270   327.1
    5390   329.7    5400  330.66    5430   336.4    5440  338.81  5449.6  340.09
#Mann= 4 ,-1 , 0
  4811.3     .15       0  4981.7     .05       0  5018.3     .13       0
    5200      10       0
Bank Sta=4981.7,5018.3
Exp/Cntr=0.3,0.1

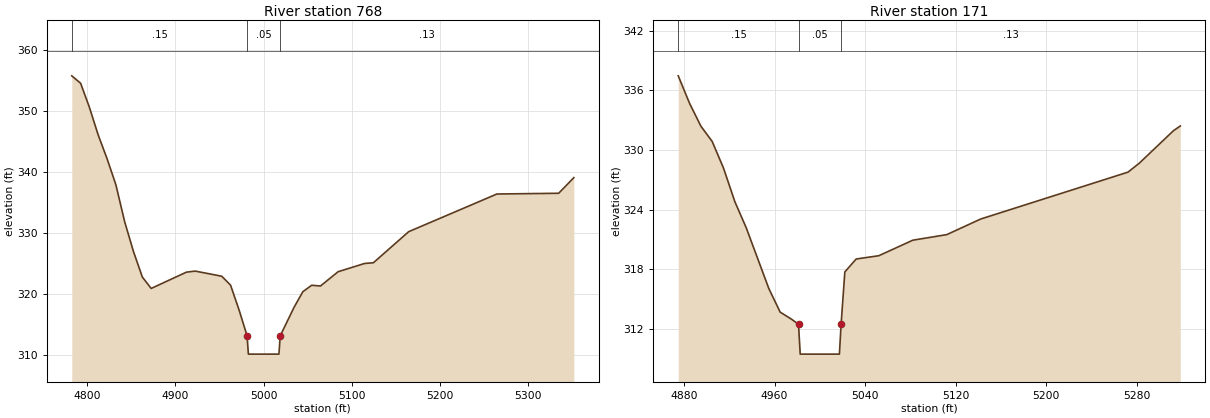
Type RM Length L Ch R = 1 ,768     ,597,597,597
BEGIN DESCRIPTION:
Barnes Creek 2.0
END DESCRIPTION:
XS GIS Cut Line= 3
      1701894.12       613919.66      1701916.77       614130.35
      1701864.67       614483.73
#Sta/Elev= 30
  4782.5   355.7  4792.5  354.49  4802.5  350.54  4812.5  345.99  4822.5  342.13
  4832.5  337.86  4842.5  331.78  4852.5  326.89  4862.5  322.74  4872.5  320.87
  4912.5  323.54  4922.5  323.71  4952.5  322.87  4962.5  321.41  4972.5  317.19
  4981.2  313.11  4982.7  310.11  5017.3  310.11  5018.8  313.11  5034.4  317.76
  5044.4  320.33  5054.4  321.39  5064.4  321.27  5084.4  323.61  5114.4  324.96
  5124.4  325.08  5164.4  330.17  5264.4  336.34  5334.4  336.46  5351.6  339.02
#Mann= 3 ,-1 , 0
  4782.5     .15       0  4981.2     .05       0  5018.8     .13       0
Bank Sta=4981.2,5018.8
Exp/Cntr=0.3,0.1

Type RM Length L Ch R = 1 ,171     ,0,0,0
BEGIN DESCRIPTION:
Barnes Creek 1.0
END DESCRIPTION:
XS GIS Cut Line= 3
      1701382.18       614193.74      1701357.25       614318.36
      1701327.81        614633.2
#Sta/Elev= 24
    4875  337.46    4885   334.7    4895   332.4    4905  330.86    4915  328.18
    4925  324.81    4935   322.2    4955  316.08    4965  313.71    4975     313
  4981.2  312.49  4982.7  309.49  5017.3  309.49  5018.8  312.49  5022.1  317.75
  5032.1  319.05  5052.1  319.38  5082.1  320.94  5112.1   321.5  5142.1  323.07
  5272.1  327.78  5282.1  328.68  5312.1  331.93  5318.3  332.42
#Mann= 3 ,-1 , 0
    4875     .15       0  4981.2     .05       0  5018.8     .13       0
Bank Sta=4981.2,5018.8
Exp/Cntr=0.3,0.1

Chan Stop Cuts=-1
Use User Specified Reach Order=0
User Specified Reach Order=Barnes Creek    ,Reach-1