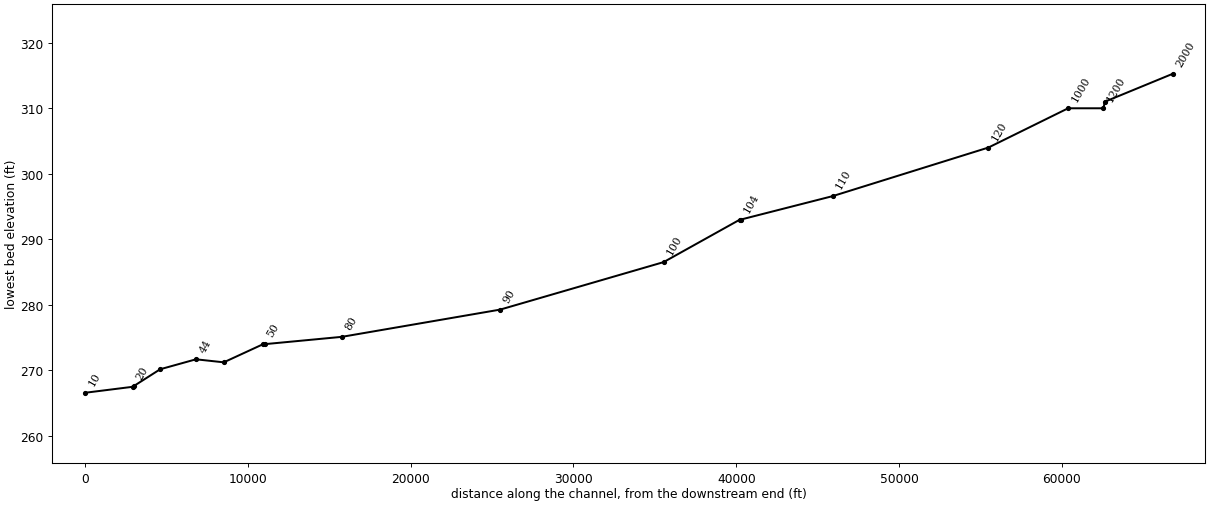
--- REACH4_REV.PRJ (project) ---

Proj Title=Drowning Creek reach 4
Current Plan=P01
Default Exp/Contr=.3,.1
English Units
Geom File=G01
Flow File=F01
Plan File=P01
Y Axis Title=Elevation
X Axis Title(PF)=Main Channel Distance
X Axis Title(XS)=Station
BEGIN DESCRIPTION:
Approximate Analysis
END DESCRIPTION:
DSS Export Rating Curves= 0
DSS Export Rating Curve Sorted= 0
DSS Export Volume Flow Curves= 0
DXF OffsetX= 0
DXF OffsetY= 0
DXF ScaleX= 1
DXF ScaleY= 10

--- REACH4_REV.P01 (plan) ---

Plan Title=Approximate Analysis
Version=Version 3.0.1  Mar 2001
Short Identifier=approximate
Geom File=G01
Flow File=F01
Subcritical Flow
K Sum by GR= 0
Std Step Tol= 0.01
Critical Tol= 0.01
Num of Std Step Trials= 20
Max Error Tol= 0.3
Flow Tol Ratio= 0.001
Split Flow NTrial= 30
Split Flow Tol= 0.02
Split Flow Ratio= 0.02
Log Output Level= 0
Friction Slope Method= 1
Unsteady Friction Slope Method= 2
Parabolic Critical Depth
Global Vel Dist= 1 , 1 , 1
Global Log Level= 0
CheckData=True
Encroach Param=-1 ,0,0, 2
Encroach River=Reach #1
Encroach Reach=Approximate Anal
Encroach Node=2000
       4      .1
Encroach Node=1600
       1 3228.47    4397
Encroach Node=1400
       4       1
Encroach Node=1200
       4     1.5
Encroach Node=1000
       4      .1
Encroach Node=120
       4       1
Encroach Node=110
       4      .2
Encroach Node=106
       1 1863.67    2500
Encroach Node=105
       4       1
Encroach Node=104
       1 1863.67    2450
Encroach Node=100
       4      .2
Encroach Node=90
       4       1
Encroach Node=80
       4       1
Encroach Node=70
       4      .7
Encroach Node=60
       4      .7
Encroach Node=50
       4      .7
Encroach Node=46
       4      .7
Encroach Node=44
       4       1
Encroach Node=42
       1    2011    2449
Encroach Node=40
       1    2758    3137
Encroach Node=30
       4      .7
Encroach Node=20
       1    2758    3137
Encroach Node=10
       1 3841.61 4605.91
Computation Interval=1HOUR
Output Interval=1HOUR
Run HTab= 0
Run UNet= 0
Run PostProcess= 0
UNET Theta= 1
UNET ZTol= 0.02
UNET ZSATol= 0.1
UNET MxIter= 20
UNET MaxInSteps= 20
UNET DtIC= 0
UNET DtMin= 0
UNET MaxCRTS= 20
UNET WFStab= 2
UNET SFStab= 1
UNET WFX= 1
UNET SFX= 1
UNET Convert EG Bridges=-1
UNET Use Existing IB Tables=-1
Instantaneous Interval=1HOUR
Write IC File= 0
Write Velocity= 0
Write Detailed= 0

--- REACH4_REV.F01 (steady flow) ---

Flow Title=2 Flow Profiles
Version=Version 3.0.1  Mar 2001
Number of Profiles= 2
Profile Names=PF 1,PF 2
River Rch & RM=Reach #1,Approximate Anal,2000
    4528    4528
River Rch & RM=Reach #1,Approximate Anal,120
    6039    6039
River Rch & RM=Reach #1,Approximate Anal,110
    6134    6134
River Rch & RM=Reach #1,Approximate Anal,90
    6488    6488
River Rch & RM=Reach #1,Approximate Anal,80
    7922    7922
River Rch & RM=Reach #1,Approximate Anal,70
    8050    8050
River Rch & RM=Reach #1,Approximate Anal,46
    8228    8228
Boundary for River Rch & Prof#=Reach #1,Approximate Anal, 1
Up Type= 0
Dn Type= 1
Dn Known WS=272.77
Boundary for River Rch & Prof#=Reach #1,Approximate Anal, 2
Up Type= 0
Dn Type= 1
Dn Known WS=273.44
DSS Import GetInterval= 0
DSS Import GetPeak= 0
DSS Import FillOption= 0

--- REACH4_REV.G01 (geometry) ---

Geom Title=Base Conditions Geometry
Version=Version 3.0.1  Mar 2001

River Reach=Reach #1        ,Approximate Anal
Reach XY= 2
              .9         .298366              .1         .701634

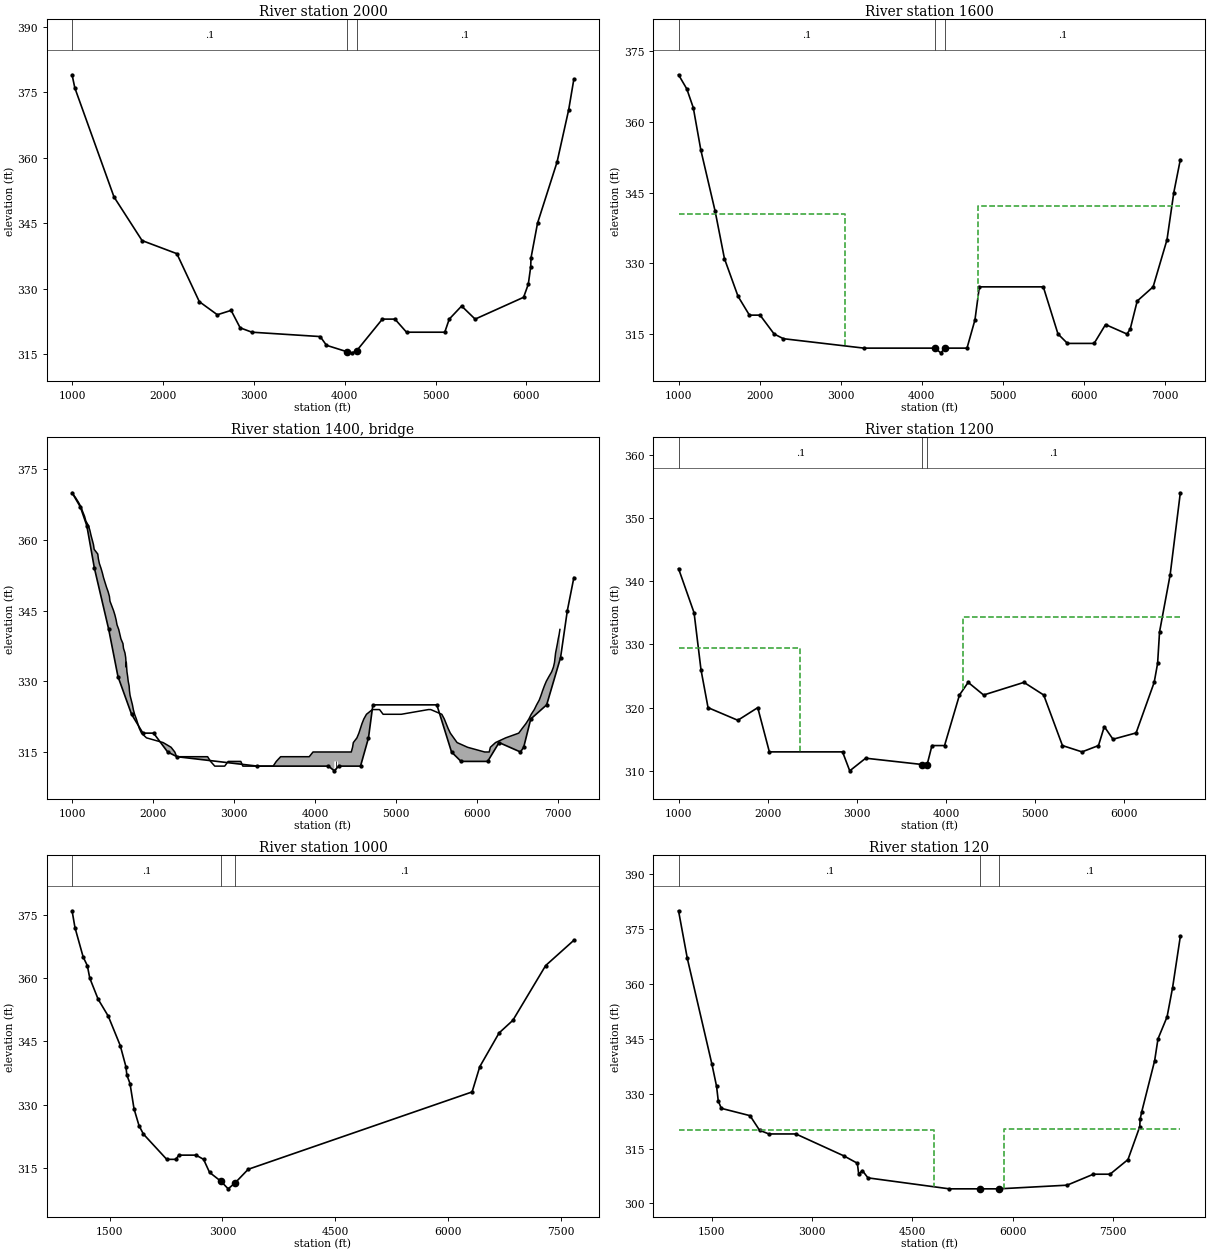
Type RM Length L Ch R = 1 ,2000    ,3000.01,4175.72,3104.39
#Sta/Elev= 30
    1000     379 1030.28     376 1461.47     351 1770.42     341 2153.28     338
 2400.59     327 2598.84     324 2750.38     325  2850.1     321 2979.48     320
 3730.77     319 3800.12     317 4021.43  315.55 4082.37  315.27 4131.12  315.72
 4415.25     323 4553.35     323 4680.86     320  5101.8     320 5151.27     323
 5287.32     326 5436.15     323 5969.63     328 6021.24     331 6047.87     335
 6050.86     337 6123.02     345 6337.83     359 6465.96     371 6522.75     378
#Mann= 3 , 0 , 0
    1000      .1       0 4021.43     .05       0 4131.12      .1       0
Bank Sta=4021.43,4131.12
XS Rating Curve= 0
Exp/Cntr=.5,.3

Type RM Length L Ch R = 1 ,1600    ,81,81,81
#Sta/Elev= 30
    1000     370 1102.03     367 1182.27     363 1275.66     354 1452.54     341
 1566.65     331 1734.42     323 1874.96     319 2006.49     319 2180.24     315
 2294.71     314  3288.6     312  4165.5     312  4237.6     311 4292.04     312
  4561.4     312  4659.7     318 4713.84     325 5503.49     325 5684.81     315
 5802.18     313 6130.87     313  6271.7     317  6535.8     315 6575.75     316
 6662.99     322 6859.31     325 7030.59     335 7114.65     345 7195.16     352
#Mann= 3 , 0 , 0
    1000      .1       0  4165.5     .05       0 4292.04      .1       0
#XS Ineff= 2 , 0
         3054.89  340.36 4692.12          342.06
Permanent Ineff=
       F       F
Bank Sta=4165.5,4292.04
XS Rating Curve= 0
Exp/Cntr=.5,.3

Type RM Length L Ch R = 3 ,1400    ,,,
Bridge Culvert--1,0,-1,-1, 0
Deck Dist Width WeirC Skew NumUp NumDn MinLoCord MaxHiCord MaxSubmerge Is_Ogee
52,18,2.6,0, 143, 143, 312, , .95, 0, 0,0,,
    1000 1042.09 1078.34 1110.28 1131.02 1154.48 1170.45 1202.95 1220.41 1233.59
 1248.94  1264.3 1272.82 1317.45 1324.65 1337.02 1356.89 1374.01 1388.34 1406.75
 1424.63 1445.34 1461.33 1467.98 1489.86 1512.14 1529.99 1544.16 1554.65 1575.97
 1589.35 1603.36 1628.21 1634.82  1653.4 1662.32 1669.06 1669.25 1677.83  1686.5
 1693.21 1704.59 1708.57 1716.22 1730.42 1745.43 1756.41 1771.93 1793.84 1811.54
 1830.07 1857.28 1918.62 2124.02 2222.34 2267.93 2291.54 2532.87 2673.46 2710.11
  2761.8 2817.57 2842.82 2884.33 2927.04 3083.28 3108.64  3188.5 3350.77 3482.46
 3521.24 3575.05 3757.75  3781.7 3870.15 3928.24 3974.58 4033.34 4061.29 4078.27
 4106.39 4163.11 4190.94 4217.41 4224.48 4232.34 4237.16 4273.32 4279.76  4282.1
 4288.91 4291.94 4447.16 4463.08 4472.45 4516.89 4541.04 4560.12  4578.8 4601.91
 4634.57 4707.21  4796.3 4840.14 5064.02 5399.41    5428 5564.85 5595.69 5618.89
 5642.53 5669.94 5711.46 5753.24 5882.99 6093.91 6150.25 6164.38 6227.96 6353.58
 6514.59 6557.34 6602.35 6639.82 6668.73 6706.78 6735.12 6767.42 6789.42 6808.94
 6830.37 6854.82 6886.87 6920.96 6942.91 6956.18 6962.22 6969.44 6980.88 6992.13
  7002.1 7014.22 7023.01
     370     369     368     367     366     365     364     363     362     361
     360     359     358     357     356     355     354     353     352     351
     350     349     348     347     346     345     344     343     342     341
     340     339     338     337     336     335     333     334     332     331
     330     329     328     327     326     325     324     323     322     321
     320     319     318     317     316     315     314     314     314     313
     312     312     312     312     313     313     312     312     312     312
     313     314     314     314     314     314     315     315     315     315
     315     315     315     315     315     315     315     315     315     315
     315     315     315     316     317     318     319     320     321     322
     323     324     324     323     323     324     324     323     322     321
     320     319     318     317     316     315     315     316     317     318
     319     320     321     322     323     324     325     326     327     328
     329     330     331     332     333     334     335     336     337     338
     339     340     341
                                                                                
                                                                                
                                                                                
                                                                                
                                                                                
                                                                                
                                                                                
                                                                                
                                                     313     313     313     313
                                                                                
                                                                                
                                                                                
                                                                                
                                                                                
                        
     507  549.09  585.34  617.28  638.02  661.48  677.45  709.95  727.41  740.59
  755.94   771.3  779.82  824.45  831.65  844.02  863.89  881.01  895.34  913.75
  931.63  952.34  968.33  974.98  996.86 1019.14 1036.99 1051.16 1061.65 1082.97
 1096.35 1110.36 1135.21 1141.82  1160.4 1169.32 1176.06 1176.25 1184.83  1193.5
 1200.21 1211.59 1215.57 1223.22 1237.42 1252.43 1263.41 1278.93 1300.84 1318.54
 1337.07 1364.28 1425.62 1631.02 1729.34 1774.93 1798.54 2039.87 2180.46 2217.11
  2268.8 2324.57 2349.82 2391.33 2434.04 2590.28 2615.64  2695.5 2857.77 2989.46
 3028.24 3082.05 3264.75  3288.7 3377.15 3435.24 3481.58 3540.34 3568.29 3585.27
 3613.39 3670.11 3697.94 3724.41 3731.48 3739.34 3744.16 3780.32 3786.76  3789.1
 3795.91 3798.94 3954.16 3970.08 3979.45 4023.89 4048.04 4067.12  4085.8 4108.91
 4141.57 4214.21  4303.3 4347.14 4571.02 4906.41    4935 5071.85 5102.69 5125.89
 5149.53 5176.94 5218.46 5260.24 5389.99 5600.91 5657.25 5671.38 5734.96 5860.58
 6021.59 6064.34 6109.35 6146.82 6175.73 6213.78 6242.12 6274.42 6296.42 6315.94
 6337.37 6361.82 6393.87 6427.96 6449.91 6463.18 6469.22 6476.44 6487.88 6499.13
  6509.1 6521.22 6530.01
     370     369     368     367     366     365     364     363     362     361
     360     359     358     357     356     355     354     353     352     351
     350     349     348     347     346     345     344     343     342     341
     340     339     338     337     336     335     333     334     332     331
     330     329     328     327     326     325     324     323     322     321
     320     319     318     317     316     315     314     314     314     313
     312     312     312     312     313     313     312     312     312     312
     313     314     314     314     314     314     315     315     315     315
     315     315     315     315     315     315     315     315     315     315
     315     315     315     316     317     318     319     320     321     322
     323     324     324     323     323     324     324     323     322     321
     320     319     318     317     316     315     315     316     317     318
     319     320     321     322     323     324     325     326     327     328
     329     330     331     332     333     334     335     336     337     338
     339     340     341
                                                                                
                                                                                
                                                                                
                                                                                
                                                                                
                                                                                
                                                                                
                                                                                
                                                     313     313     313     313
                                                                                
                                                                                
                                                                                
                                                                                
                                                                                
                        
Pier Skew, UpSta & Num, DnSta & Num=  ,4258.8, 2 ,3765.8, 2 , 0 , 0 , 0 ,,
       1       1
     307     323
       1       1
     307     323
BR Coef= 1 , 1 , 0 ,, 0 ,,,.8,0,1.2,0,
WSPro=,,,, 1 ,,,, 0 ,,,, 0 ,,,,-1 ,-1 ,-1 , 0 , 0 , 0 , 0 , 0
BC Design=,, 0 ,, 0 ,,,,,,

Type RM Length L Ch R = 1 ,1200    ,1193.69,2172.12,1472.96
#Sta/Elev= 30
    1000     342  1174.5     335  1251.9     326 1330.96     320 1665.06     318
 1888.42     320 2018.84     313 2839.68     313  2920.4     310 3099.14     312
 3733.98     311  3788.6     311 3842.58     314  3983.8     314 4151.19     322
 4248.84     324 4421.98     322  4874.6     324 5096.07     322 5306.12     314
 5525.68     313 5710.52     314 5775.61     317 5873.19     315 6132.37     316
 6335.19     324 6373.63     327 6395.48     332 6514.09     341 6628.47     354
#Mann= 3 , 0 , 0
    1000      .1       0 3733.98     .05       0  3788.6      .1       0
#XS Ineff= 2 , 0
         2360.38  329.43 4195.88          334.42
Permanent Ineff=
       F       F
Bank Sta=3733.98,3788.6
XS Rating Curve= 0
Exp/Cntr=.5,.3

Type RM Length L Ch R = 1 ,1000    ,3388.78,4899.63,3463.66
#Sta/Elev= 30
    1000     376 1038.78     372 1148.17     365 1202.75     363 1235.81     360
 1347.02     355 1481.19     351  1641.1     344 1716.34     339 1729.09     337
 1770.66     335  1824.3     329  1890.8     325 1948.98     323 2259.38     317
 2380.86     317 2420.54     318 2649.24     318 2749.83     317 2828.84  313.91
 2980.94  311.79 3077.03     310 3171.07  311.45    3343314.6363 6322.25     333
 6424.51     339 6681.19     347 6864.66     350 7300.85     363  7676.1     369
#Mann= 3 , 0 , 0
    1000      .1       0 2980.94     .05       0 3171.07      .1       0
Bank Sta=2980.94,3171.07
XS Rating Curve= 0
Exp/Cntr=.3,.1

Type RM Length L Ch R = 1 ,120     ,5232.67,9559.03,5839.69
#Sta/Elev= 30
    1000     380 1131.14     367 1500.51     338 1569.35     332 1594.75     328
 1640.38     326 2069.48     324 2213.08     320 2352.57     319 2756.28     319
 3475.05     313    3676     311 3696.27     308 3751.26     309 3834.44     307
 5051.56     304 5512.82     304 5795.23     304 6814.59     305 7208.54     308
 7457.56     308 7725.92     312 7902.38     321 7907.38     323    7931     325
 8124.79     339 8175.23     345 8310.83     351 8393.55     359 8509.36     373
#Mann= 3 , 0 , 0
    1000      .1       0 5512.82     .05       0 5795.23      .1       0
#XS Ineff= 2 , 0
            4821  320.08 5871.12           320.4
Permanent Ineff=
       F       F
Bank Sta=5512.82,5795.23
XS Rating Curve= 0
Exp/Cntr=.3,.1

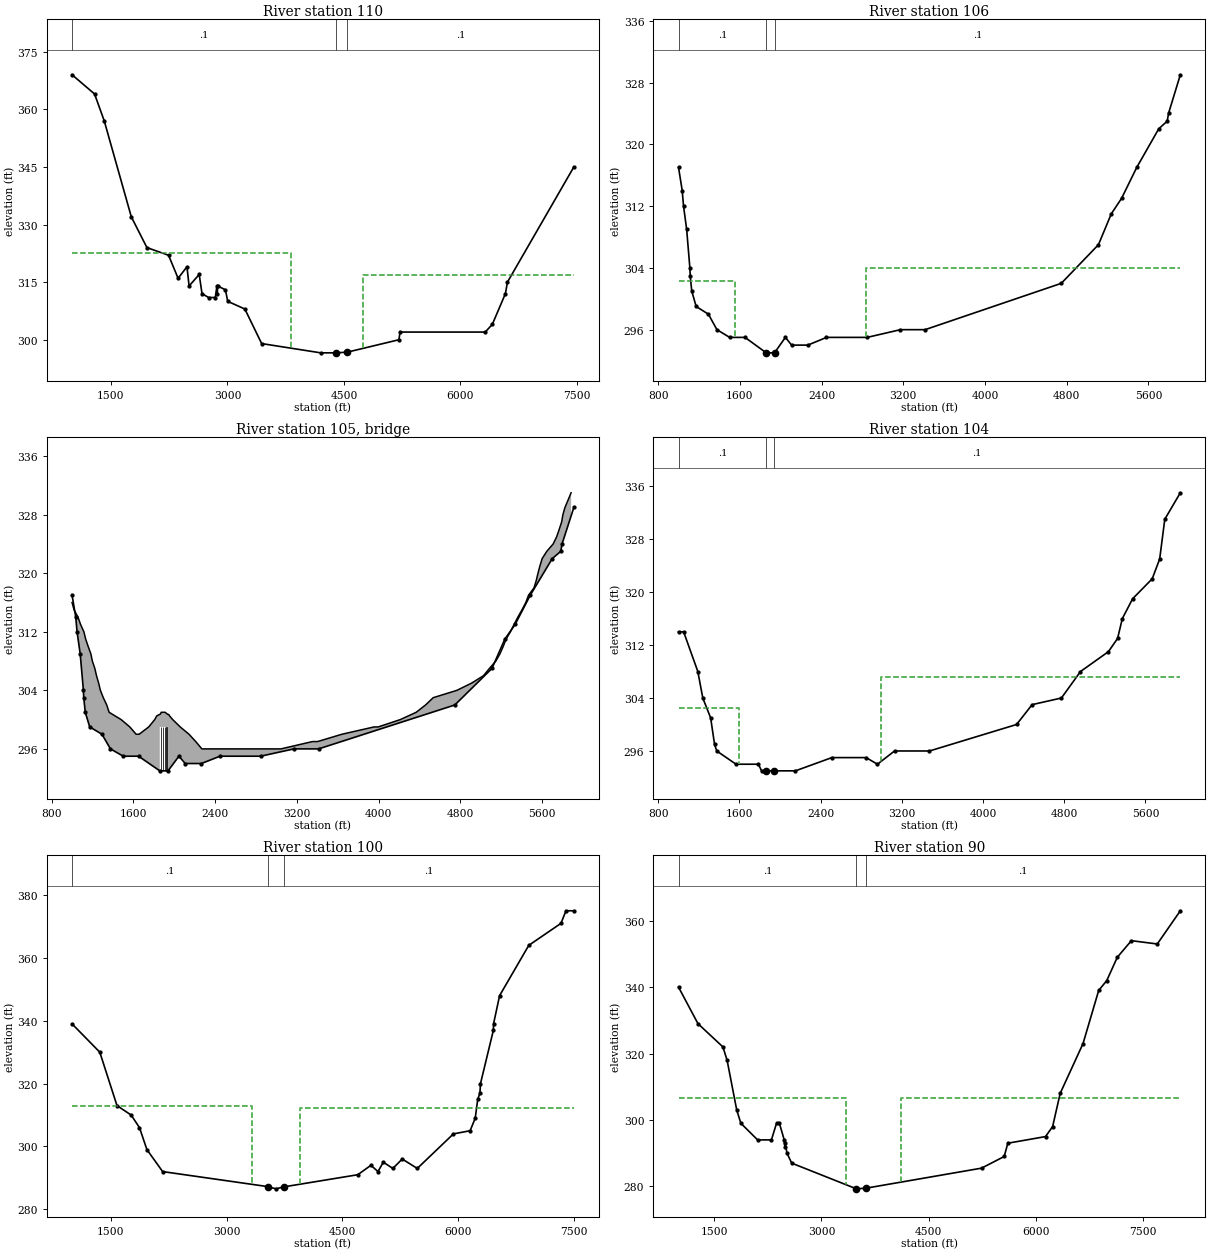
Type RM Length L Ch R = 1 ,110     ,3371.42,5655.65,3501.29
#Sta/Elev= 30
    1000     369 1289.64     364 1414.19     357 1762.81     332 1963.74     324
 2242.34     322 2365.03     316 2479.34     319 2506.71     314 2636.92     317
    2673     312 2757.57     311 2844.38     311 2864.95     314  2869.8     312
 2874.06     314 2975.09     313 3003.73     310 3224.62     308    3441     299
 4201.02  296.59 4392.64  296.59 4541.69  296.76 5208.14     300 5222.93     302
 6319.41     302 6410.74     304 6579.27     312 6605.43     315 7460.68     345
#Mann= 3 , 0 , 0
    1000      .1       0 4392.64     .05       0 4541.69      .1       0
#XS Ineff= 2 , 0
         3823.39  322.71 4742.24          316.88
Permanent Ineff=
       F       F
Bank Sta=4392.64,4541.69
XS Rating Curve= 0
Exp/Cntr=.5,.3

Type RM Length L Ch R = 1 ,106     ,47,47,47
#Sta/Elev= 30
    1000     317 1036.11     314 1048.82     312 1079.39     309 1110.97     304
 1114.17     303 1129.28     301 1172.63     299 1292.74     298 1375.65     296
 1500.61     295 1650.91     295  1858.5     293  1939.5     293  2046.2     295
 2107.16     294 2266.17     294 2448.44     295 2846.54     295 3172.47     296
 3413.83     296 4747.17     302 5110.85     307 5236.75     311  5337.2     313
  5485.5     317 5700.88     322 5784.33     323 5796.85     324 5912.43     329
#Mann= 3 , 0 , 0
    1000      .1       0  1858.5     .05       0  1939.5      .1       0
#XS Ineff= 2 , 0
       0 1548.93  302.31 2837.71       0  303.93
Permanent Ineff=
       F       F
Bank Sta=1858.5,1939.5
XS Rating Curve= 0
Exp/Cntr=.5,.3

Type RM Length L Ch R = 3 ,105     ,,,
Bridge Culvert--1,0,-1,-1, 0
Deck Dist Width WeirC Skew NumUp NumDn MinLoCord MaxHiCord MaxSubmerge Is_Ogee
25,21.2,2.6,0, 82, 82, , , .95, 0, 1.5,1.5,,
    1000 1019.34 1058.05 1083.42 1115.78 1133.24 1157.62 1183.66 1198.65 1222.77
 1239.31 1259.98 1277.37  1305.7 1339.41 1362.98 1480.84 1565.26 1626.92 1656.62
 1750.23    1809 1828.38  1854.5  1858.5 1866.69 1872.31 1882.24  1892.4 1897.36
  1903.4 1905.01 1911.55 1928.69  1939.5 1947.19    1955 1985.49  2058.8    2145
 2210.85 2270.62 3044.57 3353.49 3393.39 3403.03 3641.27 3955.89 3980.99  3996.9
 4212.24 4368.83 4460.36 4535.59 4767.16 4912.89 5027.35 5086.25 5148.63 5189.15
 5220.85 5248.67 5291.27 5326.85 5363.88 5404.47 5441.94 5468.68 5521.84 5544.07
 5560.96  5580.1 5601.83 5647.44 5709.61 5744.36 5769.05 5792.45    5805 5825.37
 5855.62 5885.48
     316     315     314     313     312     311     310     309     308     307
     306     305     304     303     302     301     300     299     298     298
     299     300   300.5   300.7   300.7   300.8     301     301     301     301
     301     301     301   300.8   300.7   300.7   300.5     300     299     298
     297     296     296     297     297     297     298     299     299     299
     300     301     302     303     304     305     306     307     308     309
     310     311     312     313     314     315     316     317     318     319
     320     321     322     323     324     325     326     327     328     329
     330     331
                                                                                
                                                                                
                                     299     299     299     299     299     299
     299     299     299     299     299
                                                                                
                                                                                
                                                                                
                                                                                
                
    1000 1019.34 1058.05 1083.42 1115.78 1133.24 1157.62 1183.66 1198.65 1222.77
 1239.31 1259.98 1277.37  1305.7 1339.41 1362.98 1480.84 1565.26 1626.92 1656.62
 1750.23    1809 1828.38  1854.5  1858.5 1866.69 1872.31 1882.24  1892.4 1897.36
  1903.4 1905.01 1911.55 1928.69  1939.5 1947.19    1955 1985.49  2058.8    2145
 2210.85 2270.62 3044.57 3353.49 3393.39 3403.03 3641.27 3955.89 3980.99  3996.9
 4212.24 4368.83 4460.36 4535.59 4767.16 4912.89 5027.35 5086.25 5148.63 5189.15
 5220.85 5248.67 5291.27 5326.85 5363.88 5404.47 5441.94 5468.68 5521.84 5544.07
 5560.96  5580.1 5601.83 5647.44 5709.61 5744.36 5769.05 5792.45    5805 5825.37
 5855.62 5885.48
     316     315     314     313     312     311     310     309     308     307
     306     305     304     303     302     301     300     299     298     298
     299     300   300.5   300.7   300.7   300.8     301     301     301     301
     301     301     301   300.8   300.7   300.7   300.5     300     299     298
     297     296     296     297     297     297     298     299     299     299
     300     301     302     303     304     305     306     307     308     309
     310     311     312     313     314     315     316     317     318     319
     320     321     322     323     324     325     326     327     328     329
     330     331
                                                                                
                                                                                
                                     299     299     299     299     299     299
     299     299     299     299     299
                                                                                
                                                                                
                                                                                
                                                                                
                
Pier Skew, UpSta & Num, DnSta & Num=  ,1874.5, 2 ,1874.5, 2 , 0 , 0 , 0 ,,
       2       2
     285     299
       2       2
     284     299
Pier Skew, UpSta & Num, DnSta & Num=  ,1890.08, 2 ,1890.08, 2 , 0 , 0 , 0 ,,
       2       2
     285     299
       2       2
     284     299
Pier Skew, UpSta & Num, DnSta & Num=  ,1906.83, 2 ,1906.83, 2 , 0 , 0 , 0 ,,
       2       2
     285     299
       2       2
     284     299
Pier Skew, UpSta & Num, DnSta & Num=  ,1924.08, 2 ,1924.08, 2 , 0 , 0 , 0 ,,
       2       2
     285     299
       2       2
     284     299
BR Coef= 1 , 0 , 1 ,1.25, 0 ,,,.8,-1,1.2,0,
WSPro=,,,, 1 ,,,, 0 ,,,, 0 ,,,,-1 ,-1 ,-1 , 0 , 0 , 0 , 0 , 0
BC Design=,, 0 ,, 0 ,,,,,,

Type RM Length L Ch R = 1 ,104     ,3034.15,4684.65,2954.6
#Sta/Elev= 30
    1000     314 1050.18     314 1190.05     308 1239.01     304 1316.34     301
 1354.87     297 1376.57     296 1566.15     294 1786.49     294 1818.06     293
 1863.67     293  1939.5     293 2151.43     293 2510.44     295  2847.6     295
 2959.49     294 3127.99     296 3472.19     296 4329.82     300 4483.29     303
 4771.67     304 4959.59     308 5234.78     311    5325     313 5371.96     316
 5473.48     319 5665.95     322  5739.7     325 5789.98     331 5943.09     335
#Mann= 3 , 0 , 0
    1000      .1       0 1863.67     .05       0  1939.5      .1       0
#XS Ineff= 2 , 0
       0 1596.66  302.55 2992.84       0  307.21
Permanent Ineff=
       F       F
Bank Sta=1863.67,1939.5
XS Rating Curve= 0
Exp/Cntr=.5,.3

Type RM Length L Ch R = 1 ,100     ,6049.63,10036.8,6010.98
#Sta/Elev= 30
    1000     339 1358.98     330  1581.6     313 1764.54     310 1872.82     306
 1968.94     299  2172.9     292 3531.48  287.23 3640.01  286.51  3740.2  287.13
 4699.23     291 4869.83     294  4961.2     292 5030.19     295  5153.5     293
 5275.18     296  5469.9     293 5938.02     304 6154.16     305 6220.32     309
 6252.76     315 6281.32     317 6288.46     320 6455.45     337 6457.33     339
  6535.9     348 6913.72     364 7330.66     371 7395.23     375 7497.41     375
#Mann= 3 , 0 , 0
    1000      .1       0 3531.48     .05       0  3740.2      .1       0
#XS Ineff= 2 , 0
         3333.33  313.02 3957.04          312.39
Permanent Ineff=
       F       F
Bank Sta=3531.48,3740.2
XS Rating Curve= 0
Exp/Cntr=.3,.1

Type RM Length L Ch R = 1 ,90      ,5047.15,9725.89,4998.21
#Sta/Elev= 30
    1000     340 1272.14     329  1621.1     322 1679.67     318 1814.41     303
 1872.72     299 2106.97     294 2300.31     294 2371.59     299 2411.83     299
 2479.34     294 2488.63     292  2491.1     293 2518.46     290 2583.98     287
  3490.1  279.26 3626.99  279.47 5241.61  285.49  5558.4     289 5609.41     293
 6137.03     295 6236.13     298 6342.05     308 6661.82     323 6881.15     339
 6994.73     342 7141.62     349 7338.85     354 7701.23     353 8023.86     363
#Mann= 3 , 0 , 0
    1000      .1       0  3490.1     .05       0 3626.99      .1       0
#XS Ineff= 2 , 0
         3348.45  306.64 4112.17          306.64
Permanent Ineff=
       F       F
Bank Sta=3490.1,3626.99
XS Rating Curve= 0
Exp/Cntr=.3,.1

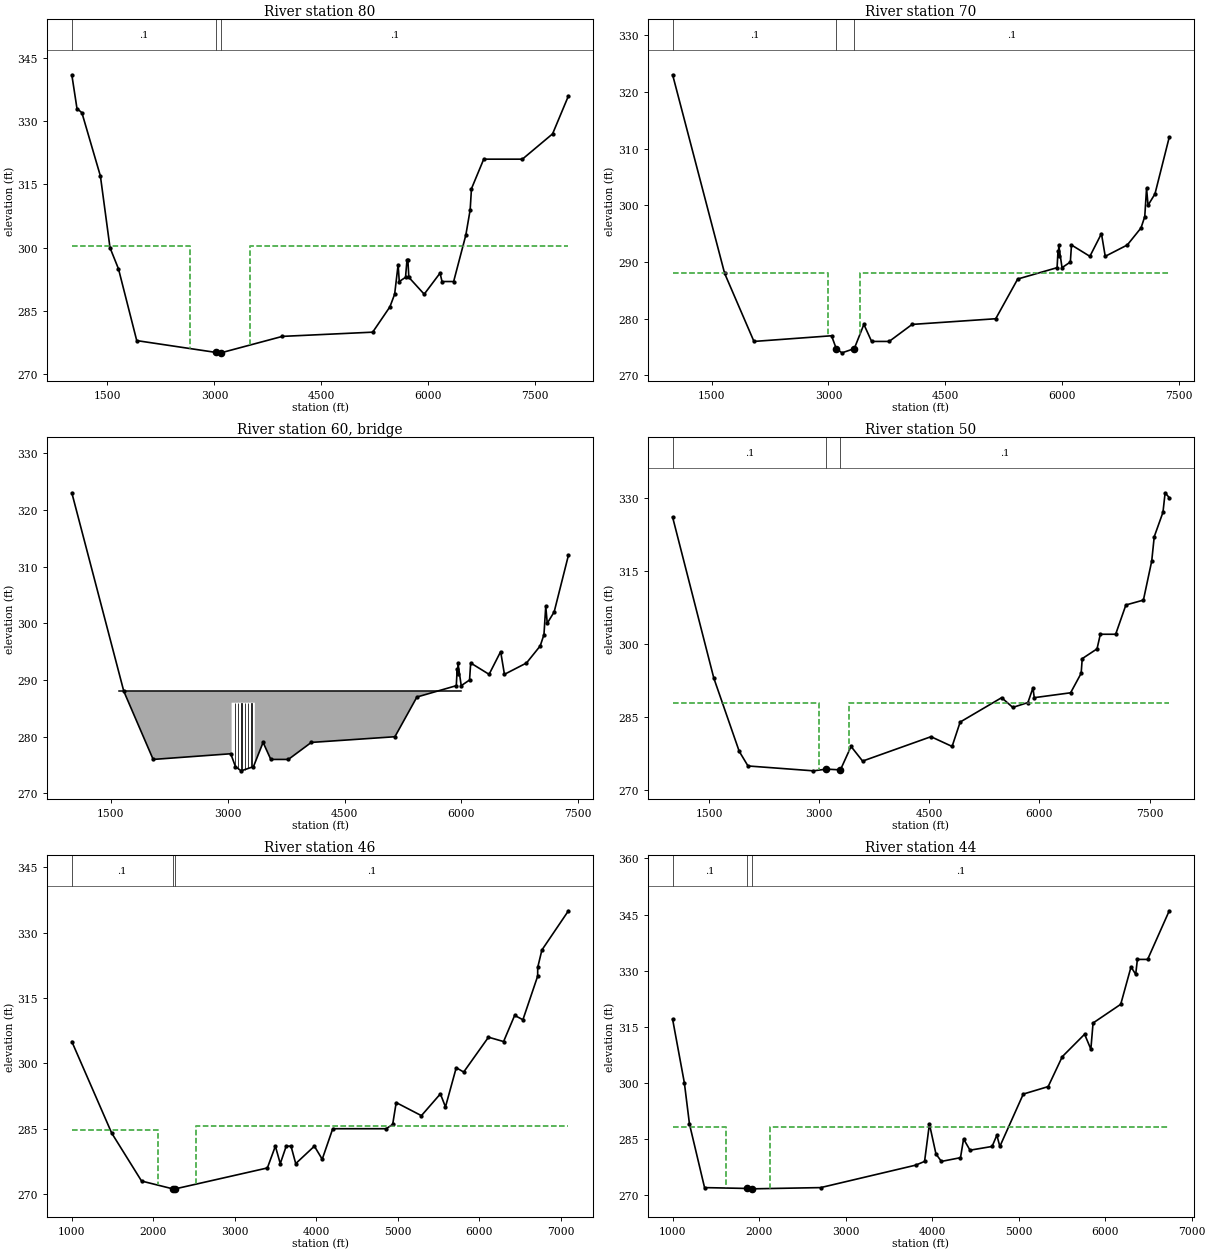
Type RM Length L Ch R = 1 ,80      ,3016.14,4711.29,2866.36
#Sta/Elev= 30
    1000     341 1072.45     333 1141.54     332 1401.06     317 1535.86     300
 1654.68     295 1910.69     278  3016.9  275.21 3090.55   275.1 3953.73     279
 5220.06     280 5461.55     286 5528.14     289 5576.77     296 5592.93     292
  5680.7     293  5700.5     297 5714.06     297 5727.07     293 5942.55     289
 6164.94     294 6192.63     292 6355.48     292 6526.37     303 6587.39     309
 6605.44     314 6777.46     321 7319.62     321 7743.24     327 7965.83     336
#Mann= 3 , 0 , 0
    1000      .1       0  3016.9     .05       0 3090.55      .1       0
#XS Ineff= 2 , 0
         2653.94  300.45 3505.97          300.45
Permanent Ineff=
       F       F
Bank Sta=3016.9,3090.55
XS Rating Curve= 0
Exp/Cntr=.5,.3

Type RM Length L Ch R = 1 ,70      ,106.48,106.48,106.48
#Sta/Elev= 30
    1000     323 1667.56     288 2044.12     276 3039.74     277 3100.55  274.73
 3173.46  273.99 3331.43  274.73 3454.98     279 3554.04     276 3779.51     276
 4073.85     279 5146.92     280 5429.26     287 5934.71     289 5946.51     292
 5954.62     291 5955.81     293 5998.01     289 6104.91     290  6119.4     293
 6355.59     291 6503.96     295 6552.79     291 6835.72     293 7011.66     296
 7059.97     298 7083.05     303 7102.09     300 7190.85     302 7374.28     312
#Mann= 3 , 0 , 0
    1000      .1       0 3100.55     .05       0 3331.43      .1       0
#XS Ineff= 2 , 0
            3000     288    3400             288
Permanent Ineff=
       F       F
Bank Sta=3100.55,3331.43
XS Rating Curve= 0
Exp/Cntr=.5,.3

Type RM Length L Ch R = 3 ,60      ,,,
Bridge Culvert--1,0,-1,-1, 0
Deck Dist Width WeirC Skew NumUp NumDn MinLoCord MaxHiCord MaxSubmerge Is_Ogee
25,28.1,2.6,0, 6, 6, , , .95, 0, 1.5,1.5,,
    1600 3051.25 3051.25 3348.92 3348.92    6000
     288     288     288     288     288     288
     270     270     286     286     270     270
    1600 3051.25 3051.25 3348.92 3348.92    6000
     288     288     288     288     288     288
     270     270     286     286     270     270
Pier Skew, UpSta & Num, DnSta & Num=  ,3093.75, 2 ,3093.75, 2 , 0 , 0 , 0 ,,
       2       2
     270     286
       2       2
     270     286
Pier Skew, UpSta & Num, DnSta & Num=  ,3136.25, 2 ,3136.25, 2 , 0 , 0 , 0 ,,
       2       2
     274     286
       2       2
     274     286
Pier Skew, UpSta & Num, DnSta & Num=  ,3178.75, 2 ,3178.75, 2 , 0 , 0 , 0 ,,
       2       2
     270     286
       2       2
     270     286
Pier Skew, UpSta & Num, DnSta & Num=  ,3221.25, 2 ,3221.25, 2 , 0 , 0 , 0 ,,
       2       2
     270     286
       2       2
     270     286
Pier Skew, UpSta & Num, DnSta & Num=  ,3263.92, 2 ,3263.92, 2 , 0 , 0 , 0 ,,
       2       2
     270     286
       2       2
     270     286
Pier Skew, UpSta & Num, DnSta & Num=  ,3306.25, 2 ,3306.25, 2 , 0 , 0 , 0 ,,
       2       2
     270     286
       2       2
     270     286
BR Coef= 1 , 0 , 1 ,1.25, 0 ,,,.8,0,1.2,0,
WSPro=,,,, 1 ,,,, 0 ,,,, 0 ,,,,-1 ,-1 ,-1 , 0 , 0 , 0 , 0 , 0
BC Design=,, 0 ,, 0 ,,,,,,

Type RM Length L Ch R = 1 ,50      ,1099.91,2433.03,1064.03
#Sta/Elev= 30
    1000     326 1561.68     293 1907.74     278 2027.26     275  2919.3     274
  3095.1  274.35 3287.21   274.2 3432.01     279 3589.56     276 4521.52     281
 4809.04     279 4918.97     284 5484.37     289 5636.28     287 5842.42     288
 5911.01     291  5928.8     289 6424.38     290 6568.24     294 6582.63     297
 6784.29     299 6829.49     302 7038.25     302 7177.64     308 7416.44     309
 7529.77     317 7564.18     322 7683.03     327 7712.43     331 7768.71     330
#Mann= 3 , 0 , 0
    1000      .1       0  3095.1     .05       0 3287.21      .1       0
#XS Ineff= 2 , 0
            3000     288    3400             288
Permanent Ineff=
       F       F
Bank Sta=3095.1,3287.21
XS Rating Curve= 0
Exp/Cntr=.5,.3

Type RM Length L Ch R = 1 ,46      ,1092.45,1709.16,1116.3
#Sta/Elev= 30
    1000     305 1489.68     284 1856.25     273 2238.83  271.21 2271.13  271.21
 3400.85     276 3498.88     281 3559.18     277  3632.2     281 3691.21     281
 3748.89     277 3977.92     281 4074.07     278 4203.28     285 4859.47     285
 4939.14     286 4982.28     291 5291.91     288 5524.87     293  5587.2     290
 5719.45     299 5810.78     298 6115.18     306 6300.53     305 6436.68     311
 6537.83     310 6718.93     320 6719.65     322 6770.88     326 7096.96     335
#Mann= 3 , 0 , 0
    1000      .1       0 2238.83     .05       0 2271.13      .1       0
#XS Ineff= 2 , 0
         2052.51  284.74 2520.29          285.59
Permanent Ineff=
       F       F
Bank Sta=2238.83,2271.13
XS Rating Curve= 0
Exp/Cntr=.5,.3

Type RM Length L Ch R = 1 ,44      ,1311.47,2198.07,1269.34
#Sta/Elev= 30
    1000     317 1135.86     300  1194.8     289  1369.3     272 1864.38  271.77
 1912.47  271.67  2711.4     272 3809.49     278 3912.61     279 3968.53     289
 4044.16     281 4106.96     279 4327.78     280 4363.45     285 4437.96     282
 4692.97     283 4748.12     286 4782.71     283 5053.55     297 5341.28     299
 5504.28     307 5762.57     313 5834.83     309 5860.16     316 6179.98     321
 6299.13     331 6353.13     329  6372.7     333 6491.08     333 6740.95     346
#Mann= 3 , 0 , 0
    1000      .1       0 1864.38     .05       0 1912.47      .1       0
#XS Ineff= 2 , 0
         1615.75  288.14 2131.26          288.14
Permanent Ineff=
       F       F
Bank Sta=1864.38,1912.47
XS Rating Curve= 0
Exp/Cntr=.5,.3

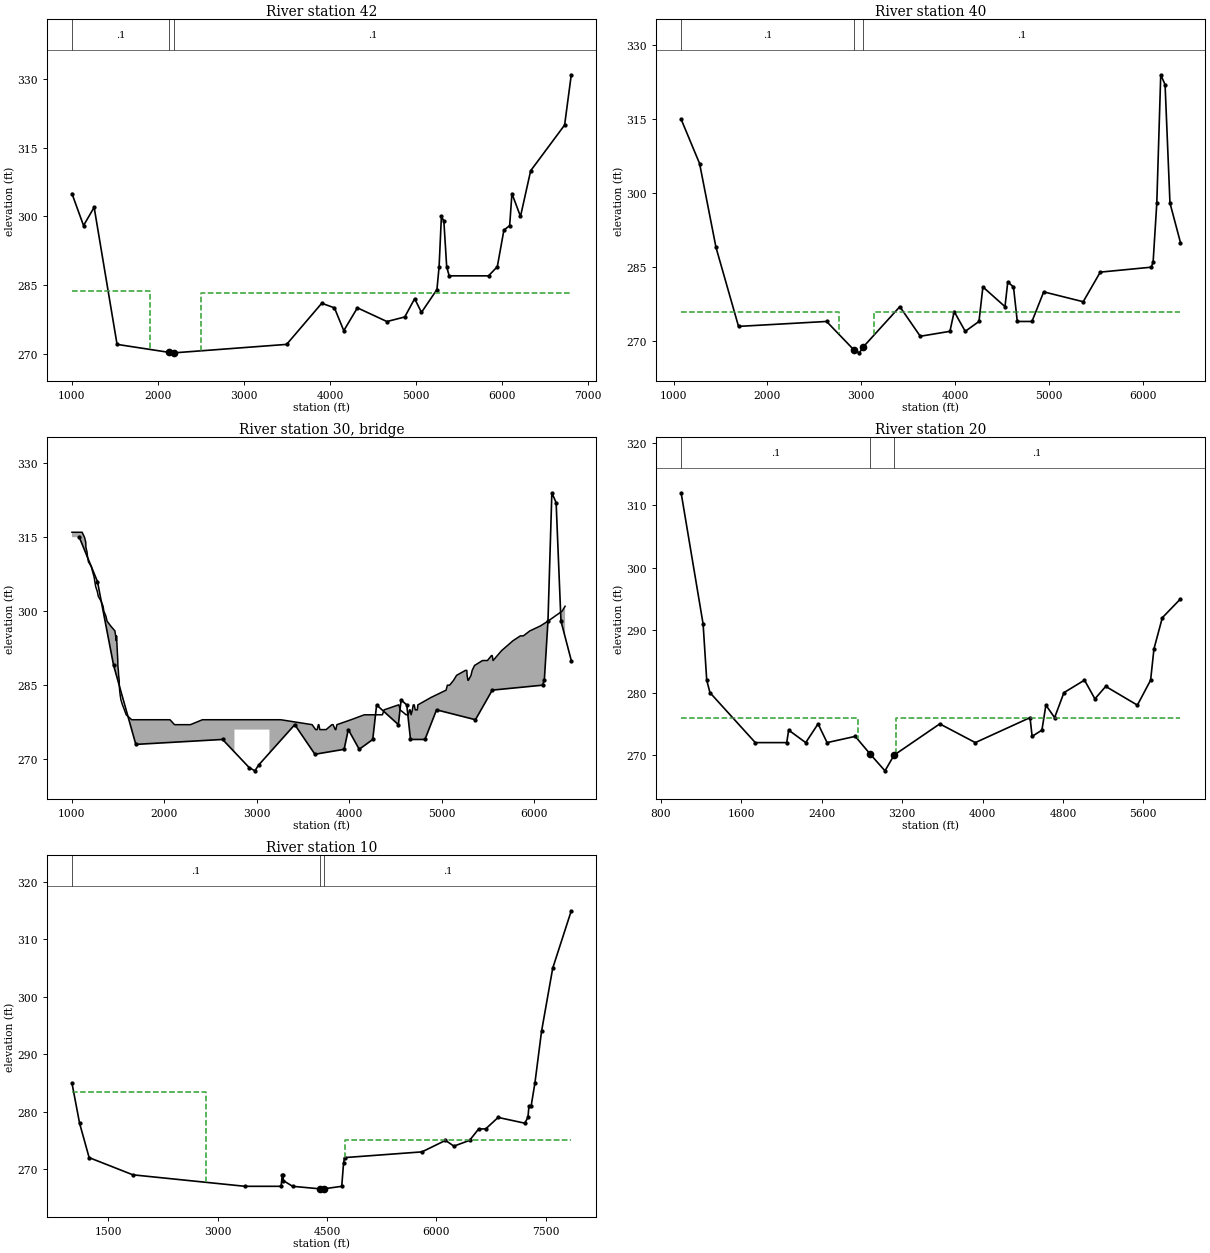
Type RM Length L Ch R = 1 ,42      ,1210.06,1585.73,1200.64
#Sta/Elev= 30
    1000     305 1134.82     298 1258.12     302 1524.65     272 2133.86  270.24
 2188.17  270.15 3496.66     272 3905.01     281 4052.45     280 4161.15     275
 4319.59     280 4662.77     277 4870.29     278 4985.45     282 5064.64     279
 5244.59     284  5269.7     289 5296.43     300 5324.97     299 5357.99     289
 5386.79     287 5844.53     287  5946.6     289 6023.22     297 6090.35     298
 6116.78     305 6216.26     300 6334.59     310 6729.23     320 6806.87     331
#Mann= 3 , 0 , 0
    1000      .1       0 2133.86     .05       0 2188.17      .1       0
#XS Ineff= 2 , 0
         1902.15   283.6 2503.58          283.32
Permanent Ineff=
       F       F
Bank Sta=2133.86,2188.17
XS Rating Curve= 0
Exp/Cntr=.5,.3

Type RM Length L Ch R = 1 ,40      ,79.63,79.63,79.63
#Sta/Elev= 30
    1079     315  1276.1     306 1451.03     289 1691.21     273 2630.01     274
 2917.73  268.31 2980.17  267.64 3019.09  268.79 3411.46     277 3629.39     271
 3945.53     272  3990.8     276 4108.91     272 4255.36     274 4297.16     281
 4532.76     277 4562.24     282 4623.43     281 4663.72     274 4820.41     274
 4945.64     280 5366.63     278 5548.78     284 6092.65     285 6112.16     286
 6151.52     298 6193.57     324 6239.74     322    6292     298 6403.74     290
#Mann= 3 , 0 , 0
    1079      .1       0 2917.73     .05       0 3019.09      .1       0
#XS Ineff= 2 , 0
       0    2758     276    3137       0     276
Permanent Ineff=
       F       F
Bank Sta=2917.73,3019.09
XS Rating Curve= 0
Exp/Cntr=.5,.3

Type RM Length L Ch R = 3 ,30      ,,,
Bridge Culvert--1,0,-1,-1, 0
Deck Dist Width WeirC Skew NumUp NumDn MinLoCord MaxHiCord MaxSubmerge Is_Ogee
20,32,2.6,0, 147, 147, , , .95, 0, 0,0,,
    1000    1110  1135.7 1149.31 1150.68 1163.18 1168.83 1178.61 1210.84 1223.75
 1239.02 1248.32 1256.65 1274.39  1285.4 1316.03 1336.79 1345.34  1367.6 1379.74
 1419.33 1465.16 1480.19 1482.46 1487.91 1490.83 1493.09 1496.05  1496.9 1502.19
 1505.38 1511.38  1512.4 1515.92 1521.79 1530.42 1547.01 1567.78 1586.98 1646.78
 1684.91 1716.15    1765 1839.54 1919.06 1941.96 1966.88 2036.39 2050.49    2061
 2110.06 2113.74 2159.83 2170.82 2174.05 2177.34 2181.99 2191.11 2202.08 2218.82
 2221.73  2225.7 2231.87 2281.81 2412.51 2419.39 2758.86 2766.93 2771.16 2775.39
    2776  2776.9 2784.26 2940.15 2947.69    3005 3137.44 3145.25 3253.84 3260.08
 3599.39 3636.81  3653.7 3666.76    3672 3682.72 3750.75 3813.36 3825.88 3849.67
 3856.08 3867.21 4020.25 4163.66 4211.12 4231.71 4357.71 4360.11 4377.62 4532.62
 4538.46 4551.44 4616.04 4639.75 4652.75 4660.05 4669.99 4670.55 4683.91 4693.27
 4704.37 4714.97 4724.81 4737.81 4743.03 4884.06 5049.25 5062.57 5064.49 5086.65
 5130.18 5162.52 5258.24 5273.23 5276.38 5285.16 5290.25  5318.7 5331.18 5356.93
 5443.48 5465.38  5496.4 5539.73 5548.27 5557.31 5649.01 5771.94 5853.06 5867.53
 5885.34 5954.36 6068.32 6153.02 6228.51 6304.27 6336.87
     316     316     315     314     313     312     311     310     309     308
     307     306     305     304     303     302     301     300     299     298
     297     296     294     295     293     292     291     290     289     288
     287     286     285     284     283     282     281     280     279     278
     278     278     278     278     278     278     278     278     278     278
     277     277     277     277     277     277     277     277     277     277
     277     277     277     277     278     278     278     278     278     278
     278     278     278     278     278     278     278     278     278     278
     277     276     276     277     277     276     276     277     277     276
     276     277     278     279     279     279     279     279     280     281
     281     280     279     279     280     280     279     279     280     281
     281     280     280     280     281   282.5     284     285     285     285
     286     287     288     288     287     286     286     287     288     289
     290     290     290     291     291     290     292     294     295     295
     295     296     297     298     299     300     301
                                                                                
                                                                                
                                                                                
                                                                                
                                                                                
                                                                                
                                                     276     276     276     276
     276     276     276     276     276     276     276
                                                                                
                                                                                
                                                                                
                                                                                
                                                                                
                                                                                
                                                        
    1000    1110  1135.7 1149.31 1150.68 1163.18 1168.83 1178.61 1210.84 1223.75
 1239.02 1248.32 1256.65 1274.39  1285.4 1316.03 1336.79 1345.34  1367.6 1379.74
 1419.33 1465.16 1480.19 1482.46 1487.91 1490.83 1493.09 1496.05  1496.9 1502.19
 1505.38 1511.38  1512.4 1515.92 1521.79 1530.42 1547.01 1567.78 1586.98 1646.78
 1684.91 1716.15    1765 1839.54 1919.06 1941.96 1966.88 2036.39 2050.49    2061
 2110.06 2113.74 2159.83 2170.82 2174.05 2177.34 2181.99 2191.11 2202.08 2218.82
 2221.73  2225.7 2231.87 2281.81 2412.51 2419.39 2758.86 2766.93 2771.16 2775.39
    2776  2776.9 2784.26 2940.15 2947.69    3005 3137.44 3145.25 3253.84 3260.08
 3599.39 3636.81  3653.7 3666.76    3672 3682.72 3750.75 3813.36 3825.88 3849.67
 3856.08 3867.21 4020.25 4163.66 4211.12 4231.71 4357.71 4360.11 4377.62 4532.62
 4538.46 4551.44 4616.04 4639.75 4652.75 4660.05 4669.99 4670.55 4683.91 4693.27
 4704.37 4714.97 4724.81 4737.81 4743.03 4884.06 5049.25 5062.57 5064.49 5086.65
 5130.18 5162.52 5258.24 5273.23 5276.38 5285.16 5290.25  5318.7 5331.18 5356.93
 5443.48 5465.38  5496.4 5539.73 5548.27 5557.31 5649.01 5771.94 5853.06 5867.53
 5885.34 5954.36 6068.32 6153.02 6228.51 6304.27 6336.87
     316     316     315     314     313     312     311     310     309     308
     307     306     305     304     303     302     301     300     299     298
     297     296     294     295     293     292     291     290     289     288
     287     286     285     284     283     282     281     280     279     278
     278     278     278     278     278     278     278     278     278     278
     277     277     277     277     277     277     277     277     277     277
     277     277     277     277     278     278     278     278     278     278
     278     278     278     278     278     278     278     278     278     278
     277     276     276     277     277     276     276     277     277     276
     276     277     278     279     279     279     279     279     280     281
     281     280     279     279     280     280     279     279     280     281
     281     280     280     280     281   282.5     284     285     285     285
     286     287     288     288     287     286     286     287     288     289
     290     290     290     291     291     290     292     294     295     295
     295     296     297     298     299     300     301
                                                                                
                                                                                
                                                                                
                                                                                
                                                                                
                                                                                
                                                     276     276     276     276
     276     276     276     276     276     276     276
                                                                                
                                                                                
                                                                                
                                                                                
                                                                                
                                                                                
                                                        
BR Coef= 1 , 1 , 0 ,, 0 ,,,.8,0,1.2,0,
WSPro=,,,, 1 ,,,, 0 ,,,, 0 ,,,,-1 ,-1 ,-1 , 0 , 0 , 0 , 0 , 0
BC Design=,, 0 ,, 0 ,,,,,,

Type RM Length L Ch R = 1 ,20      ,1939.57,2948.19,2071.27
#Sta/Elev= 30
    1000     312 1218.83     291 1254.82     282 1287.12     280 1738.32     272
 2051.19     272 2070.43     274 2240.27     272 2363.18     275 2453.15     272
 2733.46     273    2880270.1977 3029.07  267.48    3120269.9978 3574.51     275
 3928.41     272 4472.85     276 4493.81     273 4591.29     274 4630.78     278
 4717.51     276 4810.25     280 5014.77     282 5118.78     279 5226.06     281
 5541.32     278 5673.14     282 5706.26     287 5789.69     292 5970.05     295
#Mann= 3 , 0 , 0
    1000      .1       0    2880     .05       0    3120      .1       0
#XS Ineff= 2 , 0
            2758     276    3137             276
Permanent Ineff=
       F       F
Bank Sta=2880,3120
XS Rating Curve= 0
Exp/Cntr=.5,.3

Type RM Length L Ch R = 1 ,10      ,,,
#Sta/Elev= 30
    1000     285 1104.57     278 1235.81     272 1836.49     269 3376.15     267
 3870.66     267 3886.91     269 3896.58     269 3900.61     268 4028.68     267
  4404.9  266.56 4454.49  266.56 4702.69     267 4727.55     271 4741.18     272
 5804.28     273 6126.65     275  6242.2     274 6456.96     275 6582.46     277
 6678.02     277 6849.33     279 7214.36     278 7258.58     279 7272.31     281
 7302.53     281 7354.23     285 7445.07     294 7598.42     305 7853.17     315
#Mann= 3 , 0 , 0
    1000      .1       0  4404.9     .05       0 4454.49      .1       0
#XS Ineff= 2 , 0
         2837.71  283.44    4745             275
Permanent Ineff=
       F       F
Bank Sta=4404.9,4454.49
XS Rating Curve= 0
Exp/Cntr=.5,.3

Chan Stop Cuts=-1