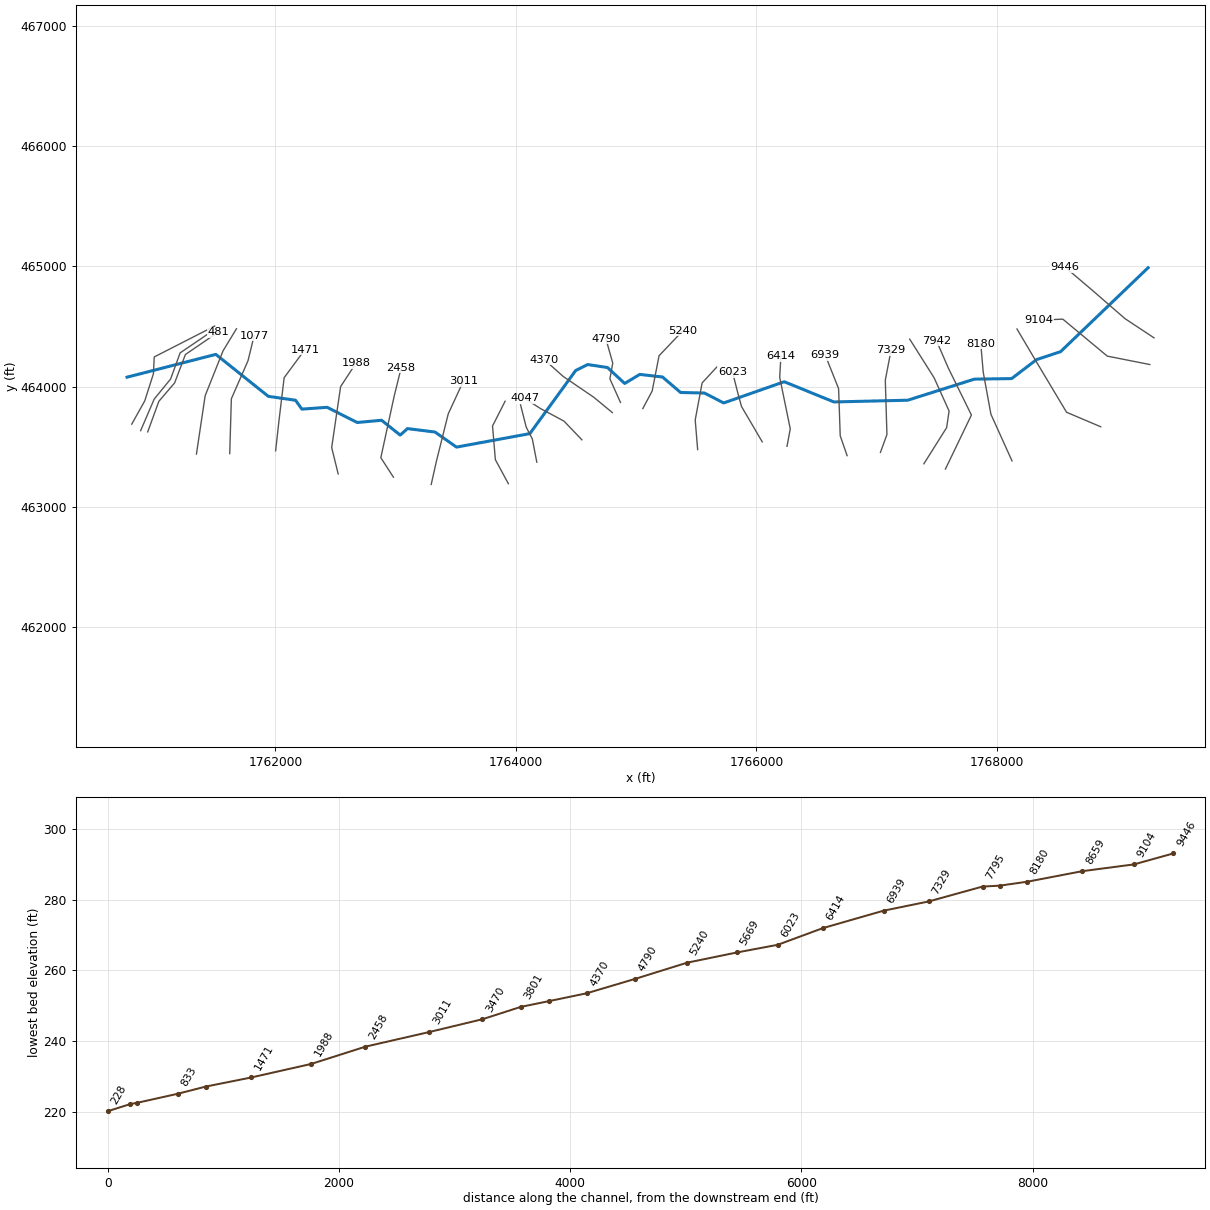
--- South Prong Cartledge Ck.prj (project) ---

Proj Title=South Prong Cartledge Creek Limited Detail Study
Current Plan=p01
Default Exp/Contr=0.3,0.1
English Units
Geom File=g01
Flow File=f01
Plan File=p01
Y Axis Title=Elevation
X Axis Title(PF)=Main Channel Distance
X Axis Title(XS)=Station
BEGIN DESCRIPTION:
South Prong Cartledge Creek
END DESCRIPTION:
DSS Export Rating Curves= 0
DSS Export Rating Curve Sorted= 0
DSS Export Volume Flow Curves= 0
DXF OffsetX= 0
DXF OffsetY= 0
DXF ScaleX= 1
DXF ScaleY= 10

--- South Prong Cartledge Ck.p01 (plan) ---

Plan Title=Floodway Run
Program Version=3.12
Short Identifier=Floodway
Geom File=g01
Flow File=f01
Subcritical Flow
K Sum by GR= 0
Std Step Tol= 0.01
Critical Tol= 0.01
Num of Std Step Trials= 20
Max Error Tol= 0.3
Flow Tol Ratio= 0.001
Split Flow NTrial= 30
Split Flow Tol= 0.02
Split Flow Ratio= 0.02
Log Output Level= 0
Friction Slope Method= 1
Unsteady Friction Slope Method= 2
Unsteady Bridges Friction Slope Method= 1
Parabolic Critical Depth
Global Vel Dist= 0 , 0 , 0
Global Log Level= 0
CheckData=True
Encroach Param=-1 ,30,30, 2
Encroach River=South Prong Cart
Encroach Reach=Reach-1
Encroach Node=9446
       1 4925.85  5035.1
Encroach Node=9104
       1 4902.24    5016
Encroach Node=8659
       1 4829.35  5036.1
Encroach Node=8180
       1  4759.3  5035.9
Encroach Node=7942
       1 4844.07  5037.2
Encroach Node=7795
       1 4844.07  5037.2
Encroach Node=7329
       1 4825.79    5024
Encroach Node=6939
       1  4840.2    5119
Encroach Node=6414
       1 4877.39  5036.8
Encroach Node=6023
       1  4972.5    5035
Encroach Node=5669
       1  4963.2  5036.8
Encroach Node=5240
       1  4920.5 5051.04
Encroach Node=4790
       1  4962.6    5031
Encroach Node=4370
       1 4906.73  5030.5
Encroach Node=4047
       1 4939.22  5037.4
Encroach Node=3801
       1    4968    5045
Encroach Node=3470
       1  4962.6  5037.4
Encroach Node=3011
       1 4906.36 5114.65
Encroach Node=2458
       1  4962.6  5037.4
Encroach Node=1988
       1 4930.93  5037.4
Encroach Node=1471
       1 4947.89  5037.4
Encroach Node=1077
       1 4868.73  5037.4
Encroach Node=833
       1    4850    5022
Encroach Node=481
       1    4920    5120
Encroach Node=423
       1    4920    5120
Encroach Node=228
       1    4920    5120
BEGIN DESCRIPTION:
Floodway Run
END DESCRIPTION:
Computation Interval=1HOUR
Output Interval=1HOUR
Run HTab= 0
Run UNet= 0
Run PostProcess= 0
UNET Theta= 1
UNET Theta Warmup= 1
UNET ZTol= 0.02
UNET ZSATol= 0.05
UNET MxIter= 20
UNET MaxInSteps= 0
UNET DtIC= 0
UNET DtMin= 0
UNET MaxCRTS= 20
UNET WFStab= 2
UNET SFStab= 1
UNET WFX= 1
UNET SFX= 1
UNET DSS MLevel= 4
UNET DZMax Abort= 100
UNET Convert EG Bridges=-1
UNET Use Existing IB Tables=-1
UNET Froude Reduction=False
UNET Froude Limit= 1
UNET Froude Power= 10
Instantaneous Interval=1HOUR
Write IC File= 0
Echo Input=False
Echo Output=False
Write Detailed= 0
Detailed Automatic Start=False, 10

--- South Prong Cartledge Ck.f01 (steady flow) ---

Flow Title=Floodway
Number of Profiles=2
Profile Names=100-year,100-FW
River Rch & RM= South Prong Cart,Reach-1,9446
    1680    1680
River Rch & RM= South Prong Cart,Reach-1,8180
    1828    1828
River Rch & RM= South Prong Cart,Reach-1,7329
    1999    1999
River Rch & RM= South Prong Cart,Reach-1,4790
    2183    2183
Boundary for River Rch & Prof#=South Prong Cart,Reach-1,1
Up Type=0
Dn Type=3
Dn Slope=0.01
Boundary for River Rch & Prof#=South Prong Cart,Reach-1,2
Up Type=0
Dn Type=1
Dn Known WS=229.61

--- South Prong Cartledge Ck.g01 (geometry) ---

Geom Title=Existing Conditions

River Reach=South Prong Cart,Reach-1
Reach XY= 30
      1769258.27       464989.11      1768530.35       464291.21
      1768330.23       464224.92      1768123.87       464067.33
      1767813.23       464062.65      1767258.84       463887.39
      1766645.44       463873.08      1766232.32       464041.19
      1765728.74       463864.72      1765568.64       463947.26
      1765370.33       463951.77      1765220.11       464080.53
      1765030.55       464101.99      1764905.36       464026.88
      1764762.29       464159.22      1764597.76       464184.26
      1764497.62       464134.18      1764116.56       463609.57
      1763506.86       463497.53      1763328.03       463622.71
      1763099.12       463651.32      1763038.31       463597.67
      1762883.35       463720.88      1762680.73       463702.12
      1762430.59       463828.44      1762220.46       463813.44
      1762167.93       463887.23      1761941.55       463919.75
      1761505.05       464268.70      1760766.44       464078.96

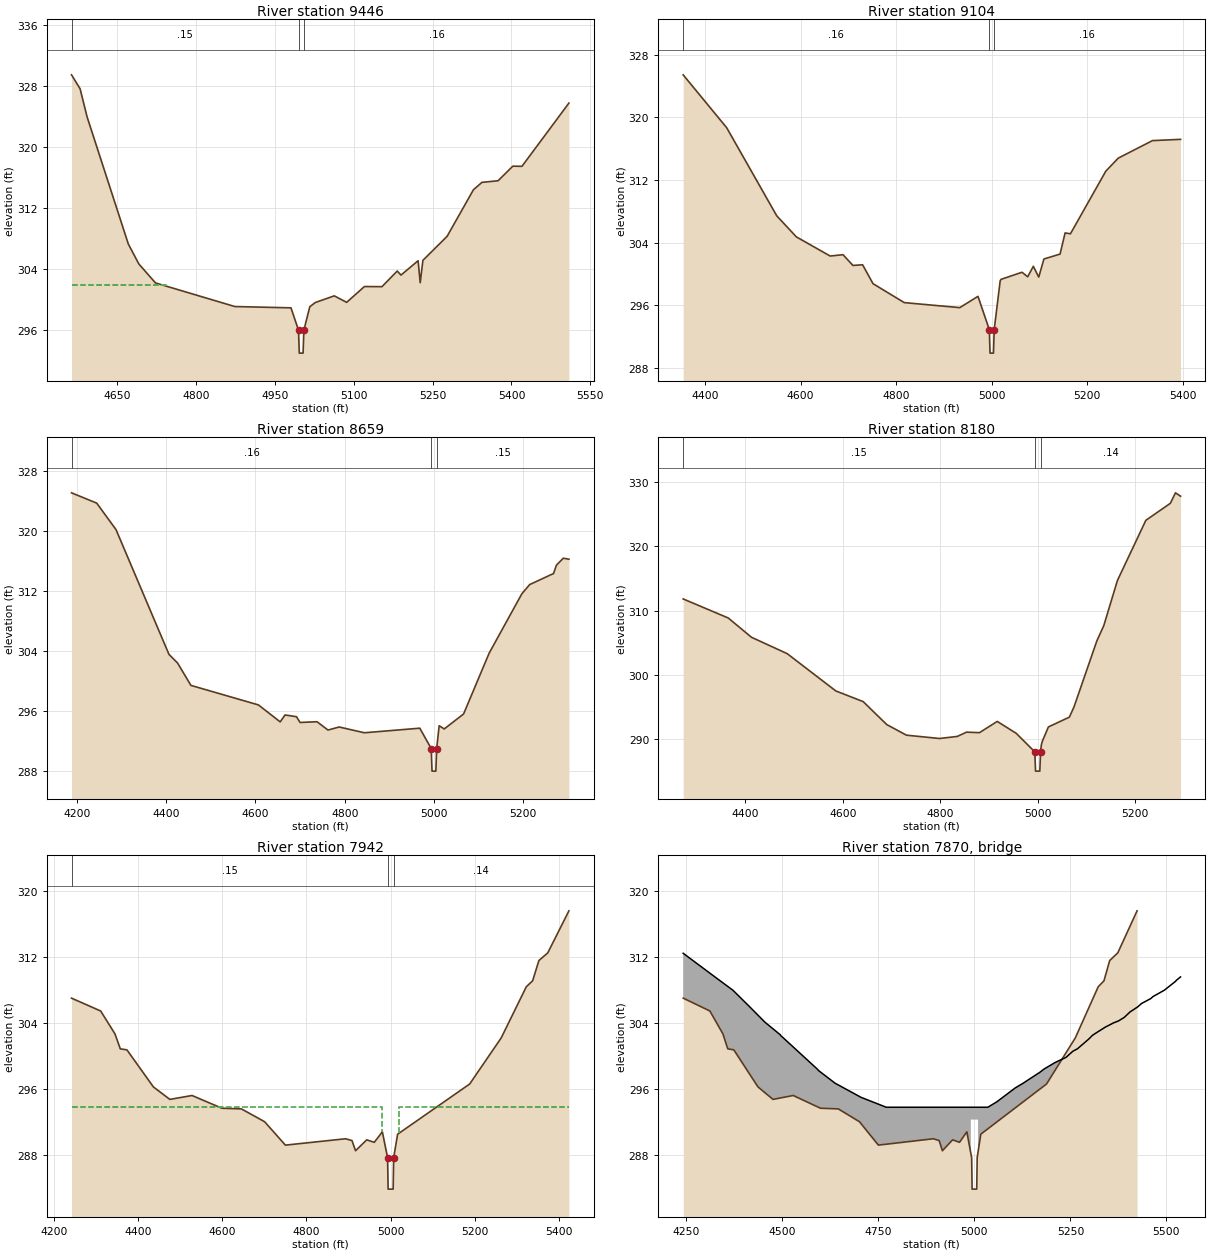
Type RM Length L Ch R = 1,9446,342,342,342
BEGIN DESCRIPTION:
South Prong Cartledge Creek 19.0
END DESCRIPTION:
XS GIS Cut Line= 4
      1769308.04       464406.02      1769066.82       464565.54
      1768802.20       464795.13      1768568.69       464993.61
#Sta/Elev= 30
  4563.2  329.43  4579.5  327.60  4592.9  323.90  4671.2  307.28  4691.2  304.67
  4722.9  302.18  4873.8  299.09  4980.6  298.92  4994.9  295.99  4996.4  292.99
  5003.6  292.99  5005.1  295.99  5016.4  299.07  5027.0  299.62  5062.9  300.49
  5086.5  299.64  5120.3  301.71  5153.6  301.69  5182.7  303.74  5189.8  303.21
  5222.4  305.09  5226.4  302.21  5231.5  305.14  5277.5  308.28  5327.7  314.39
  5343.8  315.35  5374.5  315.56  5402.5  317.47  5419.9  317.45  5509.2  325.73
#Mann=3,-1,0
  4563.2    0.15       0  4994.9    0.05       0  5005.1    0.16       0
#XS Ineff=2,0
    0.00 4743.10  301.96               0
Permanent Ineff=
       T       F
Bank Sta=4994.9,5005.1
XS Rating Curve= 0
Exp/Cntr=0.3,0.1

Type RM Length L Ch R = 1,9104,445,445,445
BEGIN DESCRIPTION:
South Prong Cartledge Creek 18.0
END DESCRIPTION:
XS GIS Cut Line= 4
      1769273.09       464184.18      1768918.94       464254.23
      1768549.26       464561.65      1768350.82       464553.87
#Sta/Elev= 30
  4354.5  325.43  4445.6  318.67  4550.3  307.42  4591.4  304.73  4662.0  302.29
  4688.9  302.46  4709.5  301.09  4729.9  301.17  4751.6  298.76  4817.0  296.34
  4933.1  295.70  4971.2  297.14  4994.9  292.89  4996.4  289.89  5003.6  289.89
  5005.1  292.89  5017.6  299.12  5019.4  299.31  5063.3  300.22  5075.1  299.64
  5087.0  300.98  5098.3  299.60  5109.1  301.91  5142.9  302.54  5153.4  305.24
  5164.6  305.13  5238.6  313.13  5264.6  314.79  5336.2  317.03  5394.9  317.19
#Mann=3,-1,0
  4354.5    0.16       0  4994.9    0.05       0  5005.1    0.16       0
Bank Sta=4994.9,5005.1
XS Rating Curve= 0
Exp/Cntr=0.3,0.1

Type RM Length L Ch R = 1,8659,479,479,479
BEGIN DESCRIPTION:
South Prong Cartledge Creek 17.0
END DESCRIPTION:
XS GIS Cut Line= 4
      1768864.47       463666.62      1768580.39       463787.26
      1768331.34       464203.64      1768167.91       464479.91
#Sta/Elev= 30
  4187.7  325.06  4244.1  323.69  4287.4  320.16  4406.1  303.54  4425.4  302.39
  4455.3  299.41  4606.6  296.81  4655.4  294.55  4666.2  295.47  4691.9  295.24
  4699.9  294.47  4738.0  294.57  4762.5  293.46  4787.5  293.87  4843.9  293.10
  4968.3  293.71  4993.9  290.99  4995.7  287.99  5004.3  287.99  5006.1  290.99
  5011.7  294.04  5023.1  293.61  5066.4  295.60  5123.8  303.71  5196.9  311.60
  5214.6  312.84  5268.0  314.31  5274.5  315.42  5289.9  316.35  5302.5  316.22
#Mann=3,-1,0
  4187.7    0.16       0  4993.9    0.05       0  5006.1    0.15       0
Bank Sta=4993.9,5006.1
XS Rating Curve= 0
Exp/Cntr=0.3,0.1

Type RM Length L Ch R = 1,8180,238,238,238
BEGIN DESCRIPTION:
South Prong Cartledge Creek 16.0
END DESCRIPTION:
XS GIS Cut Line= 4
      1768126.81       463382.47      1767951.17       463770.92
      1767886.98       464122.24      1767866.71       464358.73
#Sta/Elev= 30
  4272.4  311.81  4365.0  308.84  4412.6  305.84  4485.9  303.29  4585.6  297.49
  4641.9  295.82  4690.2  292.25  4730.6  290.60  4798.3  290.08  4834.9  290.40
  4854.0  291.07  4880.5  290.99  4917.0  292.74  4955.9  290.89  4994.1  288.00
  4995.6  285.00  5004.4  285.00  5005.9  288.00  5007.6  289.12  5009.7  289.68
  5022.0  291.88  5065.1  293.41  5074.6  295.01  5121.4  305.27  5135.6  307.64
  5163.7  314.69  5222.0  324.05  5272.2  326.69  5282.8  328.33  5293.2  327.81
#Mann=3,-1,0
  4272.4    0.15       0  4994.1    0.05       0  5005.9    0.14       0
Bank Sta=4994.1,5005.9
XS Rating Curve= 0
Exp/Cntr=0.5,0.3

Type RM Length L Ch R = 1,7942,147,147,147
BEGIN DESCRIPTION:
Sandy Ridge Road - US
END DESCRIPTION:
XS GIS Cut Line= 4
      1767572.82       463314.87      1767789.02       463764.16
      1767596.47       464156.02      1767498.52       464382.32
#Sta/Elev= 30
  4241.8  306.99  4311.0  305.44  4345.0  302.67  4357.7  300.86  4373.4  300.74
  4436.3  296.26  4475.4  294.75  4528.1  295.22  4599.2  293.68  4645.5  293.60
  4700.6  292.05  4749.9  289.22  4893.0  289.99  4908.2  289.77  4916.6  288.54
  4943.2  289.86  4961.2  289.56  4980.3  290.83  4992.8  287.70  4994.0  283.90
  5006.0  283.90  5007.2  287.70  5016.6  290.54  5187.8  296.61  5262.8  302.19
  5322.4  308.37  5337.4  309.09  5352.3  311.54  5373.4  312.47  5423.6  317.55
#Mann=3,-1,0
  4241.8    0.15       0  4992.8    0.05       0  5007.2    0.14       0
#XS Ineff=2,0
    0.00 4980.50  293.80 5019.50    0.00  293.80
Permanent Ineff=
       F       F
Bank Sta=4992.8,5007.2
XS Rating Curve= 0
Exp/Cntr=0.5,0.3

Type RM Length L Ch R =3,7870,,,
BEGIN DESCRIPTION:
Sandy Ridge Road - TOR
Structure ID: LDS_SPCAC_02
Approximate Survey Structure
END DESCRIPTION:
Bridge Culvert--1,0,-1,-1,0
Deck Dist Width WeirC Skew NumUp NumDn MinLoCord MaxHiCord MaxSubmerge Is_Ogee
61.5,21,3,,46,46,,,,0,1,1,,,
  4241.5  4329.1  4371.3  4413.8  4454.6  4494.7  4496.2  4499.4  4590.9  4594.3
  4637.0  4704.7  4770.4  4990.5  4990.5  5009.5  5009.5  5034.9  5057.8  5106.4
  5126.3  5167.4  5168.2  5182.2  5184.5  5210.1  5238.5  5256.3  5268.4  5298.6
  5307.2  5319.1  5341.0  5359.8  5361.7  5375.0  5390.4  5405.4  5425.1  5435.4
  5459.2  5465.0  5494.9  5524.1  5525.4  5536.8
  312.42  309.39  307.94  305.99  304.08  302.55  302.42  302.31  298.41  298.23
  296.71  295.00  293.80  293.80  293.80  293.80  293.80  293.80  294.44  296.14
  296.69  297.94  297.95  298.45  298.51  299.21  299.83  300.57  300.87  302.08
  302.49  302.85  303.49  303.94  303.99  304.23  304.67  305.33  305.93  306.35
  306.94  307.18  307.96  309.04  309.13  309.56
  263.90  263.90  263.90  263.90  263.90  263.90  263.90  263.90  263.90  263.90
  263.90  263.90  263.90  263.90  292.30  292.30  263.90  263.90  263.90  263.90
  263.90  263.90  263.90  263.90  263.90  263.90  263.90  263.90  263.90  263.90
  263.90  263.90  263.90  263.90  263.90  263.90  263.90  263.90  263.90  263.90
  263.90  263.90  263.90  263.90  263.90  263.90
  4241.5  4329.1  4371.3  4413.8  4454.6  4494.7  4496.2  4499.4  4590.9  4594.3
  4637.0  4704.7  4770.4  4990.5  4990.5  5009.5  5009.5  5034.9  5057.8  5106.4
  5126.3  5167.4  5168.2  5182.2  5184.5  5210.1  5238.5  5256.3  5268.4  5298.6
  5307.2  5319.1  5341.0  5359.8  5361.7  5375.0  5390.4  5405.4  5425.1  5435.4
  5459.2  5465.0  5494.9  5524.1  5525.4  5536.8
  312.42  309.39  307.94  305.99  304.08  302.55  302.42  302.31  298.41  298.23
  296.71  295.00  293.80  293.80  293.80  293.80  293.80  293.80  294.44  296.14
  296.69  297.94  297.95  298.45  298.51  299.21  299.83  300.57  300.87  302.08
  302.49  302.85  303.49  303.94  303.99  304.23  304.67  305.33  305.93  306.35
  306.94  307.18  307.96  309.04  309.13  309.56
  263.90  263.90  263.90  263.90  263.90  263.90  263.90  263.90  263.90  263.90
  263.90  263.90  263.90  263.90  292.30  292.30  263.90  263.90  263.90  263.90
  263.90  263.90  263.90  263.90  263.90  263.90  263.90  263.90  263.90  263.90
  263.90  263.90  263.90  263.90  263.90  263.90  263.90  263.90  263.90  263.90
  263.90  263.90  263.90  263.90  263.90  263.90
BR Coef=1,1,0,1.25,0,,,0.8,0,2,0,
WSPro=,,,, 1 ,,,, 0 ,,,, 0 ,,,,-1 ,-1 ,-1 , 0 , 0 , 0 , 0 , 0
BC Design=,,0,,0,,,,,,

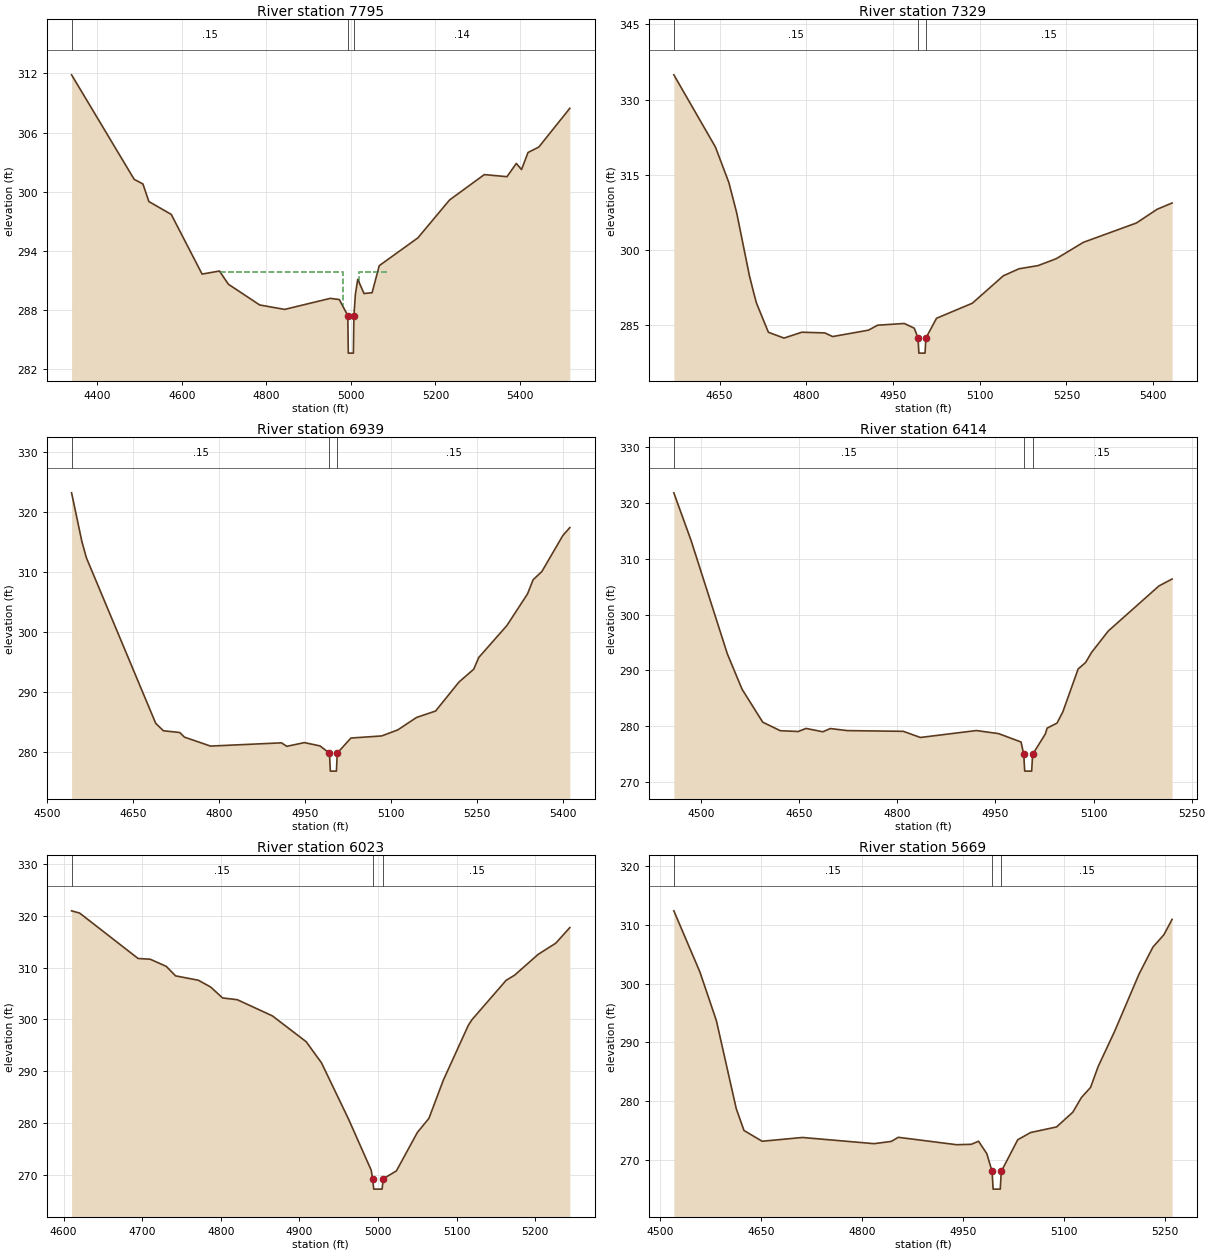
Type RM Length L Ch R = 1,7795,466,466,466
BEGIN DESCRIPTION:
Sandy Ridge Road - DS
END DESCRIPTION:
XS GIS Cut Line= 5
      1767393.80       463358.81      1767582.96       463659.44
      1767603.23       463797.94      1767478.24       464074.94
      1767275.56       464395.84
#Sta/Elev= 30
  4339.4  311.85  4487.5  301.26  4508.2  300.79  4522.2  299.01  4575.1  297.71
  4648.1  291.66  4689.2  291.97  4710.4  290.63  4784.4  288.53  4843.4  288.08
  4951.4  289.20  4972.7  289.08  4992.8  287.45  4994.0  283.65  5006.0  283.65
  5007.2  287.45  5010.8  289.62  5016.3  291.13  5031.2  289.69  5050.2  289.77
  5067.2  292.51  5158.6  295.33  5233.5  299.17  5315.7  301.74  5369.3  301.53
  5391.4  302.87  5403.7  302.25  5419.1  303.98  5444.6  304.53  5518.0  308.46
#Mann=3,-1,0
  4339.4    0.15       0  4992.8    0.05       0  5007.2    0.14       0
#XS Ineff=3,-1
 4689.30 4980.50  291.90 5019.50 5085.80  291.90 4634.10 4689.20  291.97
Permanent Ineff=
       F       F       F
Bank Sta=4992.8,5007.2
XS Rating Curve= 0
Exp/Cntr=0.5,0.3

Type RM Length L Ch R = 1,7329,390,390,390
BEGIN DESCRIPTION:
South Prong Cartledge Creek 15.0
END DESCRIPTION:
XS GIS Cut Line= 4
      1767032.35       463453.42      1767086.38       463602.01
      1767072.87       464054.67      1767120.17       464301.30
#Sta/Elev= 30
  4570.7  334.93  4642.7  320.53  4666.0  313.42  4679.5  307.39  4701.5  294.86
  4709.8  291.09  4713.7  289.42  4734.3  283.61  4761.3  282.45  4792.2  283.62
  4832.0  283.48  4845.5  282.75  4907.5  284.03  4923.3  285.02  4969.4  285.36
  4986.7  284.42  4993.2  282.45  4994.7  279.45  5005.3  279.45  5006.8  282.45
  5025.2  286.40  5087.2  289.40  5140.7  294.86  5167.7  296.26  5200.9  296.90
  5232.3  298.27  5279.3  301.54  5371.0  305.39  5407.1  308.14  5432.8  309.38
#Mann=3,-1,0
  4570.7    0.15       0  4993.2    0.05       0  5006.8    0.15       0
Bank Sta=4993.2,5006.8
XS Rating Curve= 0
Exp/Cntr=0.3,0.1

Type RM Length L Ch R = 1,6939,525,525,525
BEGIN DESCRIPTION:
South Prong Cartledge Creek 14.0
END DESCRIPTION:
XS GIS Cut Line= 4
      1766755.34       463426.33      1766697.90       463591.88
      1766684.39       463983.73      1766572.93       464264.07
#Sta/Elev= 30
  4543.4  323.19  4561.4  315.07  4569.3  312.36  4690.2  284.80  4703.6  283.57
  4732.0  283.28  4740.3  282.51  4785.7  281.02  4909.5  281.56  4918.8  280.98
  4949.5  281.60  4976.6  281.05  4993.2  279.85  4994.7  276.85  5005.3  276.85
  5006.8  279.85  5030.6  282.36  5084.3  282.71  5112.2  283.71  5145.1  285.79
  5178.3  286.86  5219.0  291.68  5244.7  293.81  5253.6  295.78  5302.6  301.09
  5338.6  306.36  5348.4  308.72  5363.7  310.10  5400.2  316.08  5412.4  317.40
#Mann=3,-1,0
  4543.4    0.15       0  4993.2    0.05       0  5006.8    0.15       0
Bank Sta=4993.2,5006.8
XS Rating Curve= 0
Exp/Cntr=0.3,0.1

Type RM Length L Ch R = 1,6414,391,391,391
BEGIN DESCRIPTION:
South Prong Cartledge Creek 13.0
END DESCRIPTION:
XS GIS Cut Line= 4
      1766255.36       463504.00      1766282.40       463649.31
      1766194.57       464078.32      1766204.70       464254.02
#Sta/Elev= 30
  4458.3  321.80  4484.7  313.25  4540.1  292.95  4562.6  286.61  4594.2  280.71
  4621.1  279.18  4648.5  279.04  4660.4  279.59  4686.1  278.99  4697.5  279.57
  4723.3  279.20  4809.1  279.07  4835.2  277.97  4920.9  279.21  4954.8  278.66
  4989.1  277.16  4993.2  274.94  4994.7  271.94  5005.3  271.94  5006.8  274.94
  5026.3  278.61  5028.9  279.64  5044.0  280.54  5052.8  282.51  5076.4  290.25
  5087.7  291.39  5096.8  293.19  5122.4  297.04  5199.8  305.11  5220.0  306.36
#Mann=3,-1,0
  4458.3    0.15       0  4993.2    0.05       0  5006.8    0.15       0
Bank Sta=4993.2,5006.8
XS Rating Curve= 0
Exp/Cntr=0.3,0.1

Type RM Length L Ch R = 1,6023,354,354,354
BEGIN DESCRIPTION:
South Prong Cartledge Creek 12.0
END DESCRIPTION:
XS GIS Cut Line= 4
      1766049.30       463541.22      1765877.03       463835.10
      1765850.00       463933.06      1765802.71       464118.86
#Sta/Elev= 30
  4610.2  320.99  4620.5  320.55  4694.9  311.78  4710.3  311.64  4730.6  310.27
  4742.6  308.42  4771.4  307.59  4787.1  306.28  4802.4  304.16  4821.1  303.82
  4865.7  300.70  4908.7  295.71  4928.2  291.63  4962.8  280.70  4991.5  270.87
  4993.2  269.23  4994.7  267.23  5005.3  267.23  5006.8  269.23  5023.5  270.75
  5050.2  278.18  5064.9  280.90  5083.2  288.27  5115.1  298.89  5119.6  299.95
  5163.1  307.56  5174.0  308.57  5203.9  312.58  5226.3  314.74  5244.2  317.75
#Mann=3,-1,0
  4610.2    0.15       0  4993.2    0.05       0  5006.8    0.15       0
Bank Sta=4993.2,5006.8
XS Rating Curve= 0
Exp/Cntr=0.3,0.1

Type RM Length L Ch R = 1,5669,429,429,429
BEGIN DESCRIPTION:
South Prong Cartledge Creek 11.0
END DESCRIPTION:
XS GIS Cut Line= 4
      1765512.19       463477.06      1765491.93       463723.62
      1765549.36       464031.03      1765670.96       464162.76
#Sta/Elev= 30
  4520.9  312.38  4559.5  302.01  4584.0  293.73  4613.5  278.76  4625.0  275.04
  4651.9  273.21  4711.7  273.85  4818.0  272.80  4843.6  273.18  4854.0  273.88
  4940.5  272.62  4962.3  272.69  4973.1  273.21  4985.3  271.11  4993.2  268.07
  4994.7  265.07  5005.3  265.07  5006.8  268.07  5031.2  273.46  5050.3  274.69
  5088.8  275.64  5113.0  278.15  5125.6  280.62  5139.3  282.36  5150.6  285.92
  5174.8  291.84  5211.3  301.64  5231.8  306.21  5248.1  308.31  5260.3  310.93
#Mann=3,-1,0
  4520.9    0.15       0  4993.2    0.05       0  5006.8    0.15       0
Bank Sta=4993.2,5006.8
XS Rating Curve= 0
Exp/Cntr=0.3,0.1

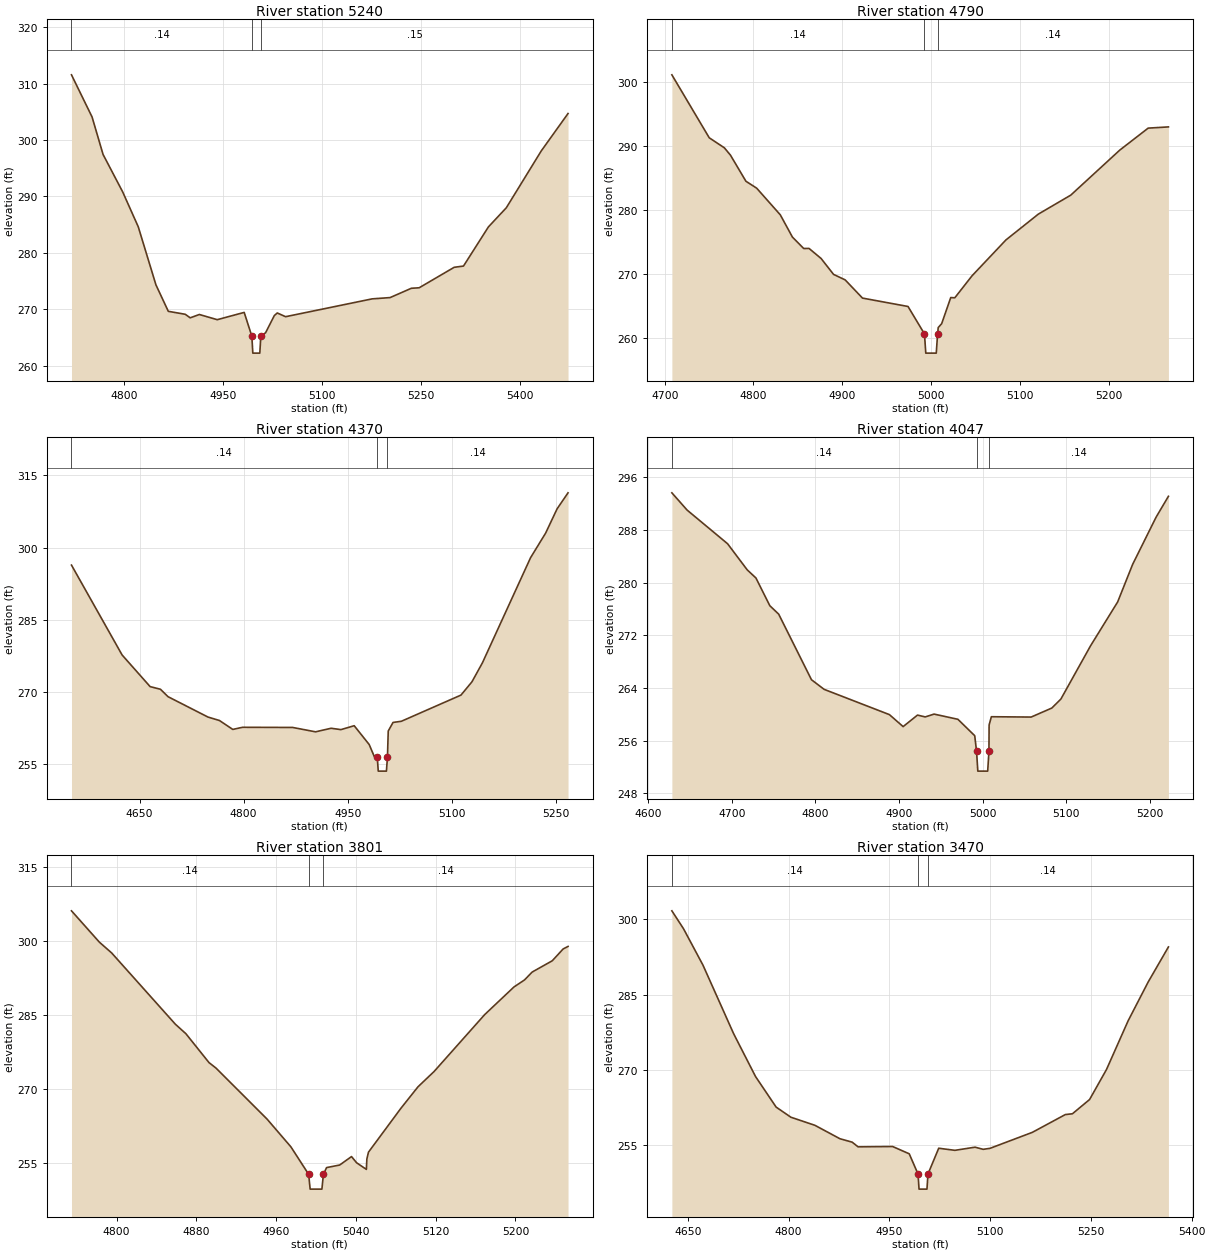
Type RM Length L Ch R = 1,5240,450,450,450
BEGIN DESCRIPTION:
South Prong Cartledge Creek 10.0
END DESCRIPTION:
XS GIS Cut Line= 4
      1765056.15       463818.20      1765133.85       463963.47
      1765191.28       464257.36      1765390.58       464466.80
#Sta/Elev= 30
  4719.6  311.55  4750.8  304.08  4767.5  297.43  4797.3  290.78  4820.9  284.60
  4847.7  274.31  4866.5  269.61  4892.1  269.09  4899.7  268.46  4913.6  269.05
  4940.7  268.13  4981.6  269.42  4993.2  265.20  4994.7  262.20  5005.3  262.20
  5006.8  265.20  5014.1  265.82  5027.3  268.86  5031.8  269.32  5044.4  268.66
  5175.7  271.82  5203.0  272.05  5235.2  273.70  5247.1  273.79  5300.2  277.42
  5314.3  277.64  5352.1  284.58  5379.3  287.98  5432.4  298.08  5472.9  304.69
#Mann=3,-1,0
  4719.6    0.14       0  4993.2    0.05       0  5006.8    0.15       0
Bank Sta=4993.2,5006.8
XS Rating Curve= 0
Exp/Cntr=0.3,0.1

Type RM Length L Ch R = 1,4790,420,420,420
BEGIN DESCRIPTION:
South Prong Cartledge Creek 9.5
END DESCRIPTION:
XS GIS Cut Line= 4
      1764870.38       463868.85      1764782.53       464064.81
      1764806.18       464196.55      1764748.74       464399.28
#Sta/Elev= 30
  4708.1  301.07  4750.2  291.24  4767.2  289.68  4774.1  288.53  4791.5  284.46
  4803.6  283.38  4830.2  279.22  4843.9  275.74  4856.6  273.96  4862.6  273.97
  4876.2  272.40  4890.2  269.92  4903.3  269.06  4922.8  266.22  4974.1  264.91
  4992.6  260.63  4994.1  257.63  5005.9  257.63  5007.4  260.63  5008.1  261.62
  5012.0  262.23  5022.2  266.30  5026.8  266.27  5046.2  269.70  5084.4  275.30
  5120.9  279.33  5157.4  282.29  5212.7  289.33  5244.6  292.75  5267.4  292.94
#Mann=3,-1,0
  4708.1    0.14       0  4992.6    0.05       0  5007.4    0.14       0
Bank Sta=4992.6,5007.4
XS Rating Curve= 0
Exp/Cntr=0.3,0.1

Type RM Length L Ch R = 1,4370,323,323,323
BEGIN DESCRIPTION:
South Prong Cartledge Creek 9.0
END DESCRIPTION:
XS GIS Cut Line= 4
      1764802.80       463784.43      1764647.41       463912.80
      1764394.05       464085.08      1764238.66       464223.58
#Sta/Elev= 30
  4551.7  296.35  4624.7  277.69  4665.1  271.12  4680.0  270.57  4690.9  269.03
  4748.5  264.80  4765.1  264.08  4784.3  262.23  4798.3  262.67  4870.6  262.64
  4903.7  261.73  4926.0  262.47  4940.3  262.19  4959.4  263.00  4981.0  259.10
  4988.3  256.63  4992.6  256.57  4994.1  253.57  5005.9  253.57  5007.4  256.57
  5008.5  261.89  5015.4  263.68  5027.4  263.92  5113.4  269.36  5129.2  272.11
  5144.3  276.05  5213.8  297.90  5235.5  303.00  5252.0  308.03  5267.8  311.36
#Mann=3,-1,0
  4551.7    0.14       0  4992.6    0.05       0  5007.4    0.14       0
Bank Sta=4992.6,5007.4
XS Rating Curve= 0
Exp/Cntr=0.3,0.1

Type RM Length L Ch R = 1,4047,246,246,246
BEGIN DESCRIPTION:
South Prong Cartledge Creek 8.0
END DESCRIPTION:
XS GIS Cut Line= 4
      1764549.43       463558.11      1764400.81       463713.49
      1764204.88       463818.21      1764073.10       463902.68
#Sta/Elev= 30
  4628.3  293.64  4646.5  291.02  4694.9  285.91  4718.4  281.94  4728.8  280.71
  4745.4  276.50  4756.0  275.22  4795.2  265.26  4810.3  263.80  4888.4  259.96
  4904.8  258.14  4922.0  259.89  4931.2  259.61  4941.8  260.04  4970.3  259.25
  4990.4  256.76  4992.6  254.38  4994.1  251.38  5005.9  251.38  5007.4  254.38
  5007.6  258.38  5010.3  259.64  5057.9  259.59  5082.6  260.96  5093.4  262.32
  5128.9  270.41  5161.3  277.07  5179.2  282.77  5207.2  289.93  5222.0  293.11
#Mann=3,-1,0
  4628.3    0.14       0  4992.6    0.05       0  5007.4    0.14       0
Bank Sta=4992.6,5007.4
XS Rating Curve= 0
Exp/Cntr=0.3,0.1

Type RM Length L Ch R = 1,3801,331,331,331
BEGIN DESCRIPTION:
South Prong Cartledge Creek 7.5
END DESCRIPTION:
XS GIS Cut Line= 4
      1764174.48       463372.32      1764137.32       463564.85
      1764086.65       463662.82      1764039.36       463848.61
#Sta/Elev= 30
  4754.7  306.09  4782.7  299.74  4795.0  297.56  4858.9  283.13  4869.5  281.20
  4892.6  275.37  4899.7  274.24  4950.8  263.94  4974.8  258.30  4992.6  252.74
  4994.1  249.74  5005.9  249.74  5007.4  252.74  5010.6  254.10  5023.7  254.62
  5035.6  256.33  5040.7  255.08  5050.5  253.74  5051.0  255.83  5052.6  257.22
  5085.2  266.12  5102.3  270.46  5118.4  273.55  5169.2  285.08  5198.6  290.68
  5209.1  292.09  5216.8  293.69  5237.0  295.98  5247.9  298.37  5252.8  298.88
#Mann=3,-1,0
  4754.7    0.14       0  4992.6    0.05       0  5007.4    0.14       0
Bank Sta=4992.6,5007.4
XS Rating Curve= 0
Exp/Cntr=0.3,0.1

Type RM Length L Ch R = 1,3470,459,459,459
BEGIN DESCRIPTION:
South Prong Cartledge Creek 7.0
END DESCRIPTION:
XS GIS Cut Line= 4
      1763938.01       463193.26      1763829.92       463392.57
      1763806.27       463672.95      1763911.01       463879.05
#Sta/Elev= 30
  4626.1  301.66  4643.5  298.08  4672.4  290.85  4718.1  277.19  4750.7  268.67
  4781.3  262.60  4803.3  260.58  4839.1  258.97  4876.3  256.30  4894.5  255.62
  4903.3  254.69  4954.8  254.75  4979.5  253.30  4992.6  249.27  4994.1  246.27
  5005.9  246.27  5007.4  249.27  5023.4  254.41  5047.5  253.99  5077.5  254.62
  5089.6  254.19  5099.8  254.39  5162.8  257.57  5211.9  261.11  5222.5  261.27
  5248.0  264.10  5273.2  270.08  5305.4  279.77  5335.2  287.48  5365.4  294.47
#Mann=3,-1,0
  4626.1    0.14       0  4992.6    0.05       0  5007.4    0.14       0
Bank Sta=4992.6,5007.4
XS Rating Curve= 0
Exp/Cntr=0.3,0.1

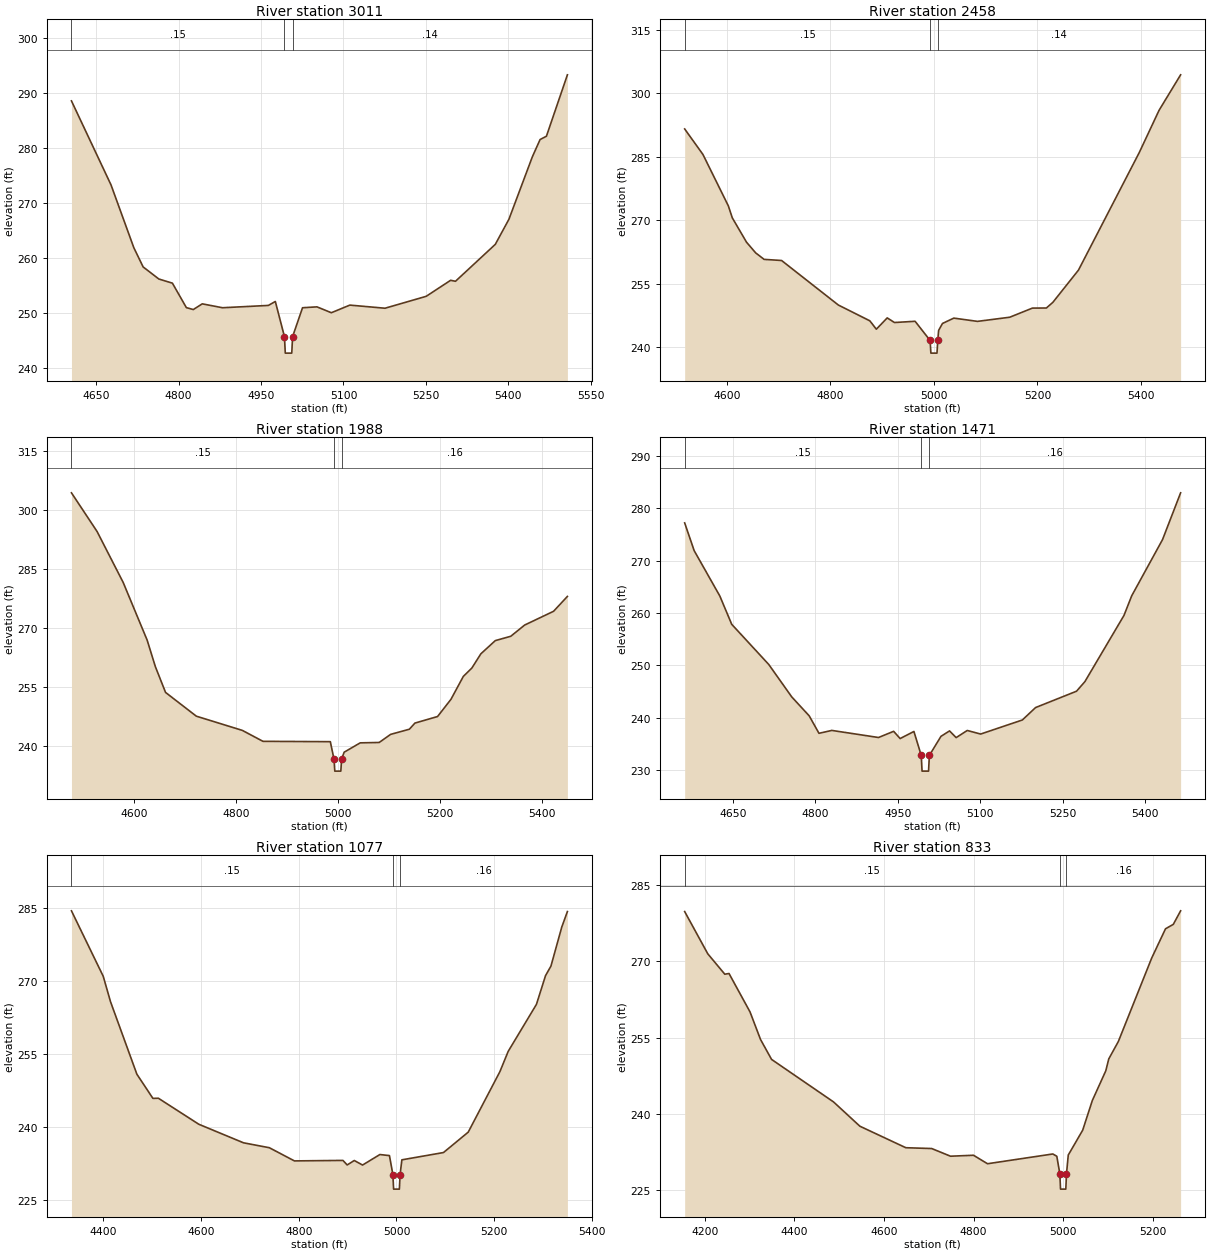
Type RM Length L Ch R = 1,3011,553,553,553
BEGIN DESCRIPTION:
South Prong Cartledge Creek 6.0
END DESCRIPTION:
XS GIS Cut Line= 4
      1763296.18       463186.52      1763340.09       463382.44
      1763438.06       463774.29      1763563.07       464044.59
#Sta/Elev= 30
  4605.0  288.63  4677.0  273.32  4718.4  261.90  4735.4  258.38  4764.1  256.17
  4788.7  255.42  4814.1  250.96  4826.7  250.61  4843.0  251.65  4879.9  250.94
  4963.3  251.36  4976.0  252.08  4992.6  245.67  4994.1  242.67  5005.9  242.67
  5007.4  245.67  5025.5  250.94  5051.8  251.10  5077.9  250.03  5111.6  251.42
  5175.6  250.85  5250.5  253.02  5295.0  255.94  5303.8  255.76  5376.3  262.49
  5401.1  267.07  5443.7  278.44  5457.8  281.59  5469.3  282.19  5507.5  293.38
#Mann=3,-1,0
  4605.0    0.15       0  4992.6    0.05       0  5007.4    0.14       0
Bank Sta=4992.6,5007.4
XS Rating Curve= 0
Exp/Cntr=0.3,0.1

Type RM Length L Ch R = 1,2458,470,470,470
BEGIN DESCRIPTION:
South Prong Cartledge Creek 5.0
END DESCRIPTION:
XS GIS Cut Line= 4
      1762982.04       463247.28      1762877.30       463409.46
      1762988.77       463922.93      1763046.21       464156.06
#Sta/Elev= 30
  4518.2  291.56  4553.5  285.53  4602.6  273.37  4610.3  270.53  4637.8  264.77
  4655.5  262.24  4671.8  260.71  4705.5  260.45  4815.3  249.91  4876.1  246.18
  4888.7  244.20  4909.7  246.87  4923.7  245.78  4963.6  246.07  4992.6  241.54
  4994.1  238.54  5005.9  238.54  5007.4  241.54  5009.1  243.92  5016.5  245.55
  5038.4  246.82  5084.2  246.05  5146.5  247.03  5190.4  249.19  5217.3  249.21
  5229.8  250.54  5279.4  258.18  5397.0  286.01  5435.2  295.98  5476.8  304.36
#Mann=3,-1,0
  4518.2    0.15       0  4992.6    0.05       0  5007.4    0.14       0
Bank Sta=4992.6,5007.4
XS Rating Curve= 0
Exp/Cntr=0.3,0.1

Type RM Length L Ch R = 1,1988,517,517,517
BEGIN DESCRIPTION:
South Prong Cartledge Creek 4.0
END DESCRIPTION:
XS GIS Cut Line= 4
      1762522.61       463274.30      1762468.55       463493.91
      1762542.87       464000.63      1762671.21       464196.52
#Sta/Elev= 30
  4477.7  304.45  4527.9  294.62  4579.1  281.66  4626.1  266.99  4642.3  260.21
  4662.2  253.68  4722.5  247.64  4812.8  244.02  4853.2  241.24  4985.3  241.15
  4992.6  236.66  4994.1  233.66  5005.9  233.66  5007.4  236.66  5012.4  238.47
  5043.9  240.85  5081.1  240.95  5103.6  243.01  5140.3  244.32  5151.2  245.88
  5195.6  247.55  5221.9  251.93  5246.1  257.75  5262.9  259.89  5280.5  263.50
  5308.8  266.86  5339.1  267.96  5366.4  270.82  5423.1  274.32  5450.2  278.10
#Mann=3,-1,0
  4477.7    0.15       0  4992.6    0.05       0  5007.4    0.16       0
Bank Sta=4992.6,5007.4
XS Rating Curve= 0
Exp/Cntr=0.3,0.1

Type RM Length L Ch R = 1,1471,394,394,394
BEGIN DESCRIPTION:
South Prong Cartledge Creek 3.0
END DESCRIPTION:
XS GIS Cut Line= 4
      1762002.37       463466.85      1762029.67       463712.65
      1762073.32       464074.94      1762245.62       464308.06
#Sta/Elev= 30
  4562.3  277.19  4579.6  271.89  4626.2  263.26  4647.9  257.85  4715.3  250.19
  4757.0  244.02  4788.9  240.39  4806.6  237.07  4830.0  237.62  4914.9  236.27
  4942.4  237.45  4954.2  236.07  4979.3  237.42  4992.6  232.86  4994.1  229.86
  5005.9  229.86  5007.4  232.86  5028.5  236.49  5044.1  237.53  5056.1  236.25
  5076.3  237.61  5100.7  236.93  5176.5  239.61  5200.6  241.98  5275.1  245.10
  5290.2  246.91  5361.4  259.55  5375.5  263.30  5431.5  274.00  5464.4  282.92
#Mann=3,-1,0
  4562.3    0.15       0  4992.6    0.05       0  5007.4    0.16       0
Bank Sta=4992.6,5007.4
XS Rating Curve= 0
Exp/Cntr=0.3,0.1

Type RM Length L Ch R = 1,1077,244,244,244
BEGIN DESCRIPTION:
South Prong Cartledge Creek 2.0
END DESCRIPTION:
XS GIS Cut Line= 4
      1761620.65       463443.21      1761634.17       463899.28
      1761772.94       464216.70      1761823.35       464422.93
#Sta/Elev= 30
  4334.8  284.49  4399.8  271.04  4414.7  265.82  4468.7  250.91  4501.5  245.94
  4512.7  245.97  4595.5  240.62  4686.9  236.81  4739.8  235.80  4791.1  233.09
  4890.4  233.19  4899.1  232.26  4913.6  233.17  4930.6  232.24  4966.0  234.40
  4985.6  234.18  4992.6  230.29  4994.1  227.29  5005.9  227.29  5007.4  230.29
  5011.0  233.31  5096.2  234.81  5146.8  239.00  5211.6  251.43  5228.6  255.60
  5286.4  265.26  5305.0  271.16  5316.1  273.13  5338.2  281.13  5349.8  284.34
#Mann=3,-1,0
  4334.8    0.15       0  4992.6    0.05       0  5007.4    0.16       0
Bank Sta=4992.6,5007.4
XS Rating Curve= 0
Exp/Cntr=0.3,0.1

Type RM Length L Ch R = 1,833,352,352,352
BEGIN DESCRIPTION:
South Prong Cartledge Creek 1.5
END DESCRIPTION:
XS GIS Cut Line= 4
      1761343.75       463439.98      1761416.30       463924.73
      1761564.68       464297.34      1761676.77       464481.96
#Sta/Elev= 30
  4155.0  279.82  4206.6  271.51  4244.6  267.50  4254.0  267.64  4300.9  260.09
  4324.4  254.66  4349.0  250.75  4487.4  242.39  4546.1  237.62  4648.7  233.39
  4706.5  233.23  4748.5  231.72  4799.8  231.91  4831.1  230.24  4976.9  232.16
  4985.8  231.71  4992.6  228.25  4994.1  225.25  5005.9  225.25  5007.4  228.25
  5011.4  231.95  5043.6  236.84  5065.1  242.67  5095.1  248.50  5101.8  250.85
  5123.2  254.27  5197.7  270.69  5228.5  276.43  5245.9  277.30  5262.2  279.96
#Mann=3,-1,0
  4155.0    0.15       0  4992.6    0.05       0  5007.4    0.16       0
Bank Sta=4992.6,5007.4
XS Rating Curve= 0
Exp/Cntr=0.5,0.3

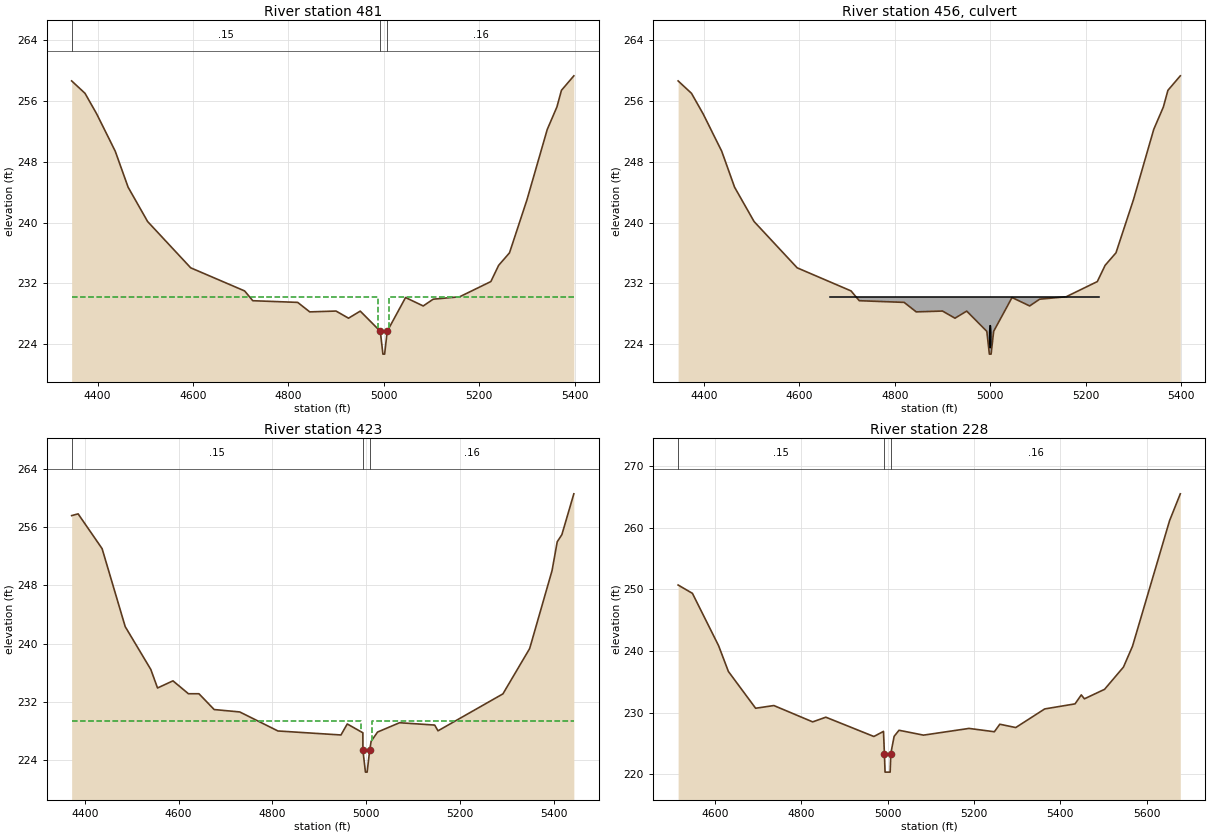
Type RM Length L Ch R = 1,481,58,58,58
BEGIN DESCRIPTION:
Unnamed Road - US
END DESCRIPTION:
XS GIS Cut Line= 5
      1760938.64       463624.12      1761031.26       463878.40
      1761162.61       464031.66      1761251.87       464267.43
      1761522.97       464452.65
#Sta/Elev= 30
  4345.6  258.66  4373.6  257.03  4398.0  254.33  4437.0  249.41  4464.0  244.67
  4504.9  240.15  4595.2  234.06  4708.2  231.02  4725.4  229.73  4819.5  229.51
  4844.8  228.26  4899.9  228.37  4926.1  227.43  4950.7  228.36  4992.8  225.70
  4998.2  222.70  5001.8  222.70  5007.2  225.70  5045.7  230.15  5082.7  229.04
  5103.6  229.93  5159.2  230.25  5224.5  232.25  5240.9  234.39  5263.6  236.03
  5300.3  243.03  5342.8  252.28  5363.0  255.23  5372.5  257.42  5398.5  259.33
#Mann=3,-1,0
  4345.6    0.15       0  4992.8    0.05       0  5007.2    0.16       0
#XS Ineff=2,0
    0.00 4988.50  230.20 5011.50    0.00  230.20
Permanent Ineff=
       F       F
Bank Sta=4992.8,5007.2
XS Rating Curve= 0
Exp/Cntr=0.5,0.3

Type RM Length L Ch R =2,456,,,
BEGIN DESCRIPTION:
Unnamed Road - TOR
Structure ID: LDS_SPCAC_01
Approximate Survey Structure
END DESCRIPTION:
Bridge Culvert--1,0,-1,-1,0
Deck Dist Width WeirC Skew NumUp NumDn MinLoCord MaxHiCord MaxSubmerge Is_Ogee
20,10,3,,2,2,,,,0,1,1,,,
  4663.5  5228.0
  230.20  230.20
  202.70  202.70
  4663.5  5228.0
  230.20  230.20
  202.35  202.35
Culvert=1,3,,10,0.024,0.9,1,2,3,223.5,5000,223.45,5000,Culvert #1,0,20
Culvert Bottom n=0.024
Culvert Bottom Depth=0
Culvert Depth Blocked=0
BC Design=,,0,,0,,,,,,

Type RM Length L Ch R = 1,423,195,195,195
BEGIN DESCRIPTION:
Unnamed Road - DS
END DESCRIPTION:
XS GIS Cut Line= 5
      1760879.70       463634.24      1760992.52       463896.93
      1761128.93       464063.65      1761208.08       464280.90
      1761487.64       464471.20
#Sta/Elev= 30
  4371.8  257.56  4385.6  257.80  4436.7  253.03  4486.0  242.32  4540.6  236.44
  4554.9  233.90  4587.8  234.88  4620.8  233.11  4643.2  233.11  4675.7  230.94
  4730.2  230.61  4811.6  228.00  4946.0  227.45  4959.4  228.96  4992.7  227.75
  4992.8  225.35  4998.2  222.35  5001.8  222.35  5007.2  225.35  5010.3  226.58
  5024.0  227.85  5070.9  229.13  5145.8  228.81  5152.9  228.02  5291.3  233.09
  5348.3  239.31  5396.0  250.00  5407.1  253.97  5417.0  254.95  5442.5  260.55
#Mann=3,-1,0
  4371.8    0.15       0  4992.8    0.05       0  5007.2    0.16       0
#XS Ineff=2,0
    0.00 4988.50  229.30 5011.50    0.00  229.30
Permanent Ineff=
       F       F
Bank Sta=4992.8,5007.2
XS Rating Curve= 0
Exp/Cntr=0.5,0.3

Type RM Length L Ch R = 1,228,0,0,0
BEGIN DESCRIPTION:
South Prong Cartledge Creek 1.0
END DESCRIPTION:
XS GIS Cut Line= 5
      1760805.77       463688.42      1760913.95       463882.24
      1760986.07       464107.61      1760992.83       464247.33
      1761495.38       464504.25
#Sta/Elev= 30
  4514.9  250.69  4548.0  249.34  4608.7  240.84  4631.3  236.67  4694.4  230.70
  4736.6  231.14  4826.5  228.49  4857.0  229.25  4968.2  226.12  4990.5  226.95
  4992.6  223.34  4994.1  220.34  5005.9  220.34  5007.4  223.34  5015.1  226.14
  5026.4  227.13  5083.1  226.34  5188.6  227.43  5247.2  226.89  5259.8  228.11
  5296.7  227.57  5363.8  230.59  5434.0  231.41  5448.5  232.87  5455.7  232.23
  5502.4  233.77  5546.2  237.38  5567.1  240.76  5652.9  261.12  5677.8  265.48
#Mann=3,-1,0
  4514.9    0.15       0  4992.6    0.05       0  5007.4    0.16       0
#XS Ineff=2,0
    0.00 4857.00  229.25               0
Permanent Ineff=
       T       F
Bank Sta=4992.6,5007.4
XS Rating Curve= 0
Exp/Cntr=0.3,0.1

Chan Stop Cuts=-1