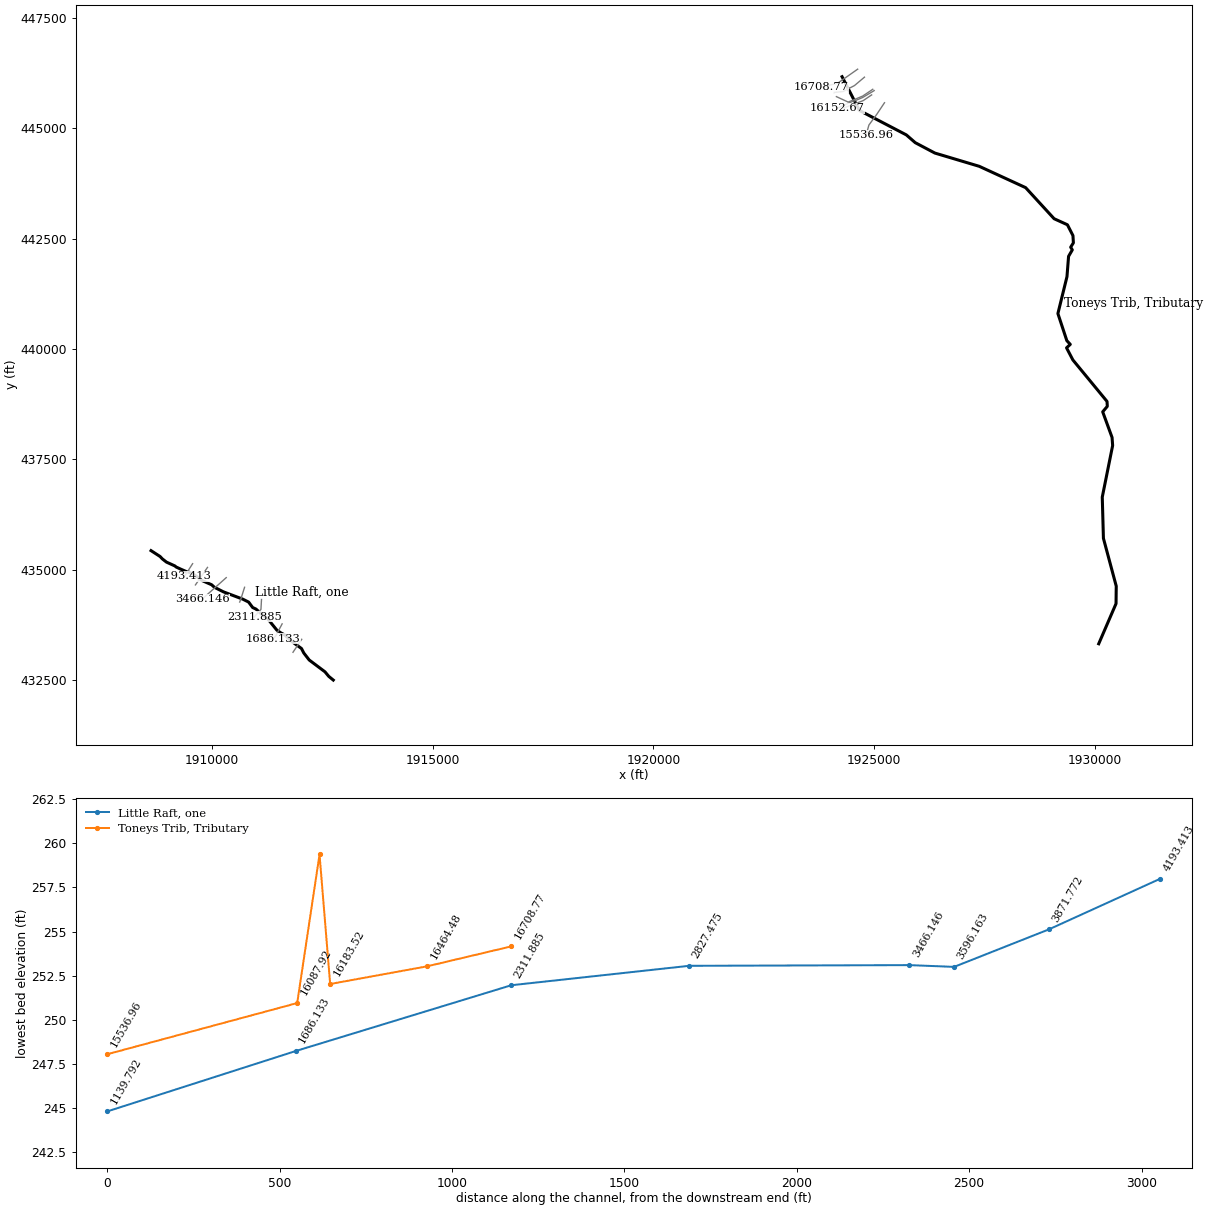
--- upraft.prj (project) ---

Proj Title=Upper Raft Swamp
Current Plan=p08
Default Exp/Contr=.3,.1
English Units
Geom File=g04
Flow File=f03
Flow File=f01
Plan File=p08
Plan File=p01
Y Axis Title=Elevation
X Axis Title(PF)=Main Channel Distance
X Axis Title(XS)=Station
BEGIN DESCRIPTION:
Floodways have been omitted from stream reaches located in swamp areas.  These include: Little Middle Swamp, Raft Swamp reaches 2 through 6 and Reach 1 downstream of section 39797, Raft Swamp Tributary downstream of section 1059, Unnamed Tributary to Raft Swamp ds of Andrews Road, Big Middle Swamp Reach two ds of section 23260, Toneys Creek Lower Reach and Upper Reach ds of US401, and Toney's Creek Tributary ds of section 15537.
This area contains several dams which are included in the state dam inventory, but either have no data or no significant hydrologic impact on the 100-year event.
END DESCRIPTION:
DSS Export Rating Curves= 0
DSS Export Rating Curve Sorted= 0
DSS Export Volume Flow Curves= 0
DXF OffsetX= 0
DXF OffsetY= 0
DXF ScaleX= 1
DXF ScaleY= 10

--- upraft.p08 (plan) ---

Plan Title=LIMITED DETAILED DELINEATION (EwBr)
Version=Version 3.0.1  Mar 2001
Short Identifier=delineation
Geom File=g04
Flow File=f03
Subcritical Flow
K Sum by GR= 0
Std Step Tol= 0.01
Critical Tol= 0.01
Num of Std Step Trials= 20
Max Error Tol= 0.3
Flow Tol Ratio= 0.001
Split Flow NTrial= 30
Split Flow Tol= 0.02
Split Flow Ratio= 0.02
Log Output Level= 0
Friction Slope Method= 1
Unsteady Friction Slope Method= 2
Parabolic Critical Depth
Global Vel Dist= 0 , 0 , 0
Global Log Level= 0
CheckData=True
Encroach Param=-1 ,0,0, 2
Encroach River=Little Raft
Encroach Reach=one
Encroach Node=4193.413
       4       1
Encroach Node=3871.772
       4       1
Encroach Node=3596.163
       1     344     352
Encroach Node=3500
       1     342     357
Encroach Node=3466.146
       1     346     357
Encroach Node=2827.475
       4       1
Encroach Node=2311.885
       4       1
Encroach Node=1686.133
       4       1
Encroach Node=1139.792
       4       1
Encroach River=Toneys Trib
Encroach Reach=Tributary
Encroach Node=16708.77
       4      .3
Encroach Node=16464.48
       4      .3
Encroach Node=16183.52
       4      .3
Encroach Node=16152.67
       4      .3
Encroach Node=16087.92
       4      .7
Encroach Node=15536.96
       4      .7
Encroach Reach=one
Encroach Node=4193.409
       4      20
Encroach Node=3871.768
       4      .7
Encroach Node=3596.160
       4       1
Encroach Node=3466.141
       4      .7
Encroach Node=2827.475
       4      .7
Encroach Node=2311.886
       4      10
Encroach Node=1686.135
       4      .7
Encroach Node=1139.795
       4       2
Encroach Reach=two
Encroach Node=36786.83
       4      .7
Encroach Node=36120.21
       4      .7
Encroach Node=34633.26
       4      .7
Encroach Node=33256.38
       4      .7
Encroach Node=33200
       4      .7
Encroach Node=33154.24
       4      .7
Encroach Node=31925.16
       4      .2
Encroach Node=30843.70
       4      .7
Encroach Node=30026.89
       4      .7
Encroach Node=29517.74
       4      .7
Encroach Node=29475
       4      .3
Encroach Node=29390.49
       4      .7
Encroach Node=28915.04
       4      .7
Encroach Node=28593.44
       4      .7
Encroach Node=28008.00
       4      .7
Encroach Node=26204.15
       4      .7
Encroach Node=26125
       4      .7
Encroach Node=26048.59
       4      .7
Encroach Node=25415.62
       4      .7
Encroach Node=24505.35
       4      .7
Encroach Node=23614.87
       4      .3
Encroach Node=23093.08
       4      .2
Encroach Node=20600.19
       4      10
Encroach Node=18136.95
       4       5
Encroach Node=18100
       4      .7
Encroach Node=17979.38
       4      .1
Encroach Node=15886.45
       4      .7
Encroach Node=14894.68
       4       1
Encroach River=Raft Trib
Encroach Reach=one
Encroach Node=2209.383
       1     440     510
Encroach Node=1839.998
       1     355     415
Encroach Node=1783.777
       4      .7
Encroach Node=1716.791
       4       1
Encroach Node=1059.292
       4       1
Encroach River=Big Middle Swamp
Encroach Reach=one
Encroach Node=34425.77
       4      .8
Encroach Node=34329.65
       4       1
Encroach Node=33599.89
       4      .7
Encroach Node=32427.20
       4      .7
Encroach Node=31901.07
       4       1
Encroach Node=31121.48
       4      .8
Encroach Node=29853.69
       4      .8
Encroach Node=28641.81
       4      .6
Encroach Node=27420.54
       1     292     308
Encroach Node=27350
       4      .7
Encroach Node=27329.47
       4      .7
Encroach Node=25978.32
       4      .7
Encroach Node=24901.31
       4       1
Encroach Reach=two
Encroach Node=23893.03
       4      .7
Encroach Node=23260.46
       4      .7
Encroach Reach=five
Encroach Node=5338.952
       1    1750    2100
Encroach Node=4295.078
       1    1450    1700
Encroach River=Unmd Trib to Raf
Encroach Reach=one
Encroach Node=6968.509
       4      .7
Encroach Node=6818.804
       4      .7
Encroach Node=6262.827
       4       1
Encroach Node=5708.149
       4       1
Encroach Node=4624.104
       1     536     564
Encroach River=Toneys
Encroach Reach=upper
Encroach Node=27166.28
       4      .7
Encroach Node=25570.04
       4      .7
Encroach Node=23795.39
       1     800     953
Encroach Node=23124.47
       1     600     725
Encroach Node=23110.78
       4      .7
Encroach Node=23078.15
       4      .7
Encroach Node=22055.42
       4      .8
Encroach Node=20676.93
       4      .7
Encroach Node=19609.42
       4       1
Encroach Node=18348.93
       1    1320    1330
Encroach River=Raft Swamp
Encroach Reach=one
Encroach Node=47188.15
       4      .8
Encroach Node=46921.74
       4      .7
Encroach Node=46367.23
       4       1
Encroach Node=45268.16
       4       1
Encroach Node=44400.80
       4      .7
Encroach Node=43786.27
       4       1
Encroach Node=43110.25
       4      .7
Encroach Node=43050
       4      .7
Encroach Node=43020.37
       4      .7
Encroach Node=41435.81
       4       1
Encroach Node=40682.05
       4       1
Encroach Node=39797.93
       4       1
Encroach Reach=upper
Encroach Node=27166.28
       4      .7
Encroach Node=25570.04
       4      .7
Encroach Node=23795.39
       1     800     953
Encroach Node=23124.47
       1     600     725
Encroach Node=23110.78
       4      .7
Encroach Node=23078.15
       4      .7
Encroach Node=22055.42
       4      .7
Encroach Node=20676.93
       4      .2
Encroach Node=19609.42
       4      .7
Encroach Node=18348.93
       1    1320    1330
Encroach Node=18300
       1    1320    1330
Encroach Node=18274.75
       1    1320    1330
Encroach Node=16781.26
       4      .9
Encroach Node=16234.99
       4      .7
Encroach Node=16180.22
       4      .2
Encroach Node=16084.80
       4      .9
Encroach Node=15051.49
       1     908    1045
Encroach Node=14444.60
       1     679     696
Encroach Node=14400
       1     492     696
Encroach Node=14309.12
       1     492     510
Encroach Node=13843.49
       4      .7
Encroach Node=13345.61
       4      .7
Encroach Node=12907.39
       1     612     646
Encroach Node=12900
       1     611     645
Encroach Node=12859.68
       1     612     646
Encroach Node=11922.08
       1     524     650
Encroach Node=11032.58
       1     380     507
Encroach Node=10051.03
       1     548     580
Encroach Node=10025
       1     548     589
Encroach Node=9999.496
       1     567     589
Encroach Node=9349.251
       4      .7
Encroach Node=8804.968
       4      .7
Encroach Node=8247.843
       4      .7
Encroach Node=7090.430
       4      .7
Encroach Node=6095.014
       4      .7
Encroach Node=5122.141
       4      .7
Computation Interval=1HOUR
Output Interval=1HOUR
Run HTab= 0
Run UNet= 0
Run PostProcess= 0
UNET Theta= 1
UNET ZTol= 0.02
UNET ZSATol= 0.1
UNET MxIter= 20
UNET MaxInSteps= 20
UNET DtIC= 0
UNET DtMin= 0
UNET MaxCRTS= 20
UNET WFStab= 2
UNET SFStab= 1
UNET WFX= 1
UNET SFX= 1
UNET Convert EG Bridges=-1
UNET Use Existing IB Tables=-1
Instantaneous Interval=1HOUR
Write IC File= 0
Write Velocity= 0
Write Detailed= 0

--- upraft.p01 (plan) ---

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Plan Title=slope-area
Short Identifier=s-a
Geom File=g04
Flow File=f01
Encroach Node=15134.91
Encroach Node=13991.59
       1     794  822.75
Encroach Node=13950
       1     794  822.75
Encroach Node=13942.37
       1     794  822.75
Encroach Node=12406.38
       1     885    1005
Encroach Node=11645.98
       1     645     666
Encroach Node=11600
       1     645     666
Encroach Node=11582.77
       1     645     666
Encroach Node=11009.22
       1     720     870
Encroach Node=10970
       1     720     870
Encroach Node=10952.11
       1     720     870
Encroach Node=10242.61
       1     720     890
Encroach Node=9319.043
       1     790     940
Encroach Node=8231.161
       1     690     770
Encroach Node=8207.270
Encroach Node=8183.923
Encroach Node=7573.170
Encroach Node=7133.585
Encroach Node=6529.366
       1     704     730
Encroach Node=6500
       1     703     731
Encroach Node=6469.116
       1     703     731
Encroach Node=4966.555
Encroach Node=3283.960
Encroach Node=1749.078
Encroach Node=891.005
Encroach Node=415.572
       1     460     510
Encroach Node=812.200
       4      .5
Encroach Node=330.736
       1     320     380
Encroach Node=21682.84
Encroach Node=20177.71
Encroach Node=20108
Encroach Node=20080.98
       1     722    1015
Encroach Node=18531.74
Encroach Node=17261.25
Encroach Node=16807.95
       1     661     678
Encroach Node=16780
       1     590     676
Encroach Node=16765.14
       1     583     604
Encroach Node=16311.99
Encroach Node=14875.69
       1     388     425
Encroach Node=14818
       1     390     425
Encroach Node=14766.18
Encroach Node=12802.75
Encroach Node=11316.17
       1     540     575
Encroach Node=11271
       1     520     575
Encroach Node=11212.82
       1     520     554
Encroach Node=8608.604
Encroach Node=7398.322
Encroach Node=5422.359
Encroach Node=3777.575
Encroach Node=2331.797
       1     691     724
Encroach Node=2272
Encroach Node=2213.341
Encroach Node=1499.608
Encroach Node=1081.484
Encroach Node=4510
Encroach Node=4497.864
Encroach Node=3095.502
Encroach Node=1613.738
Encroach Reach=Lower
Encroach Node=4391.645
Encroach Node=3594.530
       4     1.3
Encroach Node=3227.726
       4     1.3
Encroach Node=2314.825
       4     1.3
Encroach Node=2060.046
       1     820     870
Encroach Node=1976
       1     820     900
Encroach Node=1919.281
       1     846     900
Encroach Node=1125.491
       4     1.3
Encroach Node=38962.12
Encroach Node=37989.43
Encroach Node=37302.51
       1     370     380
       1     370     468
       1     461     478
       1     250     390
       1    1700    1850
       1    1717    1736
       1    1687    1736
       1    1687    1704
       1     630     648
       1     476     648
       1     476     495
       1     285     630
       1     278     630
       1     280     630
       1     550     760
Encroach Reach=three
Encroach Node=13831.19
       4      .5
Encroach Node=11881.39
Encroach Node=9548.713
Encroach Node=8097.348
       4     .01
Encroach Reach=four
Encroach Node=6555.530
Encroach Node=6222.441
       1    1700    2250
       1    1200    1700
Encroach Reach=six
Encroach Node=3384.885
       1    1030    1430
Encroach Node=765.745
       1     825    1100
Encroach Node=60.987
       1     -25     270
Encroach River=Little Middle Sw
Encroach Node=13038.78
Encroach Node=11331.05
Encroach Node=9561.107
Encroach Node=7995.133
Encroach Node=6299.352
Encroach Node=4770.686
Encroach Node=3380.940
Encroach Node=1791.920
Encroach Node=1700
Encroach Node=1670.976
Encroach Node=1362.013
       4      .5

--- upraft.f03 (steady flow) ---

Flow Title=revised base flood (E)
Version=Version 3.0.1  Mar 2001
Number of Profiles= 2
Profile Names=base flood,FLOODWAY
River Rch & RM=Little Raft,one             ,4193.413
      15      15
River Rch & RM=Little Raft,one             ,3596.163
      20      20
River Rch & RM=Little Raft,one             ,2827.475
      25      25
River Rch & RM=Little Raft,one             ,2311.885
      30      30
River Rch & RM=Little Raft,one             ,1686.133
      35      35
River Rch & RM=Toneys Trib,Tributary       ,16708.77
     202     202
River Rch & RM=Toneys Trib,Tributary       ,12406.38
     260     260
River Rch & RM=Toneys Trib,Tributary       ,8183.923
     318     318
River Rch & RM=Toneys Trib,Tributary       ,415.572
     376     376
River Rch & RM=Raft Trib,one             ,2209.383
      58      58
River Rch & RM=Raft Trib,one             ,1716.791
     147     147
River Rch & RM=Big Middle Swamp,one             ,34425.77
     219     219
River Rch & RM=Big Middle Swamp,one             ,24901.31
     234     234
River Rch & RM=Big Middle Swamp,two             ,23893.03
     259     259
River Rch & RM=Big Middle Swamp,two             ,23260.46
     284     284
River Rch & RM=Big Middle Swamp,two             ,18531.74
     334     334
River Rch & RM=Big Middle Swamp,two             ,17261.25
     359     359
River Rch & RM=Big Middle Swamp,two             ,16311.99
     384     384
River Rch & RM=Big Middle Swamp,two             ,14875.69
     409     409
River Rch & RM=Big Middle Swamp,two             ,12802.75
     434     434
River Rch & RM=Big Middle Swamp,two             ,11316.17
     459     459
River Rch & RM=Big Middle Swamp,two             ,8608.604
     484     484
River Rch & RM=Big Middle Swamp,two             ,5422.359
     534     534
River Rch & RM=Big Middle Swamp,two             ,3777.575
     559     559
River Rch & RM=Big Middle Swamp,two             ,2331.797
     579     579
River Rch & RM=Unmd Trib to Raf,one             ,6968.509
      33      33
River Rch & RM=Unmd Trib to Raf,one             ,6818.804
      57      57
River Rch & RM=Unmd Trib to Raf,one             ,6262.827
      61      61
River Rch & RM=Unmd Trib to Raf,one             ,5708.149
      75      75
River Rch & RM=Unmd Trib to Raf,one             ,4624.104
      89      89
River Rch & RM=Unmd Trib to Raf,one             ,3095.502
     132     132
River Rch & RM=Toneys,upper           ,27166.28
     243     243
River Rch & RM=Toneys,upper           ,25570.04
     254     254
River Rch & RM=Toneys,upper           ,23795.39
     265     265
River Rch & RM=Toneys,upper           ,23124.47
     276     276
River Rch & RM=Toneys,upper           ,22055.42
     320     320
River Rch & RM=Toneys,upper           ,15051.49
     364     364
River Rch & RM=Toneys,upper           ,11032.58
     408     408
River Rch & RM=Toneys,Lower           ,4391.645
     631     631
River Rch & RM=Toneys,Lower           ,3227.726
     694     694
River Rch & RM=Raft Swamp,one             ,47188.15
     203     203
River Rch & RM=Raft Swamp,one             ,41435.81
     247     247
River Rch & RM=Raft Swamp,one             ,40682.05
     269     269
River Rch & RM=Raft Swamp,one             ,39797.93
     291     291
River Rch & RM=Raft Swamp,one             ,38962.12
     312     312
River Rch & RM=Raft Swamp,one             ,37989.43
     332     332
River Rch & RM=Raft Swamp,one             ,37302.51
     398     398
River Rch & RM=Raft Swamp,two             ,36786.83
     447     447
River Rch & RM=Raft Swamp,two             ,31925.16
     496     496
River Rch & RM=Raft Swamp,two             ,24505.35
     545     545
River Rch & RM=Raft Swamp,two             ,20600.19
     593     593
River Rch & RM=Raft Swamp,two             ,14894.68
    1038    1038
River Rch & RM=Raft Swamp,three           ,13831.19
    1092    1092
River Rch & RM=Raft Swamp,four            ,6555.530
    1375    1375
River Rch & RM=Raft Swamp,five            ,5338.952
    1419    1419
River Rch & RM=Raft Swamp,six             ,3384.885
    1552    1552
River Rch & RM=Little Middle Sw,one             ,13038.78
     260     260
River Rch & RM=Little Middle Sw,one             ,9561.107
     286     286
River Rch & RM=Little Middle Sw,one             ,6299.352
     312     312
River Rch & RM=Little Middle Sw,one             ,3380.940
     338     338
River Rch & RM=Little Middle Sw,one             ,1791.920
     364     364
Boundary for River Rch & Prof#=Little Raft,one             , 1
Up Type= 0
Dn Type= 0
Boundary for River Rch & Prof#=Little Raft,one             , 2
Up Type= 0
Dn Type= 0
Boundary for River Rch & Prof#=Toneys Trib,Tributary       , 1
Up Type= 0
Dn Type= 0
Boundary for River Rch & Prof#=Toneys Trib,Tributary       , 2
Up Type= 0
Dn Type= 0
Boundary for River Rch & Prof#=Raft Trib,one             , 1
Up Type= 0
Dn Type= 0
Boundary for River Rch & Prof#=Raft Trib,one             , 2
Up Type= 0
Dn Type= 0
Boundary for River Rch & Prof#=Big Middle Swamp,one             , 1
Up Type= 0
Dn Type= 0
Boundary for River Rch & Prof#=Big Middle Swamp,one             , 2
Up Type= 0
Dn Type= 0
Boundary for River Rch & Prof#=Big Middle Swamp,two             , 1
Up Type= 0
Dn Type= 0
Boundary for River Rch & Prof#=Big Middle Swamp,two             , 2
Up Type= 0
Dn Type= 0
Boundary for River Rch & Prof#=Unmd Trib to Raf,one             , 1
Up Type= 0
Dn Type= 0
Boundary for River Rch & Prof#=Unmd Trib to Raf,one             , 2
Up Type= 0
Dn Type= 0
Boundary for River Rch & Prof#=Toneys,upper           , 1
Up Type= 0
Dn Type= 0
Boundary for River Rch & Prof#=Toneys,upper           , 2
Up Type= 0
Dn Type= 0
Boundary for River Rch & Prof#=Toneys,Lower           , 1
Up Type= 0
Dn Type= 2
Boundary for River Rch & Prof#=Toneys,Lower           , 2
Up Type= 0
Dn Type= 2
Boundary for River Rch & Prof#=Raft Swamp,one             , 1
Up Type= 0
Dn Type= 0
Boundary for River Rch & Prof#=Raft Swamp,one             , 2
Up Type= 0
Dn Type= 0
Boundary for River Rch & Prof#=Raft Swamp,two             , 1
Up Type= 0
Dn Type= 0
Boundary for River Rch & Prof#=Raft Swamp,two             , 2
Up Type= 0
Dn Type= 0
Boundary for River Rch & Prof#=Raft Swamp,three           , 1
Up Type= 0
Dn Type= 0
Boundary for River Rch & Prof#=Raft Swamp,three           , 2
Up Type= 0
Dn Type= 0
Boundary for River Rch & Prof#=Raft Swamp,four            , 1
Up Type= 0
Dn Type= 0
Boundary for River Rch & Prof#=Raft Swamp,four            , 2
Up Type= 0
Dn Type= 0
Boundary for River Rch & Prof#=Raft Swamp,five            , 1
Up Type= 0
Dn Type= 0
Boundary for River Rch & Prof#=Raft Swamp,five            , 2
Up Type= 0
Dn Type= 0
Boundary for River Rch & Prof#=Raft Swamp,six             , 1
Up Type= 0
Dn Type= 1
Dn Known WS=205.2
Boundary for River Rch & Prof#=Raft Swamp,six             , 2
Up Type= 0
Dn Type= 1
Dn Known WS=205.4
Boundary for River Rch & Prof#=Little Middle Sw,one             , 1
Up Type= 0
Dn Type= 0
Boundary for River Rch & Prof#=Little Middle Sw,one             , 2
Up Type= 0
Dn Type= 0
Set Internal Change=Toneys Trib     ,Tributary       ,15536.96, 2 , 3 ,251.1
Set Internal Change=Raft Trib       ,one             ,1059.292, 2 , 3 ,254.7
Set Internal Change=Big Middle Swamp,two             ,23260.46, 2 , 3 ,243.27
Set Internal Change=Unmd Trib to Raf,one             ,4624.104, 2 , 3 ,215.75
Set Internal Change=Unmd Trib to Raf,one             ,1613.738, 2 , 3 ,205.33
Set Internal Change=Toneys          ,upper           ,18348.93, 2 , 3 ,245.4
Set Internal Change=Raft Swamp      ,one             ,39797.93, 2 , 3 ,257.02
DSS Import GetInterval= 0
DSS Import GetPeak= 0
DSS Import FillOption= 0

--- upraft.f01 (steady flow) ---

Flow Title=slope-area
Version=September 1998 Version 2.2
Number of Profiles= 2
Profile Names=base flood,FLOODWAY
River Rch & RM=Little Raft,one             ,4193.413
      15      15
River Rch & RM=Little Raft,one             ,3596.163
      20      20
River Rch & RM=Little Raft,one             ,2827.475
      25      25
River Rch & RM=Little Raft,one             ,2311.885
      30      30
River Rch & RM=Little Raft,one             ,1686.133
      35      35
River Rch & RM=Toneys Trib,Tributary       ,16708.77
     202     202
River Rch & RM=Toneys Trib,Tributary       ,12406.38
     260     260
River Rch & RM=Toneys Trib,Tributary       ,8183.923
     318     318
River Rch & RM=Toneys Trib,Tributary       ,415.572
     376     376
River Rch & RM=Raft Trib,one             ,2209.383
      58      58
River Rch & RM=Raft Trib,one             ,1716.791
     147     147
River Rch & RM=Big Middle Swamp,one             ,34425.77
     219     219
River Rch & RM=Big Middle Swamp,one             ,24901.31
     234     234
River Rch & RM=Big Middle Swamp,two             ,23893.03
     259     259
River Rch & RM=Big Middle Swamp,two             ,23260.46
     284     284
River Rch & RM=Big Middle Swamp,two             ,18531.74
     334     334
River Rch & RM=Big Middle Swamp,two             ,17261.25
     359     359
River Rch & RM=Big Middle Swamp,two             ,16311.99
     384     384
River Rch & RM=Big Middle Swamp,two             ,14875.69
     409     409
River Rch & RM=Big Middle Swamp,two             ,12802.75
     434     434
River Rch & RM=Big Middle Swamp,two             ,11316.17
     459     459
River Rch & RM=Big Middle Swamp,two             ,8608.604
     484     484
River Rch & RM=Big Middle Swamp,two             ,5422.359
     534     534
River Rch & RM=Big Middle Swamp,two             ,3777.575
     559     559
River Rch & RM=Big Middle Swamp,two             ,2331.797
     579     579
River Rch & RM=Unmd Trib to Raf,one             ,6968.509
      33      33
River Rch & RM=Unmd Trib to Raf,one             ,6818.804
      57      57
River Rch & RM=Unmd Trib to Raf,one             ,6262.827
      61      61
River Rch & RM=Unmd Trib to Raf,one             ,5708.149
      75      75
River Rch & RM=Unmd Trib to Raf,one             ,4624.104
      89      89
River Rch & RM=Unmd Trib to Raf,one             ,3095.502
     132     132
River Rch & RM=Toneys,upper           ,27166.28
     243     243
River Rch & RM=Toneys,upper           ,25570.04
     254     254
River Rch & RM=Toneys,upper           ,23795.39
     265     265
River Rch & RM=Toneys,upper           ,23124.47
     276     276
River Rch & RM=Toneys,upper           ,22055.42
     320     320
River Rch & RM=Toneys,upper           ,15051.49
     364     364
River Rch & RM=Toneys,upper           ,11032.58
     408     408
River Rch & RM=Toneys,Lower           ,4391.645
     631     631
River Rch & RM=Toneys,Lower           ,3227.726
     694     694
River Rch & RM=Raft Swamp,one             ,47188.15
     203     203
River Rch & RM=Raft Swamp,one             ,41435.81
     247     247
River Rch & RM=Raft Swamp,one             ,40682.05
     269     269
River Rch & RM=Raft Swamp,one             ,39797.93
     291     291
River Rch & RM=Raft Swamp,one             ,38962.12
     312     312
River Rch & RM=Raft Swamp,one             ,37989.43
     332     332
River Rch & RM=Raft Swamp,one             ,37302.51
     398     398
River Rch & RM=Raft Swamp,two             ,36786.83
     447     447
River Rch & RM=Raft Swamp,two             ,31925.16
     496     496
River Rch & RM=Raft Swamp,two             ,24505.35
     545     545
River Rch & RM=Raft Swamp,two             ,20600.19
     593     593
River Rch & RM=Raft Swamp,two             ,14894.68
    1038    1038
River Rch & RM=Raft Swamp,three           ,13831.19
    1092    1092
River Rch & RM=Raft Swamp,four            ,6555.530
    1375    1375
River Rch & RM=Raft Swamp,five            ,5338.952
    1419    1419
River Rch & RM=Raft Swamp,six             ,3384.885
    1552    1552
River Rch & RM=Little Middle Sw,one             ,13038.78
     260     260
River Rch & RM=Little Middle Sw,one             ,9561.107
     286     286
River Rch & RM=Little Middle Sw,one             ,6299.352
     312     312
River Rch & RM=Little Middle Sw,one             ,3380.940
     338     338
River Rch & RM=Little Middle Sw,one             ,1791.920
     364     364
Boundary for River Rch & Prof#=Little Raft,one             , 1
Up Type= 0
Dn Type= 0
Boundary for River Rch & Prof#=Little Raft,one             , 2
Up Type= 0
Dn Type= 0
Boundary for River Rch & Prof#=Toneys Trib,Tributary       , 1
Up Type= 0
Dn Type= 0
Boundary for River Rch & Prof#=Toneys Trib,Tributary       , 2
Up Type= 0
Dn Type= 0
Boundary for River Rch & Prof#=Raft Trib,one             , 1
Up Type= 0
Dn Type= 0
Boundary for River Rch & Prof#=Raft Trib,one             , 2
Up Type= 0
Dn Type= 0
Boundary for River Rch & Prof#=Big Middle Swamp,one             , 1
Up Type= 0
Dn Type= 0
Boundary for River Rch & Prof#=Big Middle Swamp,one             , 2
Up Type= 0
Dn Type= 0
Boundary for River Rch & Prof#=Big Middle Swamp,two             , 1
Up Type= 0
Dn Type= 0
Boundary for River Rch & Prof#=Big Middle Swamp,two             , 2
Up Type= 0
Dn Type= 0
Boundary for River Rch & Prof#=Unmd Trib to Raf,one             , 1
Up Type= 0
Dn Type= 0
Boundary for River Rch & Prof#=Unmd Trib to Raf,one             , 2
Up Type= 0
Dn Type= 0
Boundary for River Rch & Prof#=Toneys,upper           , 1
Up Type= 0
Dn Type= 0
Boundary for River Rch & Prof#=Toneys,upper           , 2
Up Type= 0
Dn Type= 0
Boundary for River Rch & Prof#=Toneys,Lower           , 1
Up Type= 0
Dn Type= 2
Boundary for River Rch & Prof#=Toneys,Lower           , 2
Up Type= 0
Dn Type= 2
Boundary for River Rch & Prof#=Raft Swamp,one             , 1
Up Type= 0
Dn Type= 0
Boundary for River Rch & Prof#=Raft Swamp,one             , 2
Up Type= 0
Dn Type= 0
Boundary for River Rch & Prof#=Raft Swamp,two             , 1
Up Type= 0
Dn Type= 0
Boundary for River Rch & Prof#=Raft Swamp,two             , 2
Up Type= 0
Dn Type= 0
Boundary for River Rch & Prof#=Raft Swamp,three           , 1
Up Type= 0
Dn Type= 0
Boundary for River Rch & Prof#=Raft Swamp,three           , 2
Up Type= 0
Dn Type= 0
Boundary for River Rch & Prof#=Raft Swamp,four            , 1
Up Type= 0
Dn Type= 0
Boundary for River Rch & Prof#=Raft Swamp,four            , 2
Up Type= 0
Dn Type= 0
Boundary for River Rch & Prof#=Raft Swamp,five            , 1
Up Type= 0
Dn Type= 0
Boundary for River Rch & Prof#=Raft Swamp,five            , 2
Up Type= 0
Dn Type= 0
Boundary for River Rch & Prof#=Raft Swamp,six             , 1
Up Type= 0
Dn Type= 3
Dn Slope=.0001
Boundary for River Rch & Prof#=Raft Swamp,six             , 2
Up Type= 0
Dn Type= 1
Dn Known WS=204.79
Boundary for River Rch & Prof#=Little Middle Sw,one             , 1
Up Type= 0
Dn Type= 0
Boundary for River Rch & Prof#=Little Middle Sw,one             , 2
Up Type= 0
Dn Type= 0
DSS Import GetInterval= 0
DSS Import GetPeak= 0
DSS Import FillOption= 0

--- upraft.g04 (geometry) ---

Geom Title=existing conditions 2
Version=Version 3.0.1  Mar 2001

Junct Name=2
Junct Desc=, 0 , 0 ,-1
Up River,Reach=Toneys          ,upper
Up River,Reach=Toneys Trib     ,Tributary
Dn River,Reach=Toneys          ,Lower
Junc L&A=730.5,0
Junc L&A=415.57,0

Junct Name=4
Junct Desc=, 0 ,-1 ,-1
Up River,Reach=Toneys          ,Lower
Up River,Reach=Raft Swamp      ,two
Dn River,Reach=Raft Swamp      ,three
Junc L&A=1125.49,0
Junc L&A=1063.49,0

Junct Name=6
Junct Desc=, 0 , 0 ,-1
Up River,Reach=Raft Swamp      ,one
Up River,Reach=Raft Trib       ,one
Dn River,Reach=Raft Swamp      ,two
Junc L&A=515.68,0
Junc L&A=330.74,0

Junct Name=8
Junct Desc=, 0 , 0 ,-1
Up River,Reach=Raft Swamp      ,three
Up River,Reach=Big Middle Swamp,two
Dn River,Reach=Raft Swamp      ,four
Junc L&A=1541.82,
Junc L&A=1081.48,

Junct Name=10
Junct Desc=, 0 , 0 ,-1
Up River,Reach=Big Middle Swamp,one
Up River,Reach=Little Raft     ,one
Dn River,Reach=Big Middle Swamp,two
Junc L&A=1008.28,
Junc L&A=1139.79,0

Junct Name=12
Junct Desc=, 0 , 0 ,-1
Up River,Reach=Raft Swamp      ,four
Up River,Reach=Unmd Trib to Raf,one
Dn River,Reach=Raft Swamp      ,five
Junc L&A=883.49,
Junc L&A=1613.74,0

Junct Name=14
Junct Desc=, 0 , 0 ,-1
Up River,Reach=Raft Swamp      ,five
Up River,Reach=Little Middle Sw,one
Dn River,Reach=Raft Swamp      ,six
Junc L&A=910.19,
Junc L&A=1362.01,0

River Reach=Little Raft     ,one
Reach XY= 30
      1908627.24       435435.15      1908831.83        435302.6
       1908883.7       435247.85      1908975.91       435175.82
      1909166.09       435089.37      1909197.78       435063.44
      1909310.16       435011.57      1909416.78       434965.47
      1909494.58       434945.29      1909624.25       434876.14
      1909782.73         434758.      1909998.84       434662.91
      1910062.24       434605.28      1910268.26       434501.54
      1910703.37        434337.3      1910835.92       434271.02
      1910928.13       434147.12      1911003.05       434112.54
      1911129.84       433997.28      1911262.39       433899.31
      1911474.18       433637.09      1911560.62       433576.58
      1911655.71       433524.71      1911831.48       433366.23
      1912033.19       433219.27      1912085.06       433118.42
      1912207.52       432959.93      1912564.83       432691.95
      1912651.27       432588.22      1912752.89       432505.32

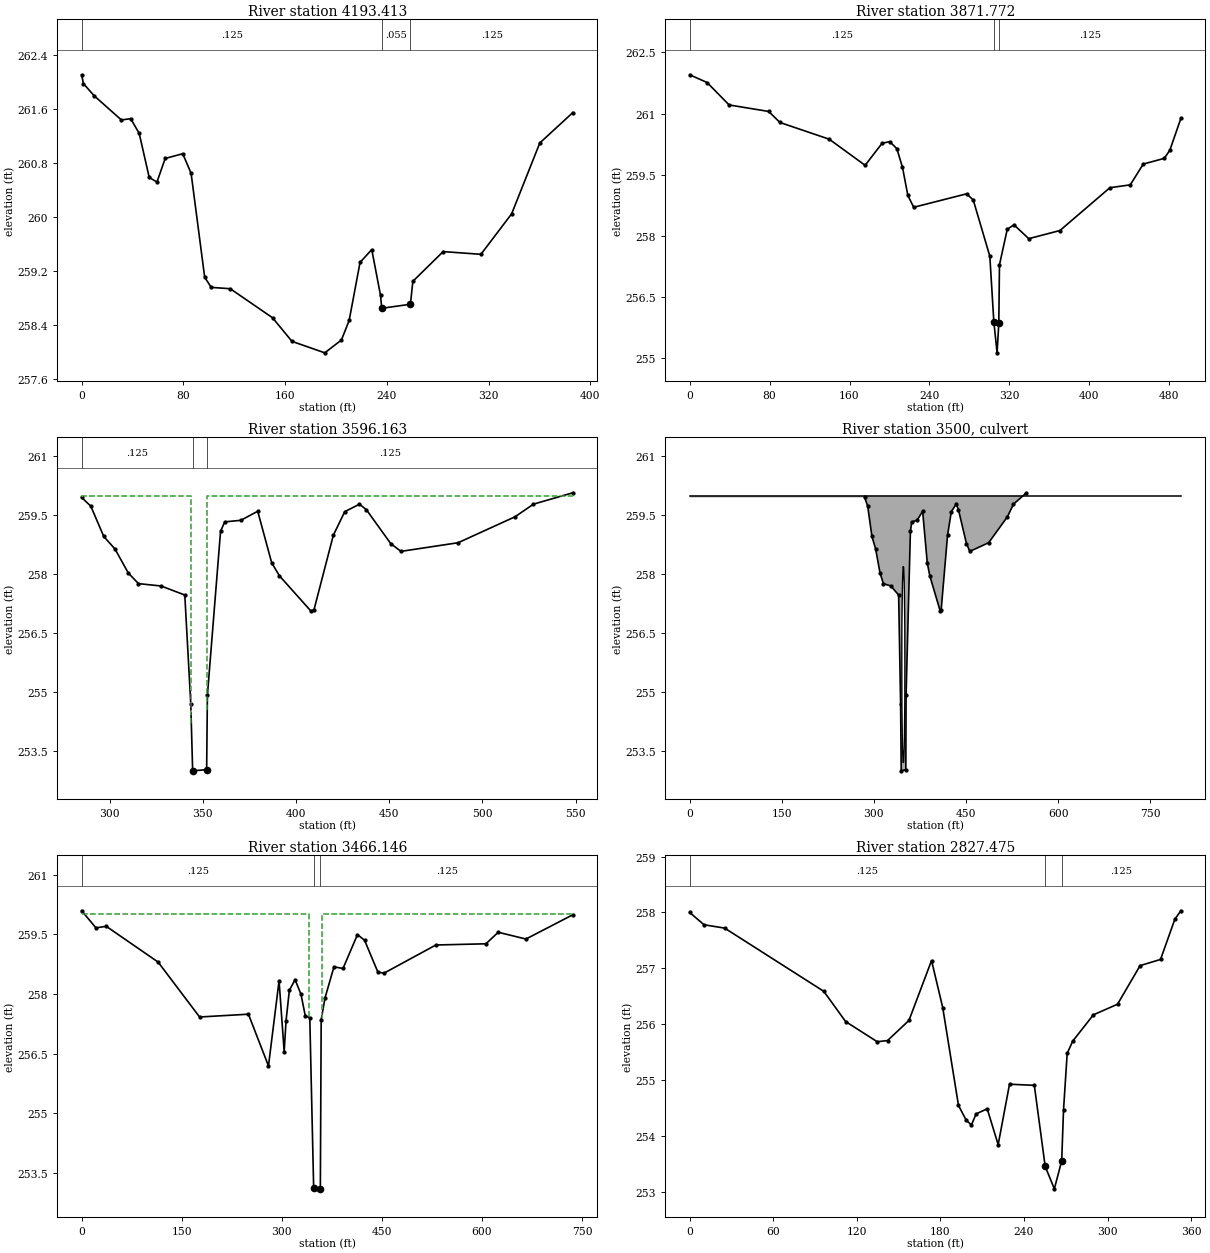
Type RM Length L Ch R = 1 ,4193.413,322.02,321.64,317.08
XS GIS Cut Line= 2
     1909568.369      435140.501     1909386.397      434855.439
#Sta/Elev= 30
       0  262.11    1.37  261.98    9.77   261.8   31.26  261.44   38.59  261.46
   45.27  261.24   53.12  260.59   59.21  260.52   65.69  260.87    79.5  260.94
   86.08  260.65   96.75  259.11   101.9  258.96  116.86  258.94  150.11  258.51
  165.41  258.16  191.23  257.99   204.3  258.18  210.39  258.47  218.95  259.33
  228.17  259.52  235.07  258.84     236  258.65  258.57  258.71  260.48  259.05
  284.32  259.49  314.01  259.45  338.19  260.05  360.34   261.1  386.31  261.55
#Mann= 3 , 0 , 0
       0    .125       0     236    .055       0  258.57    .125       0
Bank Sta=236,258.57
XS Rating Curve= 0
Exp/Cntr=.3,.1

Type RM Length L Ch R = 1 ,3871.772,289.92,275.61,247.18
XS GIS Cut Line= 2
      1909905.17      435055.554     1909631.975      434658.979
#Sta/Elev= 30
       0  261.95   17.44  261.76   39.46  261.21   79.13  261.05   90.35  260.78
  139.68  260.37  175.63  259.73  192.63  260.27  200.24  260.31  207.37  260.14
  213.03  259.68  218.41  258.99  224.26   258.7   277.2  259.03  283.87  258.88
  300.46   257.5  304.49  255.89  307.74  255.13  309.44  255.85  310.12  257.29
  317.91  258.16  324.65  258.27  339.43  257.93  370.65  258.13  420.67  259.18
  441.06  259.25  454.04  259.76  475.11   259.9  480.69   260.1   491.7  260.88
#Mann= 3 , 0 , 0
       0    .125       0  304.49    .055       0  309.44    .125       0
Bank Sta=304.49,309.44
XS Rating Curve= 0
Exp/Cntr=.5,.3

Type RM Length L Ch R = 1 ,3596.163,135.83,130.02,135.77
#Sta/Elev= 30
     285  259.95   289.9  259.73  296.84  258.96  302.88  258.64  310.02  258.03
  315.49  257.76  327.63   257.7  340.33  257.47  343.54   254.7  344.54     253
  352.05  253.03  352.45  254.92  359.51  259.09  361.75  259.33  370.39  259.37
  379.45   259.6  386.94  258.29  391.07  257.96  408.05  257.06  409.66   257.1
  420.01  258.99  426.15  259.59  434.05  259.78  437.74  259.64  450.77  258.78
  456.28  258.58  486.96   258.8   517.5  259.46  527.34  259.78   548.5  260.07
#Mann= 3 , 0 , 0
     285    .125       0  344.54    .055       0  352.05    .125       0
#XS Ineff= 2 , 0
       0  343.84     260  352.37       0     260
Permanent Ineff=
       F       F
Bank Sta=344.54,352.05
XS Rating Curve= 0
Exp/Cntr=.5,.3

Type RM Length L Ch R = 2 ,3500    ,,,
BEGIN DESCRIPTION:
US 401; structure from NCDOT small pipes database 46 2010
END DESCRIPTION:
Bridge Culvert--1,0,-1,-1, 0
Deck Dist Width WeirC Skew NumUp NumDn MinLoCord MaxHiCord MaxSubmerge Is_Ogee
51.83,25.6,2.6,0, 2, 2, , , .95, 0, 1.5,1.5,,
       0     800
     260     260
                
       0     800
     260     260
                
BR Coef=-1 , 0 , 0 ,, 0 ,,,.8,0,,0,
WSPro=,,,, 1 ,,,, 0 ,,,, 0 ,,,,-1 ,-1 ,-1 , 0 , 0 , 0 , 0 , 0
Culvert=1,5,,25.6,.03,.5,1,2,1,253.2,348,253,351,Culvert #1  , 0 ,51.83
Culvert Bottom n=.03
BC Design=,, 0 ,, 0 ,,,,,,

Type RM Length L Ch R = 1 ,3466.146,589.09,638.67,676.8
XS GIS Cut Line= 2
     1910329.524       434824.09     1909780.052      434334.342
#Sta/Elev= 30
       0  260.09   21.44  259.66    36.8   259.7   114.6   258.8  176.71  257.42
   249.9  257.49  279.95  256.19  295.81  258.33  303.46  256.55  306.31  257.33
  311.24  258.09  319.81  258.36  328.67  257.99  335.08  257.45  341.86   257.4
  347.67  253.12  357.68   253.1  358.94  257.35  364.68   257.9  378.06  258.68
  391.64  258.64   413.3  259.49  423.93  259.35  443.85  258.55  452.88  258.52
  530.81  259.23  605.85  259.26  624.17  259.55  665.78  259.38  736.05  259.99
#Mann= 3 , 0 , 0
       0    .125       0  347.67    .055       0  357.68    .125       0
#XS Ineff= 2 , 0
       0  340.39     260   359.5       0     260
Permanent Ineff=
       F       F
Bank Sta=347.67,357.68
XS Rating Curve= 0
Exp/Cntr=.5,.3

Type RM Length L Ch R = 1 ,2827.475,529.46,515.59,486.33
XS GIS Cut Line= 3
     1910744.586      434606.103     1910658.661      434332.907
     1910634.426      434271.218
#Sta/Elev= 30
       0     258    10.3  257.78   25.13  257.72    96.3  256.59  111.97  256.05
  134.61  255.69  142.05  255.71  157.44  256.07  173.66  257.14  181.69   256.3
  193.01  254.55  198.48  254.29  202.28   254.2  205.67   254.4  213.63  254.49
   221.5  253.85  229.64  254.93  247.46  254.91  255.26  253.46  261.84  253.06
  267.11  253.56  268.42  254.47  271.05  255.48  275.02   255.7  289.85  256.17
  307.21  256.36  323.41  257.05  338.09  257.16  348.37  257.88  352.67  258.03
#Mann= 3 , 0 , 0
       0    .125       0  255.26    .055       0  267.11    .125       0
Bank Sta=255.26,267.11
XS Rating Curve= 0
Exp/Cntr=.3,.1

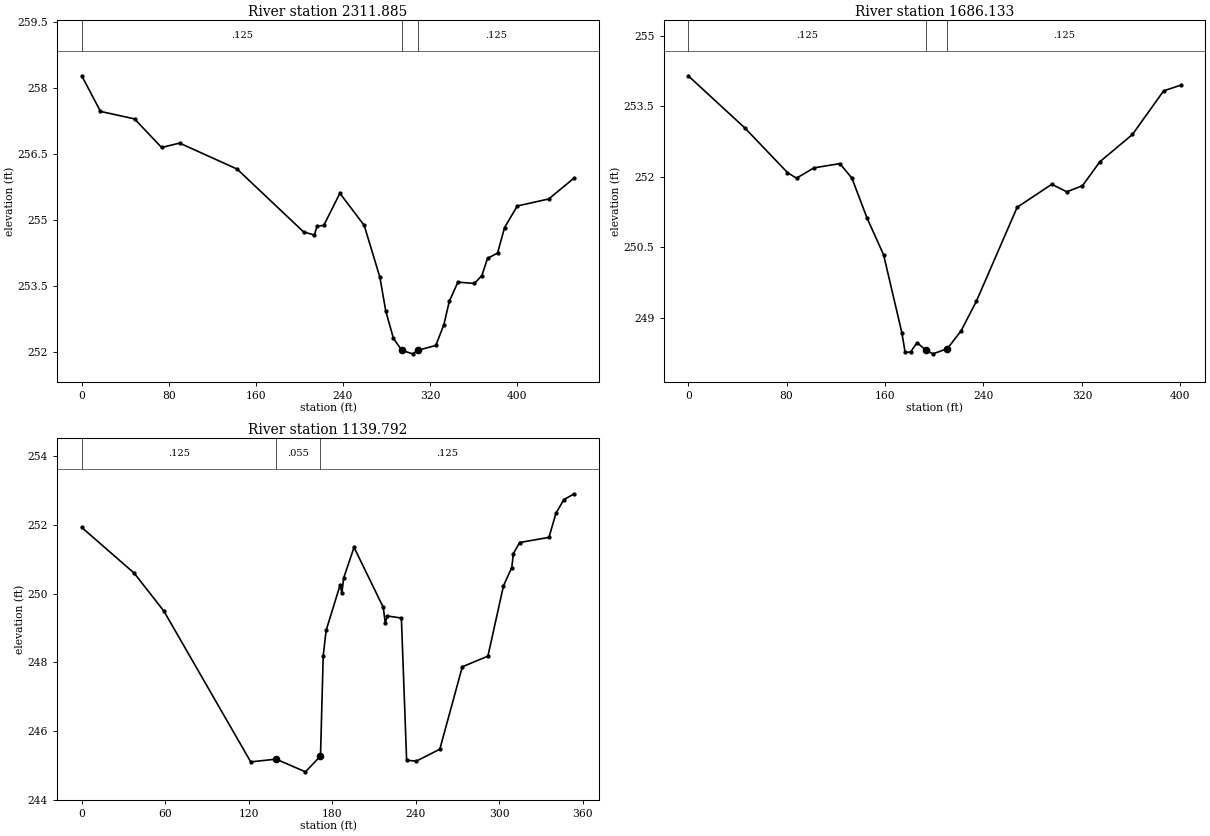
Type RM Length L Ch R = 1 ,2311.885,614.7,625.75,642.48
XS GIS Cut Line= 3
     1911127.835      434328.985     1911115.133       434104.58
     1910962.707      433935.217
#Sta/Elev= 30
       0  258.28   17.24  257.47   48.51   257.3   73.39  256.65   89.91  256.75
  142.76  256.16  203.91  254.73  213.83  254.66  216.12  254.86  222.43  254.88
  237.21  255.61  259.54  254.88  273.97   253.7  279.38  252.93  286.43  252.31
  294.08  252.04  304.07  251.96  308.76  252.04  325.32  252.15  332.74  252.62
   337.7  253.15  345.64  253.59  360.82  253.56   367.7  253.74  372.85  254.13
  382.07  254.25  388.53  254.83  400.18  255.32  429.07  255.48  452.62  255.96
#Mann= 3 , 0 , 0
       0    .125       0  294.08    .055       0  308.76    .125       0
Bank Sta=294.08,308.76
XS Rating Curve= 0
Exp/Cntr=.3,.1

Type RM Length L Ch R = 1 ,1686.133,558.09,546.34,542.26
XS GIS Cut Line= 3
     1911595.017      433777.704       1911445.2      433495.695
     1911385.714      433440.616
#Sta/Elev= 26
       0  254.15   46.01  253.04   80.66  252.09   88.04  251.97  102.25  252.19
  123.31  252.28  133.09  251.97  145.38  251.12  158.81  250.34  173.67  248.68
  176.34  248.26  180.79  248.27     186248.4673  193.22  248.31  198.93  248.23
  210.64  248.34  221.83  248.72  234.25  249.35   267.4  251.35  295.52  251.84
  307.74  251.68  320.49  251.81  334.64  252.32  361.11   252.9  386.49  253.83
   400.4  253.95
#Mann= 3 , 0 , 0
       0    .125       0  193.22    .055       0  210.64    .125       0
Bank Sta=193.22,210.64
XS Rating Curve= 0
Exp/Cntr=.3,.1

Type RM Length L Ch R = 1 ,1139.792,0,0,0
XS GIS Cut Line= 2
     1912038.023      433428.269     1911840.634      433134.482
#Sta/Elev= 30
       0  251.93   37.64   250.6   59.08  249.49  121.42   245.1  139.63  245.18
  160.76  244.81  171.56  245.27  173.51  248.19  175.61  248.93  185.64  250.25
  186.96  250.02  188.16  250.45  195.65  251.35  216.68   249.6  218.07  249.15
  219.66  249.35  229.68  249.29  233.44  245.15  240.33  245.12   257.3  245.47
  273.46  247.87  291.85  248.18  303.05  250.23  308.98  250.76  310.19  251.17
  314.62  251.49  335.72  251.64  340.72  252.34   346.4  252.74  353.94  252.91
#Mann= 3 , 0 , 0
       0    .125       0  139.63    .055       0  171.56    .125       0
Bank Sta=139.63,171.56
XS Rating Curve= 0
Exp/Cntr=.3,.1

River Reach=Toneys Trib     ,Tributary
Reach XY= 30
      1924271.51       446164.97      1924662.91       445401.74
      1925726.22       444847.25      1925928.45       444671.12
      1926372.04       444436.28      1927376.63        444136.2
       1928426.9       443653.47     1929072.072      442949.612
     1929373.208      442812.889     1929498.681      442567.134
       1929508.2      442403.587     1929446.761      442304.939
     1929483.971      442244.365     1929399.168      442098.124
        1929363.       441637.75      1929157.51       440802.76
      1929359.74       440189.57      1929438.02       440104.76
      1929353.21       440026.48      1929496.75       439752.46
      1930269.75       438813.14      1930276.27       438702.24
       1930171.9        438578.3       1930383.9       437997.72
      1930396.95       437815.06      1930162.11       436647.38
       1930188.2       435714.54      1930478.49       434631.66
      1930473.72      434235.307      1930081.74      433326.812

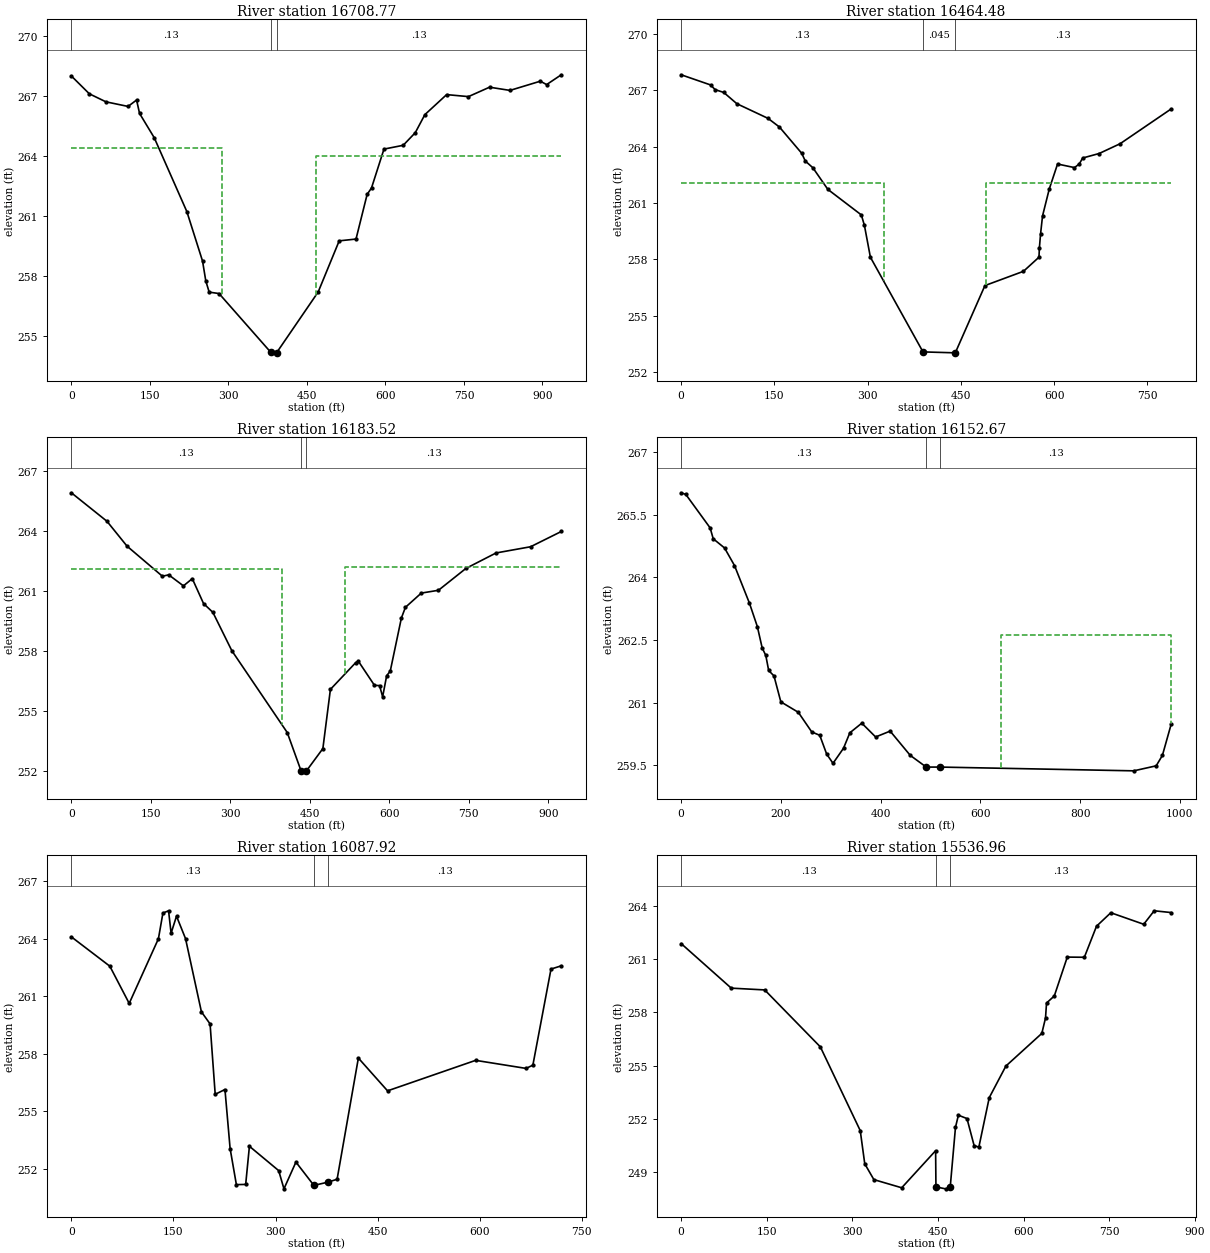
Type RM Length L Ch R = 1 ,16708.77,251.95,244.29,231.99
XS GIS Cut Line= 3
     1924624.264      446335.197     1924168.512      446015.085
     1923799.569      445928.275
#Sta/Elev= 30
       0  267.98   34.38  267.09   66.05  266.69  108.31  266.46  124.62  266.78
  130.31  266.11  158.31   264.9  220.66  261.21  250.63  258.74  256.84  257.75
  263.29  257.19  282.14  257.12  381.21  254.18  391.98  254.16  471.56   257.2
  511.68  259.75   543.8  259.84  565.06  262.07  573.41  262.39   597.2  264.33
  633.97  264.52  657.04  265.15  675.34  266.05  716.93  267.05  758.56  266.95
  798.91  267.42  837.92  267.26  895.96  267.72  907.94  267.55  935.96  268.04
#Mann= 3 , 0 , 0
       0     .13       0  381.21    .045       0  391.98     .13       0
#XS Ineff= 2 , 0
           287.4  264.38  466.54             264
Permanent Ineff=
       F       F
Bank Sta=381.21,391.98
XS Rating Curve= 0
Exp/Cntr=.3,.1

Type RM Length L Ch R = 1 ,16464.48,294.4,280.96,279.53
XS GIS Cut Line= 4
     1924778.086      446154.309     1924552.473      445964.186
     1924288.835      445827.297     1924093.642      445809.552
#Sta/Elev= 30
       0  267.83   47.21  267.29   54.62  267.04   68.45  266.89   89.57  266.29
  139.71  265.51  158.04  265.05  193.94  263.65  199.64  263.24  211.88  262.88
  235.93  261.73  289.84  260.37  294.79  259.81  304.37  258.12  388.98  253.08
  440.94  253.03  488.61  256.61  550.63  257.37  575.54  258.12  576.24  258.62
  578.08  259.35   581.3  260.32   592.1  261.75  605.44  263.08  632.68  262.89
  640.29  263.08  645.89   263.4  672.38  263.64  706.06  264.16   788.1  266.01
#Mann= 3 , 0 , 0
       0     .13       0  388.98    .045       0  440.94     .13       0
#XS Ineff= 2 , 0
          325.98  262.05  489.76          262.05
Permanent Ineff=
       F       F
Bank Sta=388.98,440.94
XS Rating Curve= 0
Exp/Cntr=.3,.1

Type RM Length L Ch R = 1 ,16183.52,30.99,30.85,26.11
XS GIS Cut Line= 4
      1924966.72      445879.756     1924738.857      445726.762
     1924410.083      445590.044     1924143.157      445713.742
#Sta/Elev= 30
       0  265.89    67.2  264.47   105.1  263.23  171.84  261.73  183.77   261.8
  211.55  261.25  228.26  261.61  249.48  260.37  267.11  259.93  302.86  258.02
  407.48  253.94  433.56  252.03  443.77  252.03  474.73  253.14  488.95  256.09
  536.56  257.42   541.6   257.5  572.15  256.29  581.75  256.28  587.54  255.72
  595.11  256.77  601.89     257  622.94  259.65  630.53  260.18  660.47  260.89
  692.86  261.03  744.75  262.12  801.59  262.89  866.79   263.2  924.72  263.96
#Mann= 3 , 0 , 0
       0     .13       0  433.56    .045       0  443.77     .13       0
#XS Ineff= 2 , 0
          397.64  262.07  515.75          262.17
Permanent Ineff=
       F       F
Bank Sta=433.56,443.77
XS Rating Curve= 0
Exp/Cntr=.3,.1

Type RM Length L Ch R = 1 ,16152.67,72.59,64.74,69.34
XS GIS Cut Line= 6
      1924998.62      445850.112      1924736.54      445693.656
     1924564.509      445620.414      1924513.41      445608.491
     1924189.971       445462.26     1924151.946       445452.12
#Sta/Elev= 30
       0  266.02    9.36  265.98    58.1  265.18   64.29  264.92   87.02   264.7
  106.94  264.28  136.92  263.38  152.76  262.82  162.45  262.31  169.72  262.13
  175.48  261.77  186.14  261.64  199.88  261.02  234.91  260.77   261.9   260.3
  277.93  260.22  291.81  259.77  304.51  259.55  325.57  259.91   338.3  260.28
  362.26  260.51  389.99  260.18   419.1  260.32  459.39  259.74  491.51  259.46
  519.44  259.46  907.62  259.37  952.66  259.49  965.12  259.74  982.56  260.48
#Mann= 3 , 0 , 0
       0     .13       0  491.51    .045       0  519.44     .13       0
#XS Ineff= 2 , 0
                          641.73          262.62
Permanent Ineff=
       F       F
Bank Sta=491.51,519.44
XS Rating Curve= 0
Exp/Cntr=.3,.1

Type RM Length L Ch R = 1 ,16087.92,449.28,550.96,560.92
XS GIS Cut Line= 4
     1924940.678      445752.804     1924748.622      445622.596
     1924331.958      445466.347 1924319.3028124  445425.3337723
#Sta/Elev= 30
       0  264.09   56.55  262.56   85.01  260.62  127.93  263.99  134.54  265.33
  142.85  265.45  146.58  264.28  154.52  265.17  167.77     264  191.13  260.18
  203.85  259.55  211.39  255.88  225.72  256.13   233.3  253.05   242.5  251.17
  256.17  251.18  261.66  253.17  304.68   251.9  312.41  250.95     330252.3446
   356.4  251.13  377.22   251.3  390.52  251.45  421.76  257.77  464.65  256.06
  594.08  257.65  668.21  257.23   678.2   257.4  704.83  262.41  719.95  262.58
#Mann= 3 , 0 , 0
       0     .13       0   356.4    .045       0  377.22     .13       0
Bank Sta=356.4,377.22
XS Rating Curve= 0
Exp/Cntr=.3,.1

Type RM Length L Ch R = 1 ,15536.96,327.71,402.06,418.13
XS GIS Cut Line= 4
     1925231.934       445575.61     1925058.314       445315.18
     1924879.268      445071.027     1924814.161      444837.725
#Sta/Elev= 30
       0  261.87   87.72  259.36  146.27  259.26  243.72  256.05   313.6  251.33
   321.5  249.46  337.46  248.57  386.19  248.11  445.59   250.2  446.16  248.16
  462.94  248.05  471.11  248.13  480.38  251.52  485.48   252.2  500.52  252.01
  512.98  250.49   521.3   250.4  539.52  253.19  568.66  254.97  631.57  256.81
  638.06  257.68  639.81  258.52  653.43  258.92  676.16  261.11  706.05   261.1
  727.35  262.85   752.4  263.61     810  262.96  828.38  263.72  857.98  263.62
#Mann= 3 , 0 , 0
       0     .13       0  446.16    .045       0  471.11     .13       0
Bank Sta=446.16,471.11
XS Rating Curve= 0
Exp/Cntr=.3,.1