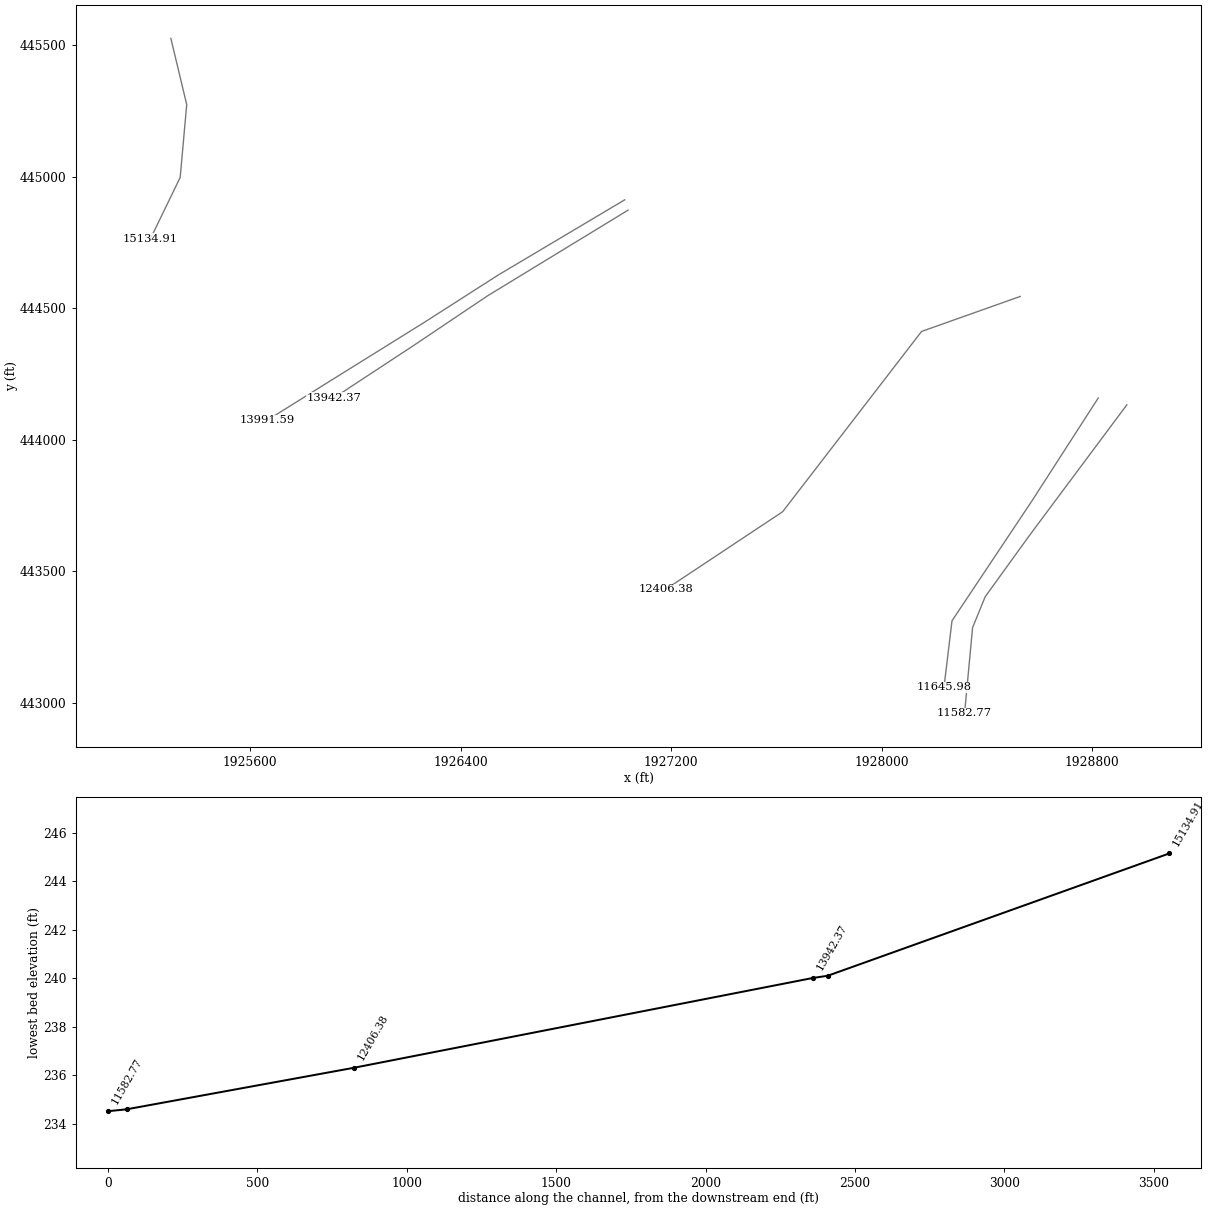
HEC-RAS study upraft.prj: Upper Raft Swamp

--- upraft.g04 (geometry) --- (continued)

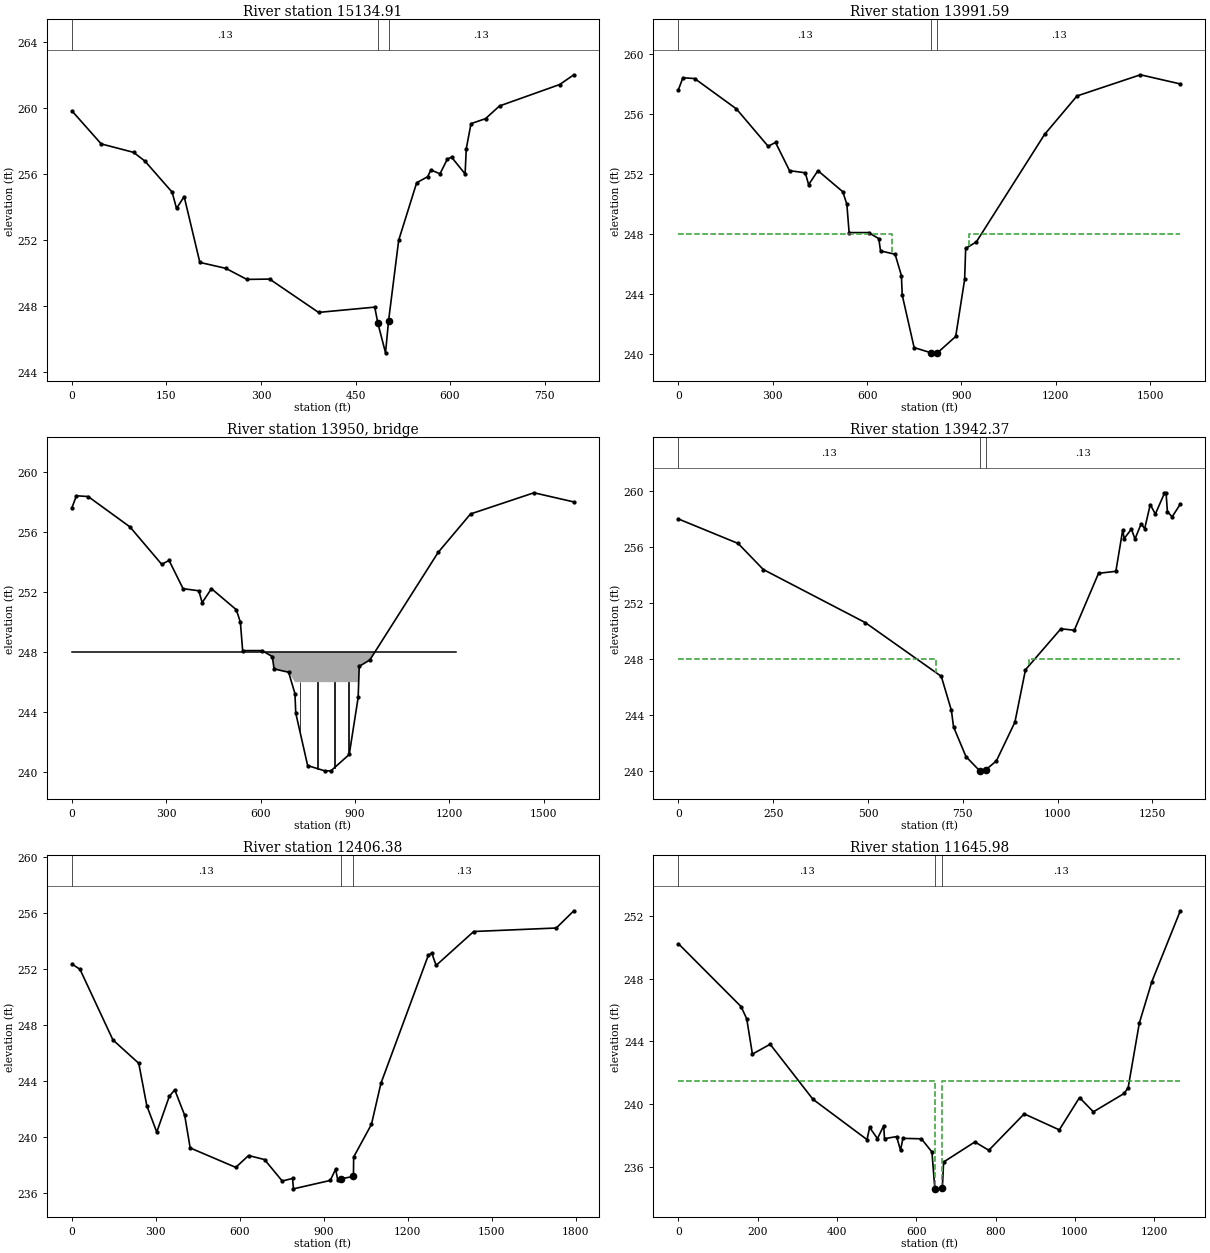
Type RM Length L Ch R = 1 ,15134.91,1227.82,1143.32,1067.68
XS GIS Cut Line= 4
     1925299.696      445524.919     1925359.965      445273.206
     1925335.149      444996.676       1925221.7      444762.689
#Sta/Elev= 30
       0   259.8   46.48   257.8   97.75  257.29  115.79  256.76  158.93  254.88
  165.97  253.89  178.08  254.61  202.96  250.62  244.15  250.26  277.56  249.59
  313.68  249.61  391.33  247.59   480.5  247.91  485.48  246.94  497.64  245.14
  502.45  247.08  518.51  251.96  547.09  255.45  564.39  255.81  569.64  256.22
   584.1  255.99  595.76  256.88  602.43     257   623.9  255.98  625.81  257.52
  633.32  259.03  656.32  259.33  678.52   260.1  774.04   261.4  796.51  261.99
#Mann= 3 , 0 , 0
       0     .13       0  485.48    .045       0  502.45     .13       0
Bank Sta=485.48,502.45
XS Rating Curve= 0
Exp/Cntr=.5,.3

Type RM Length L Ch R = 1 ,13991.59,66.76,49.22,56.63
XS GIS Cut Line= 5
     1927023.474      444911.514     1926541.679      444625.041
     1926263.887       444447.08     1925873.242      444204.013
     1925664.898      444073.798
#Sta/Elev= 30
       0  257.61   14.27   258.4   51.57  258.35  184.46  256.33   285.5  253.84
  308.83   254.1  353.41  252.22  403.41  252.08  414.11  251.29  443.68  252.22
  522.68  250.82  535.66  249.99  542.88   248.1   604.6   248.1  637.23   247.7
  642.81  246.88  689.08  246.66  709.19  245.24  711.81  243.94  749.61  240.45
  803.78   240.1  823.69   240.1  881.89  241.19  910.24  244.98  913.59  247.05
  947.52  247.48 1164.48  254.63 1267.59  257.19 1469.42   258.6 1596.22  257.99
#Mann= 3 , 0 , 0
       0     .13       0  803.78    .045       0  823.69     .13       0
#XS Ineff= 2 , 0
       0  679.62     248     925       0     248
Permanent Ineff=
       F       F
Bank Sta=803.78,823.69
XS Rating Curve= 0
Exp/Cntr=.5,.3

Type RM Length L Ch R = 3 ,13950   ,,,
BEGIN DESCRIPTION:
US401; structure 3 from NCDOT database
END DESCRIPTION:
Bridge Culvert--1,0,-1,-1, 0
Deck Dist Width WeirC Skew NumUp NumDn MinLoCord MaxHiCord MaxSubmerge Is_Ogee
10.75,31.4,2.6,0, 9, 9, , , .95, 0, 1.5,1.5,,
       0  676.82  679.62     680     724     881     925  925.74 1221.88
     248     248     248     248     248     248     248     248     248
                             246     246     246     246
       0  676.82  679.62     680     724     881     925  925.74 1221.88
     248     248     248     248     248     248     248     248     248
                             246     246     246     246
Pier Skew, UpSta & Num, DnSta & Num=  ,725, 2 ,725, 2 , 0 , 0 , 0 ,,
       2       2
     244     255
       2       2
     244     255
Pier Skew, UpSta & Num, DnSta & Num=  ,780, 2 ,780, 2 , 0 , 0 , 0 ,,
       2       2
     244     255
       2       2
     244     255
Pier Skew, UpSta & Num, DnSta & Num=  ,835, 2 ,835, 2 , 0 , 0 , 0 ,,
       2       2
     244     255
       2       2
     244     255
Pier Skew, UpSta & Num, DnSta & Num=  ,880, 2 ,880, 2 , 0 , 0 , 0 ,,
       2       2
     244     255
       2       2
     244     255
BR Coef=-1 , 1 , 0 ,, 0 ,,,.8,0,1.2,1,
WSPro=,,,, 1 ,,,, 0 ,,,, 0 ,,,,-1 ,-1 ,-1 , 0 , 0 , 0 , 0 , 0
BC Design=,, 0 ,, 0 ,,,,,,

Type RM Length L Ch R = 1 ,13942.37,1500.05,1535.99,1546.28
XS GIS Cut Line= 4
     1927036.496      444872.449     1926502.615      444546.912
     1926224.823      444360.271     1925920.988      444160.608
#Sta/Elev= 30
       0     258  157.47  256.25  223.83  254.39  492.61   250.6  693.17  246.76
  719.83  244.33  725.52  243.15  758.21  241.03  794.45  240.01   810.8  240.09
  838.52  240.72   887.4  243.49  915.22  247.23 1008.66  250.16 1043.92  250.05
 1107.93  254.12 1153.54  254.26 1171.64  257.21 1175.52   256.6  1194.6  257.28
 1203.95  256.57 1220.22  257.65 1229.58  257.31 1244.28  259.03 1257.65  258.35
  1281.7  259.84 1285.94  259.87 1289.48  258.53 1301.84  258.15 1323.54  259.06
#Mann= 3 , 0 , 0
       0     .13       0  794.45    .045       0   810.8     .13       0
#XS Ineff= 2 , 0
       0     680     248     925       0     248
Permanent Ineff=
       F       F
Bank Sta=794.45,810.8
XS Rating Curve= 0
Exp/Cntr=.5,.3

Type RM Length L Ch R = 1 ,12406.38,750.13,760.4,760.69
XS GIS Cut Line= 4
     1928525.625      444544.538     1928151.007      444411.609
      1927623.32      443726.823     1927180.223      443432.768
#Sta/Elev= 30
       0  252.36   28.74  251.98  146.46  246.94  238.84  245.27  267.48  242.25
  303.11  240.36  347.89  242.91  367.34  243.38  402.93  241.56  422.54  239.23
  585.59  237.84  631.32  238.69  688.23   238.4  751.48  236.87  788.32  237.05
  791.77  236.31  923.27  236.91  942.26  237.71  949.88  236.96  961.12  237.02
 1006.09   237.2 1006.81  238.58 1070.35  240.91 1104.24  243.84  1273.6  252.98
 1286.07  253.14  1301.5  252.26 1435.89  254.68 1730.96  254.93 1793.81  256.16
#Mann= 3 , 0 , 0
       0     .13       0  961.12    .045       0 1006.09     .13       0
Bank Sta=961.12,1006.09
XS Rating Curve= 0
Exp/Cntr=.5,.3

Type RM Length L Ch R = 1 ,11645.98,64.99,63.22,57.03
XS GIS Cut Line= 4
     1928822.204       444158.98     1928570.455      443768.335
      1928266.62      443312.583     1928236.237      443060.834
#Sta/Elev= 30
       0  250.23  158.11  246.22  172.33  245.44  186.66  243.19  231.39  243.82
  339.38  240.31   475.8  237.74   482.3  238.52  502.02   237.8  517.83  238.62
  519.87   237.8  550.36  237.93  560.28  237.06  566.29  237.82  612.91  237.79
  639.52  236.95  646.89   234.6  665.79  234.63  668.92  236.31  747.82  237.59
  782.99  237.06  872.26  239.38  960.79  238.36 1011.77  240.42 1046.75  239.51
 1124.28  240.68 1134.46  241.05 1162.66  245.17 1194.35  247.82 1266.06  252.33
#Mann= 3 , 0 , 0
       0     .13       0  646.89    .045       0  665.79     .13       0
#XS Ineff= 2 , 0
       0  646.89   241.5  665.79       0   241.5
Permanent Ineff=
       F       F
Bank Sta=646.89,665.79
XS Rating Curve= 0
Exp/Cntr=.5,.3

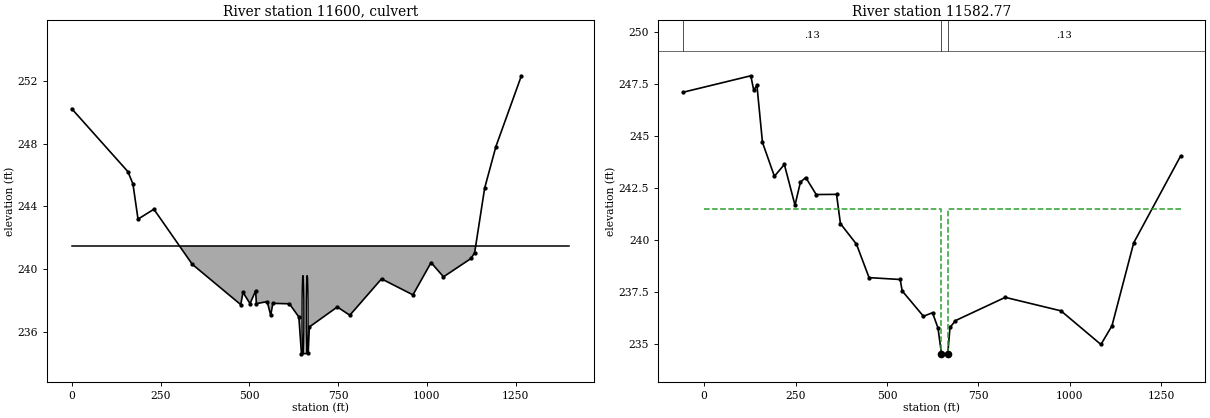
Type RM Length L Ch R = 2 ,11600   ,,,
BEGIN DESCRIPTION:
SR 1143; NCDOT small pipes data 46 2039
END DESCRIPTION:
Bridge Culvert--1,0,-1,-1, 0
Deck Dist Width WeirC Skew NumUp NumDn MinLoCord MaxHiCord MaxSubmerge Is_Ogee
32,20,2.6,0, 2, 2, , , .95, 0, 0,0,,
       0    1400
   241.5   241.5
                
       0    1400
   241.5   241.5
                
BR Coef=-1 , 0 , 0 ,, 0 ,,,.8,0,,0,
WSPro=,,,, 1 ,,,, 0 ,,,, 0 ,,,,-1 ,-1 ,-1 , 0 , 0 , 0 , 0 , 0
Multiple Barrel Culv=1,5,,20,.028,.5,1,1,1,234.6,234.5, 2,Culvert #1  , 0 ,32
     651     651     663     663
Culvert Bottom n=.028
BC Design=,, 0 ,, 0 ,,,,,,

Type RM Length L Ch R = 1 ,11582.77,584.91,573.54,518.74
XS GIS Cut Line= 5
      1928930.71      444132.937     1928561.774       443638.12
     1928392.495      443403.733     1928344.749       443286.54
     1928314.366      442961.002
#Sta/Elev= 30
     -57  247.12   127.6  247.91  135.53  247.22  144.31  247.45  159.51   244.7
  192.11  243.07  219.34  243.64  248.44  241.68  263.28  242.79  277.89  243.01
  306.46  242.19  362.04   242.2   372.7  240.79  416.58   239.8  450.99  238.19
  536.11   238.1  541.57  237.55  599.73  236.33  624.49   236.5   639.4  235.77
  649.08  234.52   666.2  234.53  672.29  235.79  687.31  236.12  823.45  237.24
  975.89  236.59  1085.1  234.97 1115.28  235.87 1174.81  239.87 1302.84  244.04
#Mann= 3 , 0 , 0
     -57     .13       0  649.08    .045       0   666.2     .13       0
#XS Ineff= 2 , 0
       0  649.08   241.5   666.2       0   241.5
Permanent Ineff=
       F       F
Bank Sta=649.08,666.2
XS Rating Curve= 0
Exp/Cntr=.5,.3