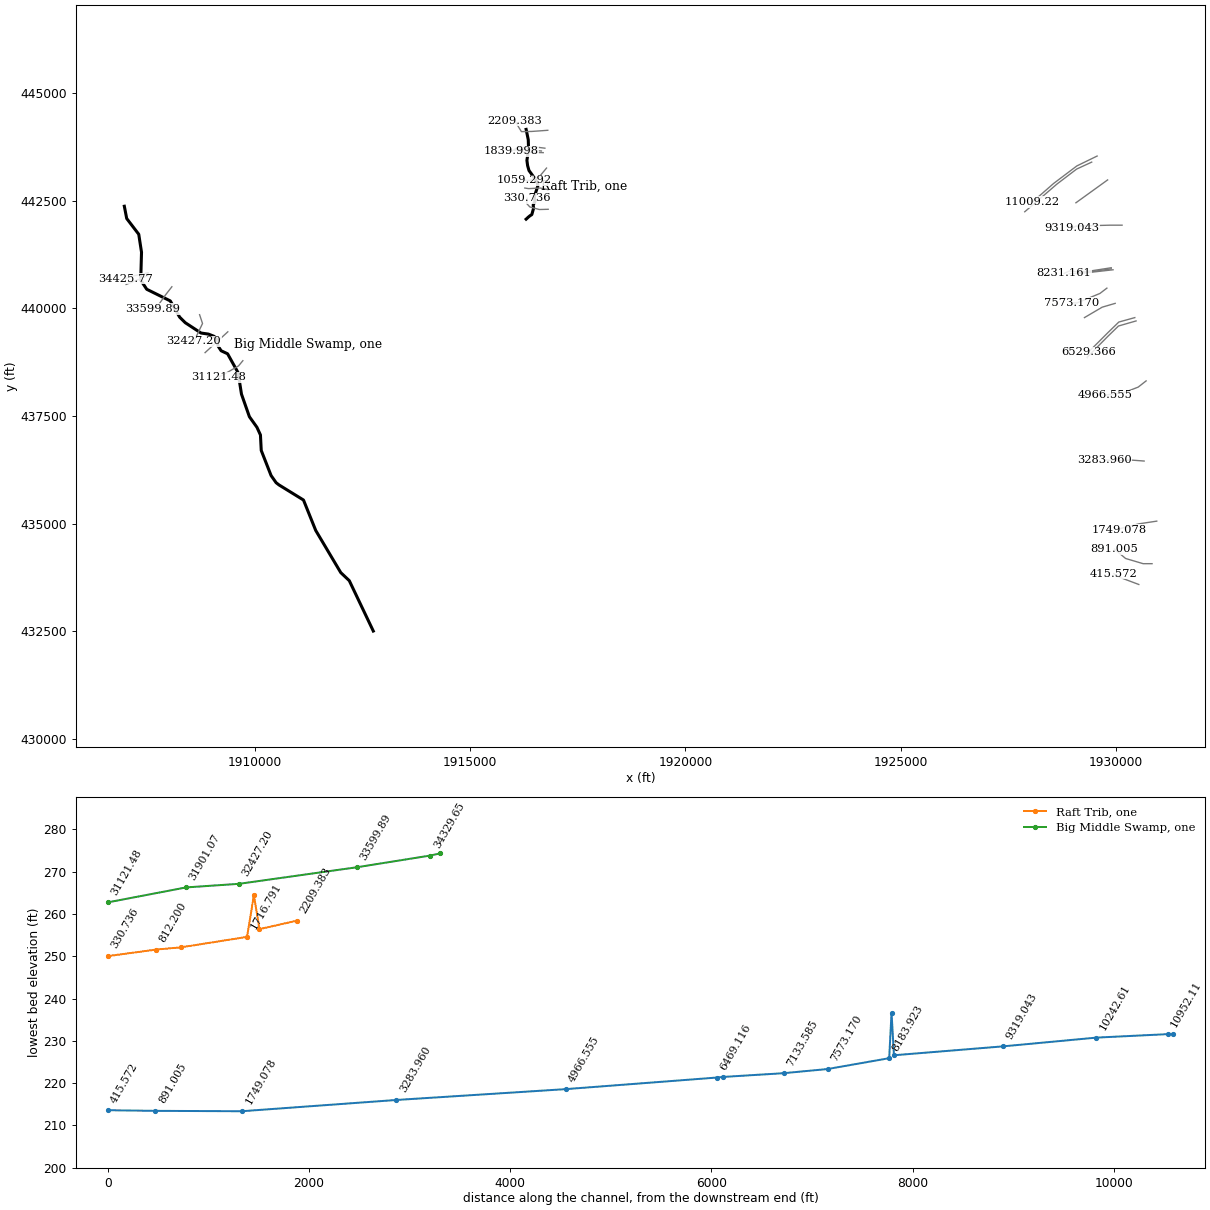
HEC-RAS study upraft.prj: Upper Raft Swamp

--- upraft.g04 (geometry) --- (continued)

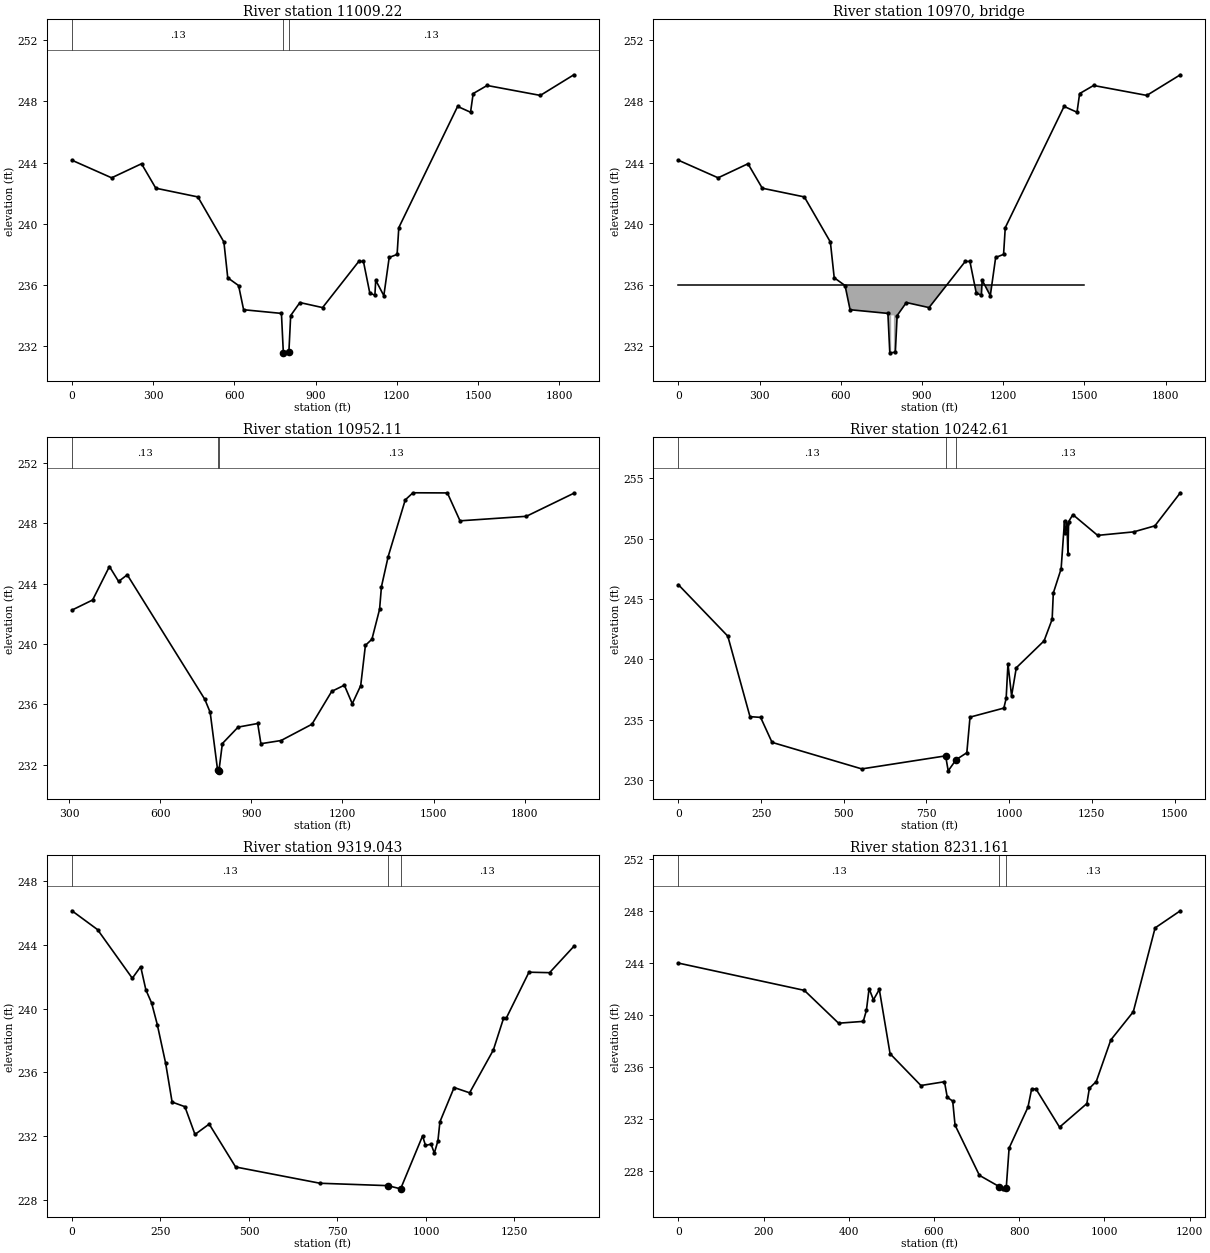
Type RM Length L Ch R = 1 ,11009.22,56.12,57.11,57.15
XS GIS Cut Line= 4
      1929562.73      443536.535     1929092.158      443307.129
     1928553.936      442901.256      1928059.83      442468.913
#Sta/Elev= 30
       0  244.15  146.58     243     257  243.92  309.79  242.32   465.2  241.75
  561.36   238.8  575.58  236.46  615.66  235.95  634.14  234.37   773.9  234.13
  780.93  231.55  801.37  231.59  808.03  233.99  842.12  234.84  925.84  234.51
 1059.61  237.53 1076.84  237.53 1100.37  235.46 1119.16  235.32 1122.23   236.3
 1152.21  235.29 1171.99  237.79 1201.21  237.99 1207.47  239.74 1424.71  247.67
 1472.53  247.29 1482.19  248.51 1533.75  249.04 1730.33  248.39 1854.17  249.74
#Mann= 3 , 0 , 0
       0     .13       0  780.93    .045       0  801.37     .13       0
Bank Sta=780.93,801.37
XS Rating Curve= 0
Exp/Cntr=.5,.3

Type RM Length L Ch R = 3 ,10970   ,,,
BEGIN DESCRIPTION:
opening size estimated using similar road class
END DESCRIPTION:
Bridge Culvert--1,0,-1,-1, 0
Deck Dist Width WeirC Skew NumUp NumDn MinLoCord MaxHiCord MaxSubmerge Is_Ogee
22,26,2.6,0, 4, 4, , , .95, 0, 0,0,,
       0     786     796    1500
     236     236     236     236
             234     234
       0     786     796    1500
     236     236     236     236
             234     234
BR Coef=-1 , 1 , 0 ,, 0 ,,,.8,0,1.2,1,
WSPro=,,,, 1 ,,,, 0 ,,,, 0 ,,,,-1 ,-1 ,-1 , 0 , 0 , 0 , 0 , 0
BC Design=,, 0 ,, 0 ,,,,,,

Type RM Length L Ch R = 1 ,10952.11,647.96,709.51,615.44
XS GIS Cut Line= 5
      1929436.26      443395.362     1929086.276      443233.601
     1928630.404       442886.55     1928103.946       442433.62
 1927881.7207478  442242.4319404
#Sta/Elev= 30
     309  242.24  377.04  242.91  432.43  245.13  462.68  244.14  491.12  244.58
  746.64  236.32  764.22  235.46  788.76  231.62  793.04  231.58  804.42  233.39
  856.22  234.48  920.77  234.72  931.31  233.38  997.66  233.59 1099.37  234.67
 1164.56  236.85 1206.14  237.26 1232.19  236.03 1259.98  237.23 1275.49   239.9
 1296.98  240.31 1322.14  242.29  1328.3  243.79 1350.46  245.79 1406.74  249.55
 1432.09  250.02 1545.44  250.01 1587.08  248.16 1805.55  248.46 1961.99  249.99
#Mann= 3 , 0 , 0
     309     .13       0  788.76    .045       0  793.04     .13       0
Bank Sta=788.76,793.04
XS Rating Curve= 0
Exp/Cntr=.5,.3

Type RM Length L Ch R = 1 ,10242.61,854.83,923.57,624.1
XS GIS Cut Line= 3
      1929805.96      442981.825 1929292.5075211   442611.596715
  1929070.250395  442451.3367532
#Sta/Elev= 30
       0  246.18  149.34  241.92   216.4  235.25  248.53  235.19  283.09  233.12
  554.49  230.92  807.93     232  815.75  230.76  839.47  231.68  872.06  232.26
   881.7  235.21     984  235.96  990.97  236.76  996.44  239.63 1007.39  236.97
 1021.61   239.3 1105.66  241.53 1130.06  243.32 1133.54  245.49 1157.21   247.5
 1167.46  251.48 1169.02  250.44 1174.87  251.23 1177.69  248.74 1179.92  251.41
 1192.65  251.99 1267.61  250.27 1376.58  250.56 1440.68  251.06  1517.6   253.8
#Mann= 3 , 0 , 0
       0     .13       0  807.93    .045       0  839.47     .13       0
Bank Sta=807.93,839.47
XS Rating Curve= 0
Exp/Cntr=.3,.1

Type RM Length L Ch R = 1 ,9319.043,1135.39,1087.88,1089.07
XS GIS Cut Line= 4
      1930141.58      441930.948     1929863.516      441930.948
     1929070.019      441910.602  1928972.427894  441858.5532609
#Sta/Elev= 30
       0  246.13   72.26  244.95  170.53   241.9  194.13  242.63  208.83  241.17
  225.05  240.35  241.01     239  264.67  236.57  282.91  234.14  319.01  233.85
  347.55  232.11  387.64  232.76  462.34  230.07   700.8  229.05  892.32   228.9
  928.38   228.7  990.44  232.02  998.57  231.42 1014.37   231.5 1023.62  230.94
 1033.76  231.71  1039.4   232.9 1079.47  235.05 1123.23  234.72 1190.27   237.4
 1218.96  239.38 1227.24  239.42 1290.89  242.28 1349.14  242.25 1417.71   243.9
#Mann= 3 , 0 , 0
       0     .13       0  892.32    .045       0  928.38     .13       0
Bank Sta=892.32,928.38
XS Rating Curve= 0
Exp/Cntr=.3,.1

Type RM Length L Ch R = 1 ,8231.161,18.73,23.89,20.65
BEGIN DESCRIPTION:
bridge losses added
END DESCRIPTION:
XS GIS Cut Line= 6
       1929890.1      440942.159     1929386.652      440864.524
     1929252.556      440855.114     1929057.294      440852.761
     1928927.903      440869.229 1928797.2180023  440811.1470836
#Sta/Elev= 30
       0  243.98  295.49  241.88  375.95  239.35  433.91  239.49  441.25  240.34
  447.55  242.02  457.73  241.15  471.55  241.95  496.79     237  569.17  234.55
  624.48  234.84  631.09  233.64  643.82  233.35   649.3   231.5  706.49  227.63
  753.63  226.75  762.59  226.59  769.41  226.64  776.21  229.73  820.45  232.88
  828.88  234.25   839.1  234.29  894.58  231.34  958.71  233.16  964.63  234.34
  980.66  234.85 1014.93  238.06 1067.68  240.23 1118.87  246.69 1178.07  248.01
#Mann= 3 , 0 , 0
       0     .13       0  753.63    .045       0  769.41     .13       0
Bank Sta=753.63,769.41
XS Rating Curve= 0
Exp/Cntr=.3,.1

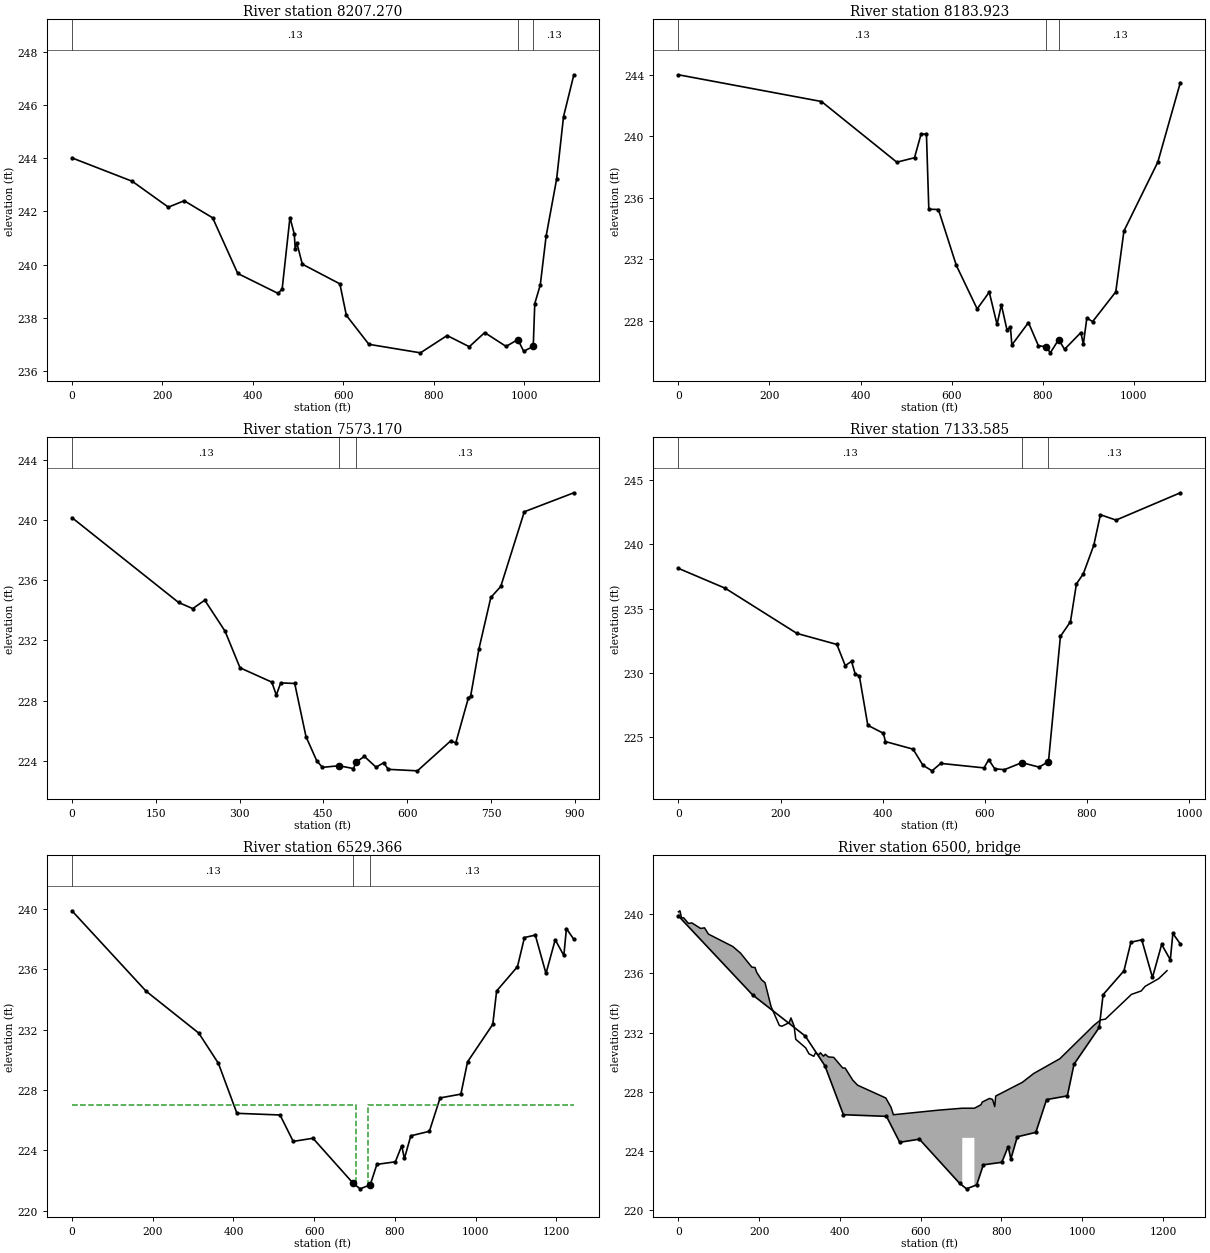
Type RM Length L Ch R = 1 ,8207.270,17.62,23.35,23.91
XS GIS Cut Line= 4
      1929891.61      440916.304     1929389.247      440846.871
     1929176.863      440830.534  1929096.627935  440832.4442251
#Sta/Elev= 30
       0  244.01  133.31  243.13     213  242.16  248.01   242.4  310.89  241.76
  366.39  239.67  455.61  238.92  464.52  239.09  481.72  241.77  491.38  241.15
  493.27   240.6     497  240.81  509.04  240.02  592.06  239.28  606.29   238.1
   656.1  237.01  770.07  236.69  828.96  237.34  877.93  236.92  912.08  237.45
  959.41  236.93  985.21  237.19  998.16  236.75 1019.32  236.93 1022.71  238.54
 1034.88  239.24 1047.77  241.07 1071.05  243.22 1086.26  245.56 1109.06  247.13
#Mann= 3 , 0 , 0
       0     .13       0  985.21    .045       0 1019.32     .13       0
Bank Sta=985.21,1019.32
XS Rating Curve= 0
Exp/Cntr=.3,.1

Type RM Length L Ch R = 1 ,8183.923,609.06,610.75,645.96
BEGIN DESCRIPTION:
dam
END DESCRIPTION:
XS GIS Cut Line= 5
      1929932.44      440895.108     1929391.357      440833.941
     1929158.454      440808.063     1928956.133      440810.415
 1928912.3092038  440799.8975572
#Sta/Elev= 30
       0     244  314.17  242.26  479.59  238.31  518.46   238.6  533.04  240.16
  544.68  240.12  549.87  235.25  570.96  235.23  610.31  231.59  656.04  228.76
   682.6  229.85  699.71  227.75  709.21  229.03  721.47   227.4  729.13  227.57
  732.21  226.41  768.69  227.87  790.41  226.37  807.52  226.29  816.69   225.9
  834.95  226.76  847.96  226.13  883.81  227.22  889.21  226.46   896.9  228.17
  909.53  227.93  960.45  229.87  978.33  233.83 1052.79  238.32 1102.17  243.49
#Mann= 3 , 0 , 0
       0     .13       0  807.52    .045       0  834.95     .13       0
Bank Sta=807.52,834.95
XS Rating Curve= 0
Exp/Cntr=.3,.1

Type RM Length L Ch R = 1 ,7573.170,353.1,439.58,364.61
XS GIS Cut Line= 4
       1929789.2      440468.961      1929627.44      440345.434
     1929086.276       440121.91     1928977.455      440130.733
#Sta/Elev= 30
       0  240.15  190.74  234.52   216.2  234.11  237.68  234.67     274  232.61
   300.8  230.18  357.65  229.23  365.75  228.37  373.63  229.18  398.65  229.14
  418.85  225.61  438.18     224  448.32  223.57  478.04  223.68  503.78  223.49
   508.4  223.91  523.28   224.3  544.28  223.58  557.85  223.88  566.01  223.44
  618.24  223.34  677.54  225.32  686.99   225.2  709.44  228.18  713.52   228.3
  728.38  231.44  749.63  234.85  767.41  235.58  809.55  240.54  898.22   241.8
#Mann= 3 , 0 , 0
       0     .13       0  478.04    .045       0   508.4     .13       0
Bank Sta=478.04,508.4
XS Rating Curve= 0
Exp/Cntr=.3,.1

Type RM Length L Ch R = 1 ,7133.585,588.16,604.22,612.2
XS GIS Cut Line= 3
      1929981.62      440115.087     1929680.207      440026.866
 1929267.8789579  439784.5320498
#Sta/Elev= 30
       0  238.13   91.66  236.58  232.02  233.06  310.28   232.2  326.62  230.55
  338.98  230.88  346.42  229.86  354.24  229.76  370.83   225.9  401.16  225.28
  405.42  224.63  459.46  224.04  478.66  222.79  496.61  222.35  513.62  222.93
  598.42  222.58  607.48  223.22  619.39  222.51  638.15  222.44  672.52  222.99
  706.16  222.64   724.6  223.07  747.95  232.83  767.63  233.97  779.33  236.92
  792.75   237.7   813.3  239.93  826.28  242.31  856.87  241.89  982.74  244.02
#Mann= 3 , 0 , 0
       0     .13       0  672.52    .045       0   724.6     .13       0
Bank Sta=672.52,724.6
XS Rating Curve= 0
Exp/Cntr=.5,.3

Type RM Length L Ch R = 1 ,6529.366,67.69,60.25,60.11
XS GIS Cut Line= 5
      1930437.43      439784.258     1930066.174      439681.334
     1929812.539       439435.05     1929455.979       439078.49
 1929356.3617932  438978.8727932
#Sta/Elev= 30
       0  239.87  183.49  234.55   314.1  231.77  362.71  229.77  408.61  226.46
  515.31  226.35  548.04   224.6  596.85  224.81  696.38  221.83  713.73  221.46
   738.8  221.73  755.23  223.08  800.98  223.25  816.69  224.31  823.35  223.47
  839.26  224.97  885.22  225.27  911.77  227.48  963.23  227.73  979.82  229.87
 1042.25  232.35 1051.78  234.56 1103.42  236.17  1120.7   238.1 1147.55  238.26
 1174.04  235.72 1196.87  237.95 1218.28  236.91  1224.6  238.69 1243.05  237.98
#Mann= 3 , 0 , 0
       0     .13       0  696.38    .045       0   738.8     .13       0
#XS Ineff= 2 , 0
       0     703     227     733       0     227
Permanent Ineff=
       F       F
Bank Sta=696.38,738.8
XS Rating Curve= 0
Exp/Cntr=.5,.3

Type RM Length L Ch R = 3 ,6500    ,,,
BEGIN DESCRIPTION:
Old Maxton Rd (SR1116); opening size estimated using similar road class and ortho photo
END DESCRIPTION:
Bridge Culvert--1,0,-1,-1, 0
Deck Dist Width WeirC Skew NumUp NumDn MinLoCord MaxHiCord MaxSubmerge Is_Ogee
20,26,2.6,0, 60, 60, , , .95, 0, 0,0,,
       0    3.76    7.97   12.82   24.69   33.46   54.92   64.69   74.14  134.64
  153.61  181.75  189.81  193.82  205.65  214.48  229.45     250  256.36  274.14
  278.68  286.38   290.6  315.22  323.34   335.3  339.61  347.52  351.61  359.41
  363.76  371.43  384.67  406.71  412.86   431.9  443.94  513.58  526.62  532.43
  644.56     703     733  749.18  752.69  770.56  778.05  783.39  785.83  851.96
  879.78  944.72 1029.23 1045.22 1057.51 1122.09 1146.19 1155.77 1189.35 1210.15
  240.15  240.22  239.73  239.75  239.37   239.4  239.03  239.07  238.65  237.81
  237.37  236.42  236.39  236.07  235.57  235.37  233.76  232.48  232.43  232.67
  232.99  232.46  231.55  230.97  230.57   230.4  230.64   230.5  230.64  230.41
  230.54  230.36  230.33  229.62  229.61  228.79  228.45  227.59  226.96  226.46
  226.77   226.9   226.9  227.13  227.32  227.56  227.49  227.01  227.72  228.65
  229.24  230.24   232.5  232.85  232.91  234.58  234.81  235.12  235.64  236.18
                                                                                
                                                                                
                                                                                
                                                                                
           224.9   224.9
                                                                                
       0    3.76    7.97   12.82   24.69   33.46   54.92   64.69   74.14  134.64
  153.61  181.75  189.81  193.82  205.65  214.48  229.45     250  256.36  274.14
  278.68  286.38   290.6  315.22  323.34   335.3  339.61  347.52  351.61  359.41
  363.76  371.43  384.67  406.71  412.86   431.9  443.94  513.58  526.62  532.43
  644.56     703     733  749.18  752.69  770.56  778.05  783.39  785.83  851.96
  879.78  944.72 1029.23 1045.22 1057.51 1122.09 1146.19 1155.77 1189.35 1210.15
  240.15  240.22  239.73  239.75  239.37   239.4  239.03  239.07  238.65  237.81
  237.37  236.42  236.39  236.07  235.57  235.37  233.76  232.48  232.43  232.67
  232.99  232.46  231.55  230.97  230.57   230.4  230.64   230.5  230.64  230.41
  230.54  230.36  230.33  229.62  229.61  228.79  228.45  227.59  226.96  226.46
  226.77   226.9   226.9  227.13  227.32  227.56  227.49  227.01  227.72  228.65
  229.24  230.24   232.5  232.85  232.91  234.58  234.81  235.12  235.64  236.18
                                                                                
                                                                                
                                                                                
                                                                                
           224.9   224.9
                                                                                
BR Coef=-1 , 1 , 0 ,, 0 ,,,.8,0,1.2,1,
WSPro=,,,, 1 ,,,, 0 ,,,, 0 ,,,,-1 ,-1 ,-1 , 0 , 0 , 0 , 0 , 0
BC Design=,, 0 ,, 0 ,,,,,,

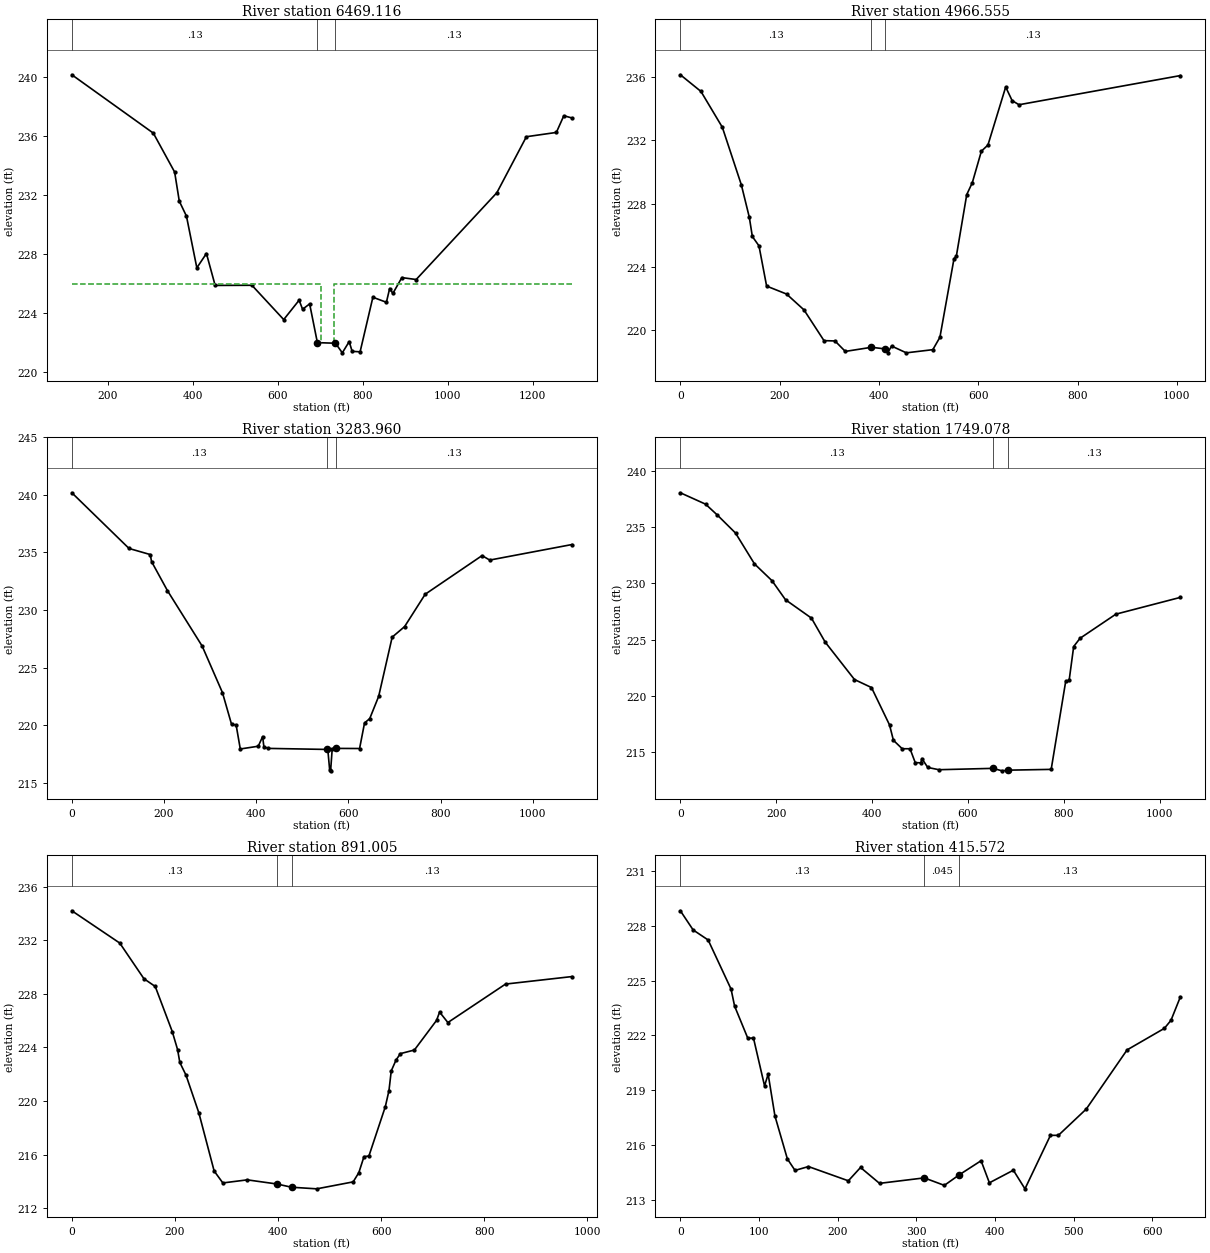
Type RM Length L Ch R = 1 ,6469.116,1528.27,1502.56,1410.7
XS GIS Cut Line= 5
      1930466.84      439707.065     1930058.822      439589.437
     1929816.215      439354.181     1929525.821      439060.111
 1929330.7314545  438862.5518815
#Sta/Elev= 30
     116  240.13  307.65  236.18  357.68  233.55  368.62  231.58  385.47  230.57
  409.89  227.07  432.45  228.04  452.96  225.88  539.45  225.89  614.17  223.57
   650.4  224.88  658.55  224.27  675.15  224.63  693.36  222.01  735.91  221.97
  751.94  221.32  768.18  222.08  775.06  221.42   793.8  221.39  823.86  225.08
  855.64  224.74  863.27  225.67  870.85  225.34  891.99  226.41  925.67  226.28
 1115.34  232.15 1184.81  235.94 1255.31  236.23 1272.84  237.36 1291.87  237.21
#Mann= 3 , 0 , 0
     116     .13       0  693.36    .045       0  735.91     .13       0
#XS Ineff= 2 , 0
       0     703     226     733       0     226
Permanent Ineff=
       F       F
Bank Sta=693.36,735.91
XS Rating Curve= 0
Exp/Cntr=.5,.3

Type RM Length L Ch R = 1 ,4966.555,1692.36,1682.59,1642.21
XS GIS Cut Line= 5
      1930700.14      438314.368     1930516.354      438170.779
     1930206.202      438050.164     1929769.692      437986.985
 1929745.6227953  437983.5013037
#Sta/Elev= 30
       0  236.12   41.45  235.07   84.52  232.81   122.8  229.18  138.89  227.13
  144.97  225.92  158.31  225.33  173.73  222.79  213.82  222.29  248.95  221.29
  289.26  219.35  311.39  219.33  332.22  218.67  384.91  218.93  411.88  218.83
  417.62  218.58  425.31  219.01  455.07  218.58  508.44  218.78  522.71  219.56
  551.11  224.52  555.77  224.67  576.74  228.56  588.05  229.32  606.24   231.3
  619.46  231.69  655.19  235.35  668.16  234.49  681.97  234.23 1007.07  236.07
#Mann= 3 , 0 , 0
       0     .13       0  384.91    .045       0  411.88     .13       0
Bank Sta=384.91,411.88
XS Rating Curve= 0
Exp/Cntr=.3,.1

Type RM Length L Ch R = 1 ,3283.960,1518.01,1534.88,1552.71
XS GIS Cut Line= 5
      1930654.19      436453.456     1930349.791       436476.43
     1929970.716      436453.456     1929792.666       436476.43
 1929731.3979383  436484.4916536
#Sta/Elev= 30
       0  240.19  124.02  235.35  170.04  234.82  172.88  234.21  207.39  231.68
  282.72  226.86  326.67  222.82   346.5  220.05  356.27  220.02  365.35  217.92
  404.34  218.16  413.84     219  416.62  218.09  426.52  217.97  553.33  217.88
  555.12   217.9  559.23   216.1  561.27  216.02  564.76  217.93  573.13  217.97
  624.13  217.96  634.87  220.18  646.12  220.56  665.49  222.49  694.81  227.64
  721.81  228.56  766.45  231.37  889.82  234.73  906.43  234.34 1084.71  235.69
#Mann= 3 , 0 , 0
       0     .13       0  553.33    .045       0  573.13     .13       0
Bank Sta=553.33,573.13
XS Rating Curve= 0
Exp/Cntr=.3,.1

Type RM Length L Ch R = 1 ,1749.078,892.91,858.07,789.84
XS GIS Cut Line= 4
      1930947.12      435057.772     1930527.841      434994.593
     1930102.818      434885.466 1930064.8795567   434856.632688
#Sta/Elev= 30
       0  238.03   52.62  237.02   77.26  236.05  115.04  234.46  154.64  231.72
  191.18  230.23  219.34  228.54  273.46  226.91  302.15  224.78  363.25  221.46
  398.73  220.75  436.39  217.43  444.45  216.07  462.82  215.32  479.08  215.32
  489.97  214.09  501.83  214.07  503.83  214.45  516.09  213.66   539.3  213.46
  652.06  213.58  671.25  213.36  683.91  213.42  773.58  213.49  803.83  221.29
  811.02  221.38  820.53  224.39  833.79  225.12  908.52  227.26 1043.17  228.75
#Mann= 3 , 0 , 0
       0     .13       0  652.06    .045       0  683.91     .13       0
Bank Sta=652.06,683.91
XS Rating Curve= 0
Exp/Cntr=.3,.1

Type RM Length L Ch R = 1 ,891.005 ,479.33,475.43,467.58
XS GIS Cut Line= 4
      1930837.99      434069.881     1930631.225      434069.881
     1930223.433      434190.495     1929964.973      434408.751
#Sta/Elev= 30
       0   234.2   92.96  231.79  139.85  229.13   161.8  228.55  194.79  225.19
  205.15  223.84   209.5  222.88  221.43  221.94  246.34  219.13  276.11  214.78
  292.98  213.89  340.42  214.12  398.19  213.81  426.31  213.57  475.23  213.45
  545.87  213.97  556.86  214.66  566.82  215.85   576.4   215.9  608.23  219.58
  615.32  220.78  619.74  222.25  629.01  223.06  637.48  223.54  664.66  223.81
  707.65  226.02  713.56  226.64  729.62  225.86   841.5  228.73  970.31  229.29
#Mann= 3 , 0 , 0
       0     .13       0  398.19    .045       0  426.31     .13       0
Bank Sta=398.19,426.31
XS Rating Curve= 0
Exp/Cntr=.3,.1

Type RM Length L Ch R = 1 ,415.572 ,0,0,0
XS GIS Cut Line= 3
      1930530.35      433586.771     1930092.134      433751.473
      1929948.02      433836.765
#Sta/Elev= 30
       0  228.83   16.25  227.78   35.32  227.23   64.45  224.54   68.93  223.61
   85.72  221.85   92.94  221.86  107.02  219.24   111.6  219.88  120.22  217.59
  136.03  215.24  145.74  214.61  162.84  214.82  213.52  214.04  229.03  214.77
  253.15   213.9  310.05   214.2  335.56  213.79  354.22  214.36  382.25  215.14
  392.81  213.93  423.27  214.62  438.03   213.6  470.42  216.53   480.5  216.53
  515.94  217.97  567.84  221.21  615.23  222.39  623.63  222.83  635.62  224.12
#Mann= 3 , 0 , 0
       0     .13       0  310.05    .045       0  354.22     .13       0
Bank Sta=310.05,354.22
XS Rating Curve= 0
Exp/Cntr=.3,.1

River Reach=Raft Trib       ,one
Reach XY= 30
       1916302.2      444155.232     1916351.779       443915.02
      1916359.08      443687.628      1916352.22       443643.03
      1916341.49      443634.706       1916337.7      443548.667
      1916320.27       443435.34      1916336.52       443313.43
      1916369.03       443199.65      1916499.06       443020.86
      1916564.08       442923.33      1916572.21       442833.93
     1916536.249      442726.047     1916532.347      442714.372
     1916530.264      442708.092     1916498.177       442611.83
      1916496.68       442607.37      1916490.94       442590.12
      1916507.19       442476.34      1916466.56        442403.2
      1916474.68       442321.93      1916434.05       442175.64
      1916393.41       442151.26      1916344.65       442110.63
       1916328.4       442094.37      1916327.62        442093.2
     1916323.122      442089.233     1916320.038      442086.406
     1916309.757      442077.668      1916301.79      442070.729

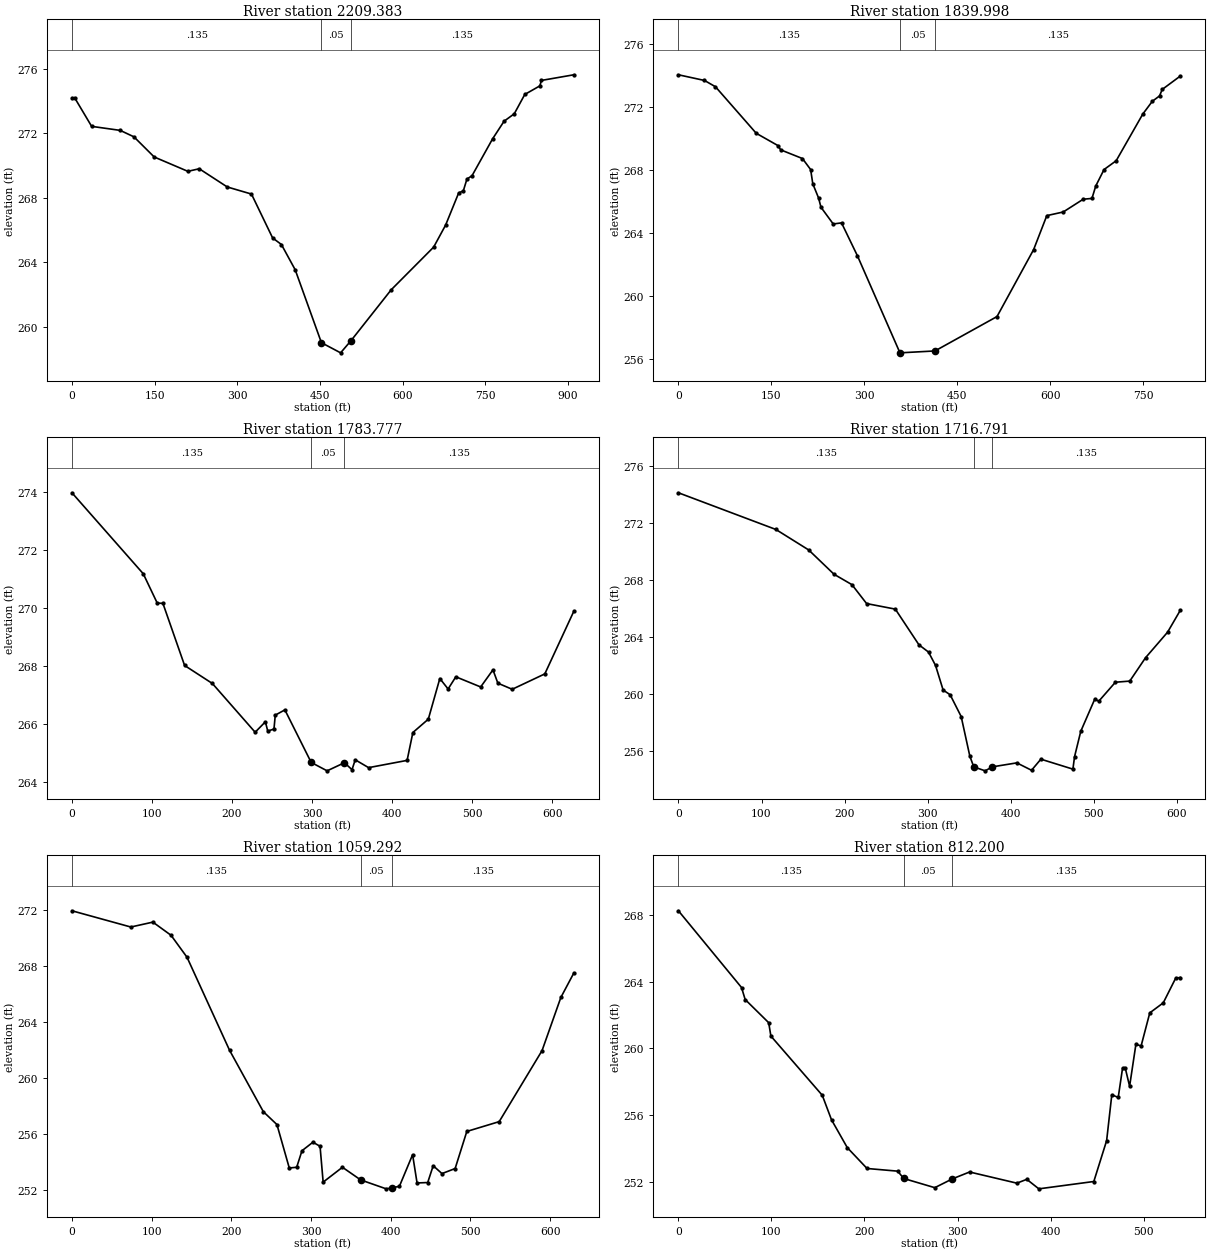
Type RM Length L Ch R = 1 ,2209.383,365.52,369.39,375.09
XS GIS Cut Line= 5
     1916805.513      444134.505      1916434.37      444107.675
     1916192.903      444103.204     1916085.584      444277.596
     1916040.868      444358.085
#Sta/Elev= 30
       0  274.18    4.76  274.21   35.72  272.43    87.6  272.18  112.46  271.78
  149.21  270.53  210.29  269.64  230.93   269.8  281.74  268.67  325.66  268.23
     364  265.51  379.97   265.1  405.01  263.53  452.53  259.01  487.34  258.38
  506.33  259.14  579.07  262.29  656.16  264.94   677.9  266.31  701.52   268.3
  709.96  268.43   716.5  269.16  725.77  269.37  762.94  271.65  783.89  272.75
  802.37  273.21  821.44  274.41  848.69  274.94  851.72  275.28  910.46  275.63
#Mann= 3 , 0 , 0
       0    .135       0  452.53     .05       0  506.33    .135       0
Bank Sta=452.53,506.33
XS Rating Curve= 0
Exp/Cntr=.3,.1

Type RM Length L Ch R = 1 ,1839.998,64.35,56.22,50.91
XS GIS Cut Line= 4
     1916738.439      443718.645     1916528.273      443745.475
     1916098.999       443732.06     1915955.907      443642.628
#Sta/Elev= 30
       0  274.04   42.08  273.68   59.83  273.28  125.63  270.33  160.67  269.55
  165.06  269.28  200.16  268.73  213.43  268.03  216.88  267.13  226.21  266.23
   230.1  265.64  249.88  264.58  263.28  264.65  288.96  262.56  357.59  256.41
  414.11  256.53  514.22  258.71  573.38  262.96   594.6  265.11  621.09  265.34
  653.37  266.15  667.47   266.2  673.64  266.99  686.95  268.03  706.57  268.59
  749.54  271.55  764.92  272.36  776.57   272.7  780.86  273.11   810.1  273.96
#Mann= 3 , 0 , 0
       0    .135       0  357.59     .05       0  414.11    .135       0
Bank Sta=357.59,414.11
XS Rating Curve= 0
Exp/Cntr=.3,.1

Type RM Length L Ch R = 1 ,1783.777,61.42,66.99,56.67
BEGIN DESCRIPTION:
dam
END DESCRIPTION:
XS GIS Cut Line= 6
     1916656.451      443653.802      1916439.14      443674.499
     1916333.589      443686.916     1916232.178      443684.847
     1916066.608      443684.847     1916037.633       443664.15
#Sta/Elev= 30
       0  273.97   89.11  271.18  106.57  270.17  113.67  270.16  140.77  268.02
  175.45   267.4  228.92  265.72  241.72  266.08  244.66  265.76  252.44  265.83
  254.08  266.31  266.09  266.49  298.95  264.68  318.86  264.39   340.5  264.67
  349.96  264.43     354264.7704   370.7   264.5  418.81  264.75  426.01  265.71
  445.31  266.17   459.7  267.57  470.05  267.21  479.68  267.63  510.73  267.28
  526.11  267.87  532.21  267.41  550.16   267.2  590.89  267.73  627.18  269.89
#Mann= 3 , 0 , 0
       0    .135       0  298.95     .05       0   340.5    .135       0
Bank Sta=298.95,340.5
XS Rating Curve= 0
Exp/Cntr=.3,.1

Type RM Length L Ch R = 1 ,1716.791,669.29,657.5,684.09
XS GIS Cut Line= 5
     1916699.239      443615.487       1916356.7      443622.032
     1916212.703      443628.577     1916140.705      443648.213
     1916099.722      443660.011
#Sta/Elev= 30
       0  274.12  117.31  271.54  156.78   270.1   187.3  268.39  208.84  267.66
  226.48  266.33  261.04  265.94  289.47  263.43     301  262.92  309.45  261.98
  318.57  260.25     327  259.92  340.28  258.39  350.72   255.6  355.45  254.85
  369.12  254.57  377.71  254.85  407.27  255.13  424.96  254.61   436.2  255.39
  474.75  254.69  476.75  255.57  484.22  257.35  500.96   259.6  505.96  259.47
  525.88   260.8  543.18  260.88  562.13  262.52  588.71  264.32  604.02  265.86
#Mann= 3 , 0 , 0
       0    .135       0  355.45     .05       0  377.71    .135       0
Bank Sta=355.45,377.71
XS Rating Curve= 0
Exp/Cntr=.3,.1

Type RM Length L Ch R = 1 ,1059.292,265.62,247.09,210.53
XS GIS Cut Line= 6
     1916775.874       443257.13     1916696.785      443161.678
     1916636.786       443090.77     1916590.423      443049.862
     1916380.427      442968.045     1916254.975      442976.227
#Sta/Elev= 30
       0  271.96   73.89   270.8  101.54  271.15  124.33  270.21  144.39  268.64
  197.73     262  240.16  257.61  257.22  256.69  272.69  253.59  281.99  253.64
  288.61  254.82  302.34  255.43  311.31  255.14   315.2  252.58   339.4  253.64
   362.2  252.74  394.28   252.1   401.4  252.17  410.87  252.28  427.44  254.54
  433.03  252.52  446.39  252.55  453.27  253.75   464.3  253.19   480.8  253.55
  495.46   256.2  536.09   256.9  589.84  261.97  613.47  265.77  629.77  267.52
#Mann= 3 , 0 , 0
       0    .135       0   362.2     .05       0   401.4    .135       0
Bank Sta=362.2,401.4
XS Rating Curve= 0
Exp/Cntr=.3,.1

Type RM Length L Ch R = 1 ,812.200 ,488.09,481.46,437.38
XS GIS Cut Line= 4
     1916805.873      442758.049     1916628.604      442793.503
     1916358.609      442779.867     1916271.338      442793.503
#Sta/Elev= 30
       0  268.24   67.83  263.64   71.74  262.92   97.05  261.53   99.38  260.73
  154.61  257.18  164.54  255.71  181.51  254.04  202.74  252.79   235.7  252.63
  242.17  252.19  275.55  251.64  294.54  252.17  312.97  252.58  363.78  251.91
  374.43  252.14  387.39  251.57  446.47  252.01  460.25  254.46  465.81  257.21
  472.71  257.05  477.37  258.81  480.27  258.81  484.94  257.72   491.7  260.23
  497.32  260.14  506.63  262.12  521.11  262.72  534.46   264.2  539.45  264.24
#Mann= 3 , 0 , 0
       0    .135       0  242.17     .05       0  294.54    .135       0
Bank Sta=242.17,294.54
XS Rating Curve= 0
Exp/Cntr=.3,.1

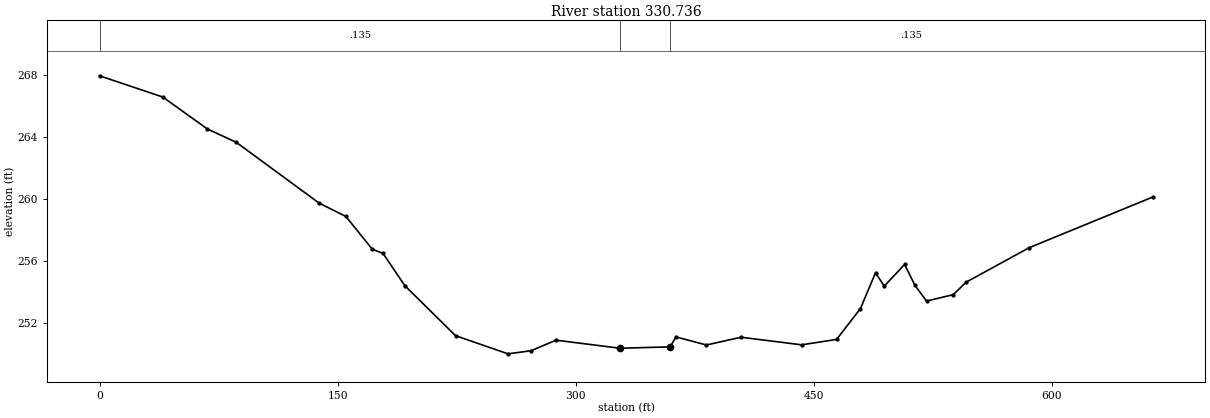
Type RM Length L Ch R = 1 ,330.736 ,0,0,0
XS GIS Cut Line= 5
     1916814.055      442299.877     1916609.514      442294.422
     1916388.609      442354.421     1916317.701      442430.783
     1916325.883      442556.235
#Sta/Elev= 30
       0  267.93   39.87  266.56   67.85  264.51   86.21  263.64  138.31  259.73
  155.18  258.87  171.81  256.76  178.59  256.49  192.33  254.41  224.26  251.19
  257.31  250.02  271.82  250.22  287.56   250.9   327.9  250.38  359.45  250.47
  363.13  251.11  382.32  250.59  404.09  251.09  442.31   250.6  464.31  250.95
  479.29  252.93  488.81  255.24  494.31  254.38  507.13  255.78  513.66  254.43
  520.96  253.42  537.73  253.83  545.98  254.64  585.69  256.86  663.45  260.12
#Mann= 3 , 0 , 0
       0    .135       0   327.9     .05       0  359.45    .135       0
Bank Sta=327.9,359.45
XS Rating Curve= 0
Exp/Cntr=.3,.1

River Reach=Big Middle Swamp,one
Reach XY= 30
      1906971.19       442370.75      1907026.46        442085.2
      1907305.88       441719.81      1907370.36       441302.23
      1907351.93       440654.36      1907491.64        440442.5
      1908038.18       440172.29      1908256.19       439794.63
      1908386.68       439665.67      1908752.07       439426.17
      1908924.02       439401.61      1909056.05       439349.41
      1909108.25       439297.21      1909151.23       439119.12
      1909218.78       439014.73      1909369.24        438944.1
      1909613.34       438505.03      1909691.64       438007.61
      1909875.86       437482.56      1910050.88       437236.92
      1910132.25       437058.83      1910150.67       436699.59
      1910379.42        436116.2       1910496.1       435950.39
      1910563.65       435898.19      1911131.69       435548.16
      1911415.71       434841.95      1911997.56       433862.47
      1912195.61       433675.17      1912752.89       432505.32

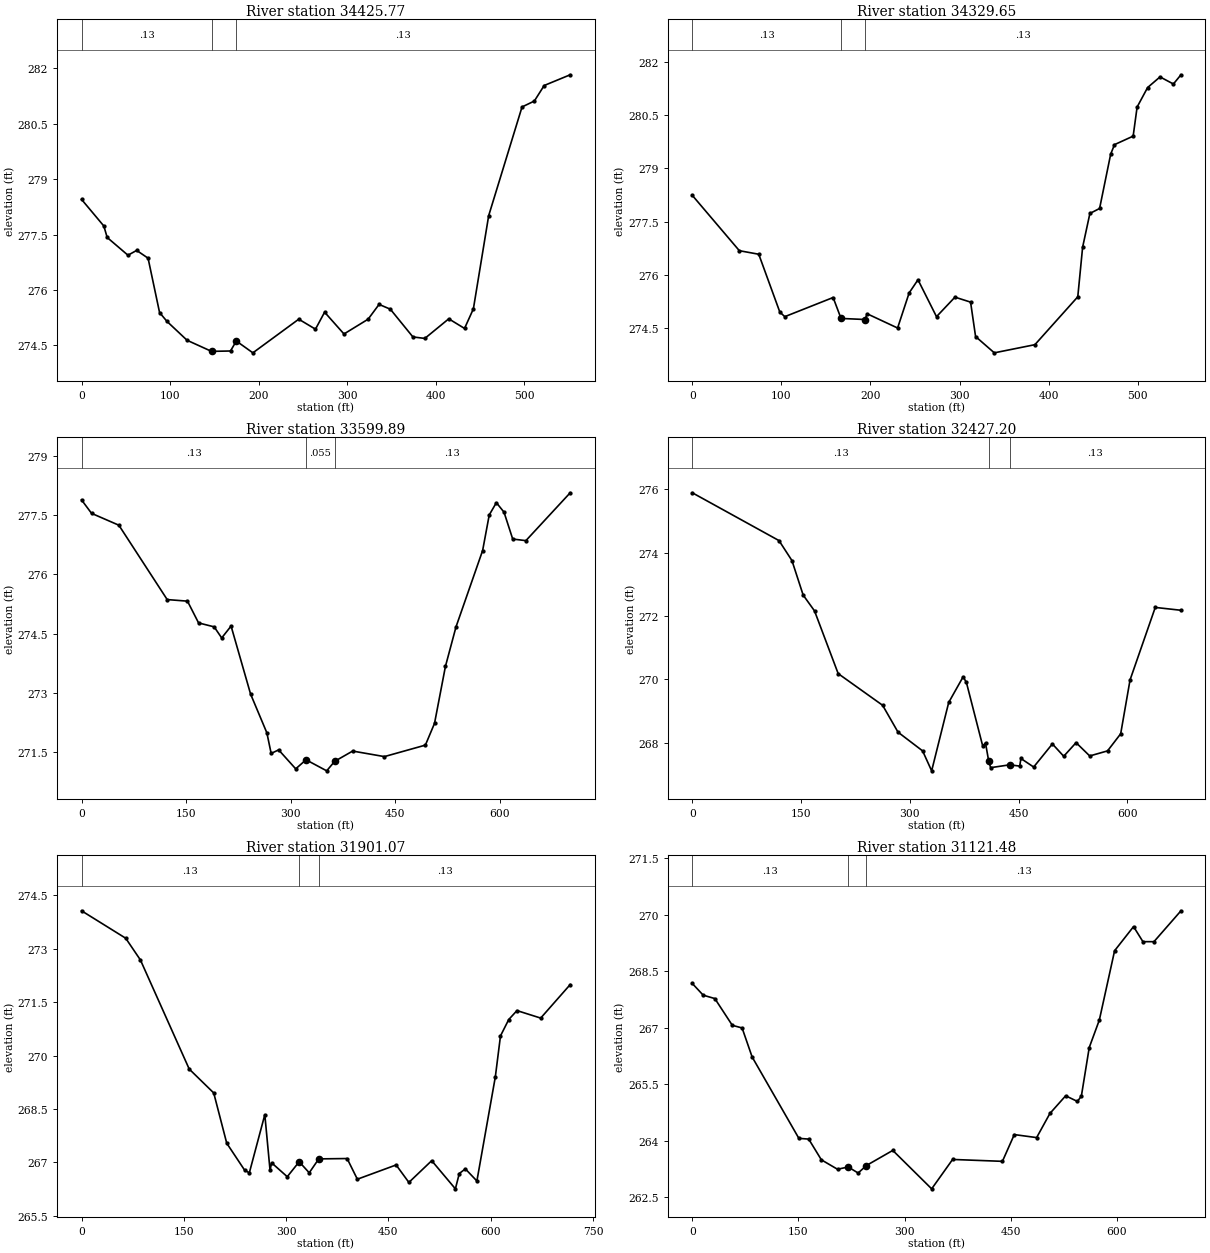
Type RM Length L Ch R = 1 ,34425.77,77.85,96.11,115.82
XS GIS Cut Line= 5
     1907525.106      440808.833      1907447.18      440805.445
     1907169.355      440751.236     1907050.772      440710.579
     1906989.786      440686.862
#Sta/Elev= 30
       0  278.45   25.18  277.73   28.96  277.42   52.44  276.94   62.26  277.07
   75.14  276.86   88.12  275.39    96.5  275.15  119.17  274.64  146.78  274.34
  168.24  274.35  174.79  274.62  193.49   274.3   245.3  275.21  264.18  274.94
   274.5   275.4  296.38  274.81  323.64  275.21  336.01  275.61  348.75  275.48
  374.21  274.73  387.68  274.69  414.71  275.22  432.53  274.96  442.52  275.49
  459.79  278.01  497.46  280.95  511.37  281.11  522.47  281.53  551.86  281.82
#Mann= 3 , 0 , 0
       0     .13       0  146.78    .055       0  174.79     .13       0
Bank Sta=146.78,174.79
XS Rating Curve= 0
Exp/Cntr=.3,.1

Type RM Length L Ch R = 1 ,34329.65,672.66,729.76,782.3
XS GIS Cut Line= 2
     1907521.718        440761.4     1907013.502      440554.726
#Sta/Elev= 30
       0  278.24    52.8  276.68   74.59  276.58   98.24  274.95  103.84  274.82
  158.09  275.36  166.95  274.77  193.69  274.74   196.4   274.9  230.47   274.5
  243.44  275.49  253.36  275.86  274.15  274.82  294.87  275.37  312.41  275.23
  318.02  274.26  339.05   273.8  384.62  274.03  432.76  275.38  438.21  276.78
  446.36  277.73  457.25  277.87  469.68   279.4  473.97  279.67  494.94  279.91
  499.37  280.73  511.16  281.28   525.1  281.58  540.11  281.38  548.63  281.64
#Mann= 3 , 0 , 0
       0     .13       0  166.95    .055       0  193.69     .13       0
Bank Sta=166.95,193.69
XS Rating Curve= 0
Exp/Cntr=.3,.1

Type RM Length L Ch R = 1 ,33599.89,1153.17,1172.69,1183.63
XS GIS Cut Line= 4
     1908075.298      440500.882     1907928.739       440312.45
     1907740.307      440045.504     1907619.919      439982.693
#Sta/Elev= 30
       0  277.88   14.37  277.54   53.57  277.24  122.91  275.36  152.03  275.32
  167.94  274.77  190.33  274.67  201.14  274.39   214.6  274.69  242.61  272.97
  265.97  271.99   272.1  271.47  282.83  271.56  307.37  271.08  322.12  271.31
  351.82  271.03  363.25  271.27  389.05  271.53  434.63  271.39  493.43  271.68
  506.55  272.23   522.2  273.67  537.39  274.67  575.58   276.6  585.08   277.5
  595.29  277.81  606.27  277.57  618.76  276.89  637.67  276.85  701.26  278.06
#Mann= 3 , 0 , 0
       0     .13       0  322.12    .055       0  363.25     .13       0
Bank Sta=322.12,363.25
XS Rating Curve= 0
Exp/Cntr=.3,.1

Type RM Length L Ch R = 1 ,32427.20,552.51,526.12,452.19
XS GIS Cut Line= 3
     1908719.109      439851.837     1908787.154      439647.702
     1908588.253      439234.198
#Sta/Elev= 30
       0  275.89  119.58  274.38  137.41  273.75  152.89  272.66  168.57  272.16
  201.19  270.18  262.48  269.18  283.77  268.33  317.64  267.74  330.12  267.11
  353.66  269.27  373.56  270.08  378.07   269.9  400.48   267.9   404.4  267.99
  408.71  267.43  411.49  267.21  437.69   267.3  451.59  267.26  453.23   267.5
  470.83  267.23  496.65  267.96   512.3  267.57  529.33     268  548.16  267.58
  572.74  267.74  590.86  268.28  603.77  269.98  638.55  272.27  674.03  272.18
#Mann= 3 , 0 , 0
       0     .13       0  408.71    .055       0  437.69     .13       0
Bank Sta=408.71,437.69
XS Rating Curve= 0
Exp/Cntr=.3,.1

Type RM Length L Ch R = 1 ,31901.07,791.28,779.59,727.91
XS GIS Cut Line= 2
      1909374.65      439454.863     1908846.225      438970.758
#Sta/Elev= 30
       0  274.06   64.77  273.29   86.35  272.68  157.92  269.62  193.86  268.95
  212.94  267.54   239.3  266.78  246.09  266.71  268.79  268.34  276.45  266.78
  278.76  266.99   301.7   266.6  319.19  267.02  333.91  266.71  347.92   267.1
   389.5  267.11  404.49  266.53  461.34  266.93  480.06  266.44  513.54  267.05
  548.26  266.26     554  266.69  562.89  266.82   579.8  266.48  606.84   269.4
   614.4  270.55  626.54  271.01  638.58  271.26  673.37  271.05  716.65  271.99
#Mann= 3 , 0 , 0
       0     .13       0  319.19    .055       0  347.92     .13       0
Bank Sta=319.19,347.92
XS Rating Curve= 0
Exp/Cntr=.3,.1

Type RM Length L Ch R = 1 ,31121.48,1245.96,1267.79,1283.46
XS GIS Cut Line= 4
     1909724.081      438784.053     1909624.631      438663.666
     1909263.469      438454.297     1909158.784      438401.954
#Sta/Elev= 30
       0  268.17   15.38  267.86   31.84  267.77   56.53  267.06   70.36  266.99
   84.54  266.22   150.6  264.06  164.51  264.04   182.4  263.49   205.2  263.24
  220.32   263.3  234.36  263.14   246.1263.3394  283.33  263.74  338.29  262.72
  367.87   263.5  438.29  263.45  455.06  264.16  486.63  264.08  505.39  264.72
  527.67  265.19  544.24  265.04  549.85  265.18  560.98  266.47  575.26   267.2
  596.83  269.04  623.61  269.68  636.86  269.28  652.47  269.28  690.65   270.1
#Mann= 3 , 0 , 0
       0     .13       0  220.32    .055       0   246.1     .13       0
Bank Sta=220.32,246.1
XS Rating Curve= 0
Exp/Cntr=.3,.1