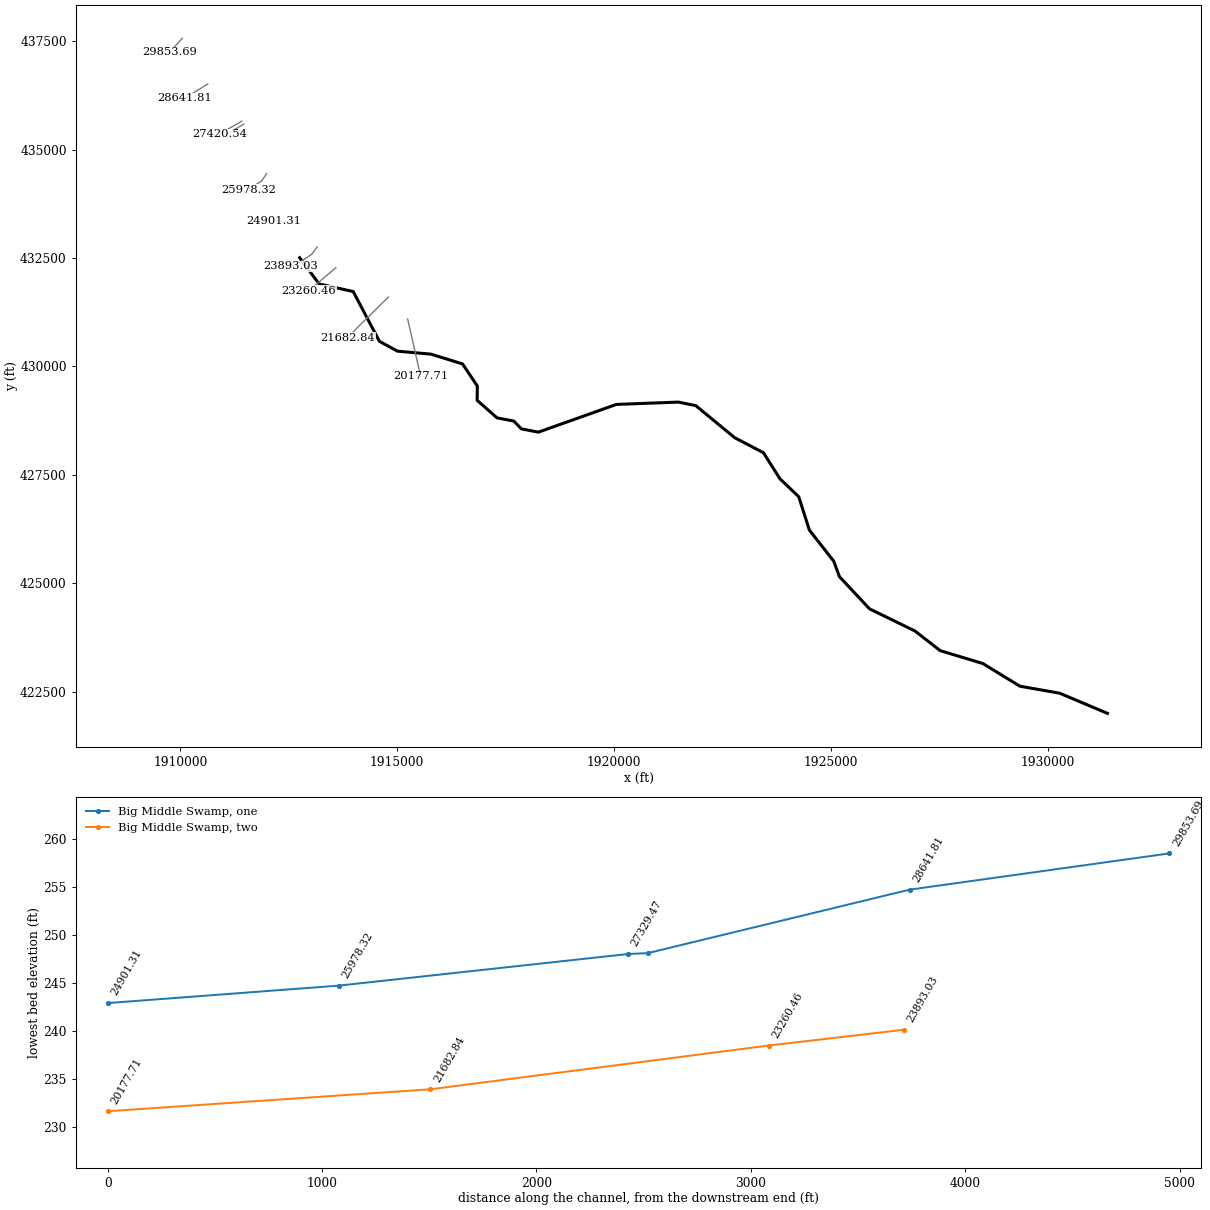
HEC-RAS study upraft.prj: Upper Raft Swamp

--- upraft.g04 (geometry) --- (continued)

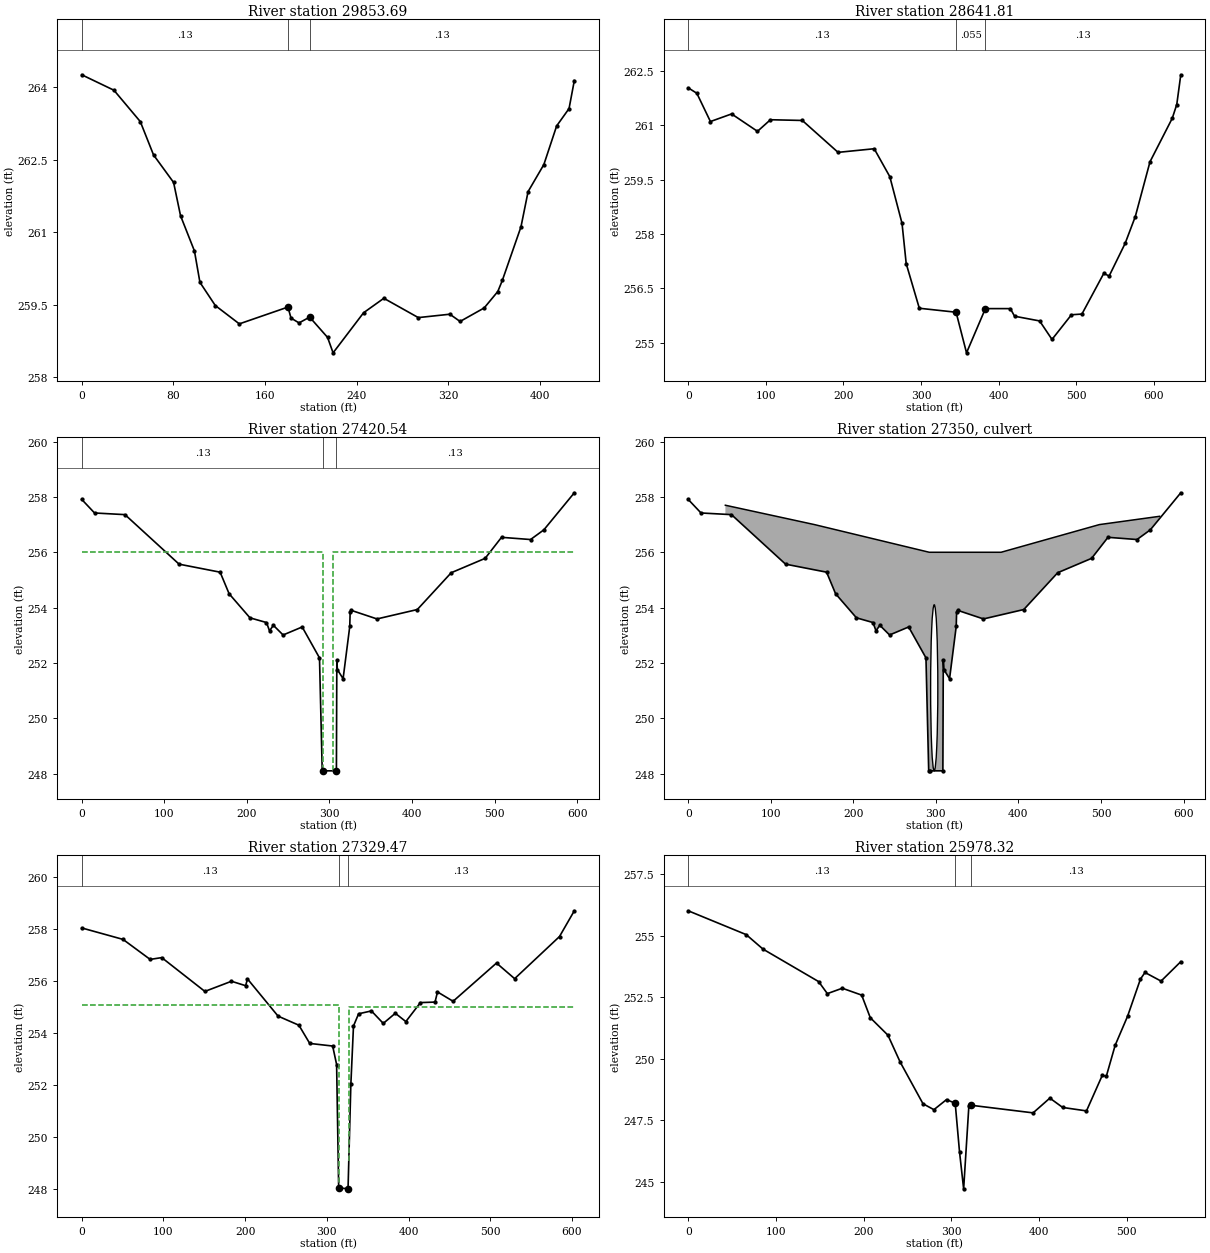
Type RM Length L Ch R = 1 ,29853.69,1242.34,1211.88,1174.17
XS GIS Cut Line= 2
      1910043.37      437564.477     1909755.487      437245.189
#Sta/Elev= 30
       0  264.26   28.11  263.94   51.12  263.29   62.66   262.6   80.17  262.03
   86.24  261.34   98.37  260.61  103.16  259.96  116.57  259.48  137.55   259.1
     180259.4483  182.64  259.22  189.65  259.12  198.92  259.24  214.54  258.82
  219.37   258.5  245.97  259.33  263.67  259.63  293.74  259.23  321.28   259.3
  330.21  259.15  351.24  259.43  363.12  259.77  367.08     260  383.35  261.11
  389.56  261.84  403.32   262.4  414.48   263.2  425.31  263.56  429.91  264.14
#Mann= 3 , 0 , 0
       0     .13       0     180    .055       0  198.92     .13       0
Bank Sta=180,198.92
XS Rating Curve= 0
Exp/Cntr=.3,.1

Type RM Length L Ch R = 1 ,28641.81,1216.47,1221.27,1200.78
XS GIS Cut Line= 2
     1910634.838      436512.396     1910095.712      436177.405
#Sta/Elev= 30
       0  262.03   11.14  261.88   28.63   261.1   55.94  261.31   89.28  260.83
  105.96  261.15  147.04  261.13  193.13  260.25  239.67  260.35  259.79  259.58
  275.54  258.29  280.91  257.18  297.81  255.95  345.19  255.84  358.64  254.72
  382.95  255.94  415.08  255.94  420.56  255.73  452.83   255.6  468.78  255.09
  493.84  255.77  507.35  255.79  535.48  256.91  542.43  256.84  563.05  257.74
  576.14  258.48  595.05  259.99  623.74  261.19  629.55  261.57  634.73  262.39
#Mann= 3 , 0 , 0
       0     .13       0  345.19    .055       0  382.95     .13       0
Bank Sta=345.19,382.95
XS Rating Curve= 0
Exp/Cntr=.5,.3

Type RM Length L Ch R = 1 ,27420.54,87.23,91.07,91.22
XS GIS Cut Line= 2
     1911418.319      435654.107     1910901.093      435356.635
#Sta/Elev= 30
       0  257.91   15.52  257.42   52.38  257.36  117.92  255.57  167.64  255.28
  178.53   254.5  203.79  253.63   223.8  253.46  227.48  253.16  232.13  253.36
  243.91  253.01  267.04   253.3     288252.1825  291.31   248.1  292.47   248.1
  308.49   248.1     309  252.11  309.66  251.76  316.59  251.43  324.66  253.32
  325.13  253.84   326.5   253.9  357.66  253.59   406.5  253.93  447.56  255.26
  488.64  255.78  508.49  256.54  543.65  256.46  559.76  256.81  596.67  258.15
#Mann= 3 , 0 , 0
       0     .13       0  292.47    .055       0  308.49     .13       0
#XS Ineff= 2 , 0
       0  292.47     256     304       0     256
Permanent Ineff=
       F       F
Bank Sta=292.47,308.49
XS Rating Curve= 0
Exp/Cntr=.5,.3

Type RM Length L Ch R = 2 ,27350   ,,,
BEGIN DESCRIPTION:
US401; opening size estimated from similar road class and ortho photos
END DESCRIPTION:
Bridge Culvert--1,0,-1,-1, 0
Deck Dist Width WeirC Skew NumUp NumDn MinLoCord MaxHiCord MaxSubmerge Is_Ogee
39,25,2.6,0, 6, 6, , , .95, 0, 0,0,,
      45     153     292     379     498     571
   257.7     257     256     256     257   257.3
                                                
       0     198     337     424     543  561.84
     258     257     256     256     257     257
                                                
BR Coef=-1 , 0 , 0 ,, 0 ,,,.8,0,,0,
WSPro=,,,, 1 ,,,, 0 ,,,, 0 ,,,,-1 ,-1 ,-1 , 0 , 0 , 0 , 0 , 0
Culvert=3,6,8.71,25,.028,.5,1,34,1,248.1,298,248,320,Culvert #1  , 0 ,39
Culvert Bottom n=.028
BC Design=,, 0 ,, 0 ,,,,,,

Type RM Length L Ch R = 1 ,27329.47,1343.84,1351.15,1355.11
XS GIS Cut Line= 4
      1911466.19      435588.642     1911293.111      435483.405
      1911162.95      435405.862     1910946.937      435282.624
#Sta/Elev= 30
       0  258.04   50.51   257.6   83.74  256.83   97.89   256.9  150.68   255.6
  183.23  255.99  200.54  255.82  202.83  256.08  240.25  254.65  265.75   254.3
  279.01   253.6  307.06   253.5  311.89  252.79  314.41  248.05  325.88  248.01
  329.32  252.03  332.54  254.27   338.8  254.74  354.48  254.85  368.98  254.37
  383.73  254.76   396.6  254.44  414.43  255.17  432.32  255.19  435.34  255.58
  454.44  255.22  507.55  256.69  529.74  256.09  584.64  257.71  602.77   258.7
#Mann= 3 , 0 , 0
       0     .13       0  314.41    .055       0  325.88     .13       0
#XS Ineff= 2 , 0
       0  315.17  255.08  326.78       0  255.02
Permanent Ineff=
       F       F
Bank Sta=314.41,325.88
XS Rating Curve= 0
Exp/Cntr=.5,.3

Type RM Length L Ch R = 1 ,25978.32,1143.27,1077.02,1012.9
XS GIS Cut Line= 3
     1911990.505      434444.874     1911875.352      434277.378
        1911577.      434078.477
#Sta/Elev= 30
       0  256.02   66.17  255.05   85.36  254.46  148.74  253.14  158.72  252.65
  175.75  252.87  197.85  252.59  207.69  251.67   227.8  250.96  241.72  249.87
  267.82  248.17  280.26  247.93  294.64  248.34  304.55  248.19  309.45  246.22
  314.17  244.71  320.13  248.08  322.55  248.11  393.39   247.8  412.51   248.4
  427.13  248.02  454.28  247.88  472.34  249.33  476.91  249.29     487  250.55
  501.15  251.73  515.81  253.24     521  253.51  539.34  253.16  561.84  253.95
#Mann= 3 , 0 , 0
       0     .13       0  304.55    .055       0  322.55     .13       0
Bank Sta=304.55,322.55
XS Rating Curve= 0
Exp/Cntr=.3,.1

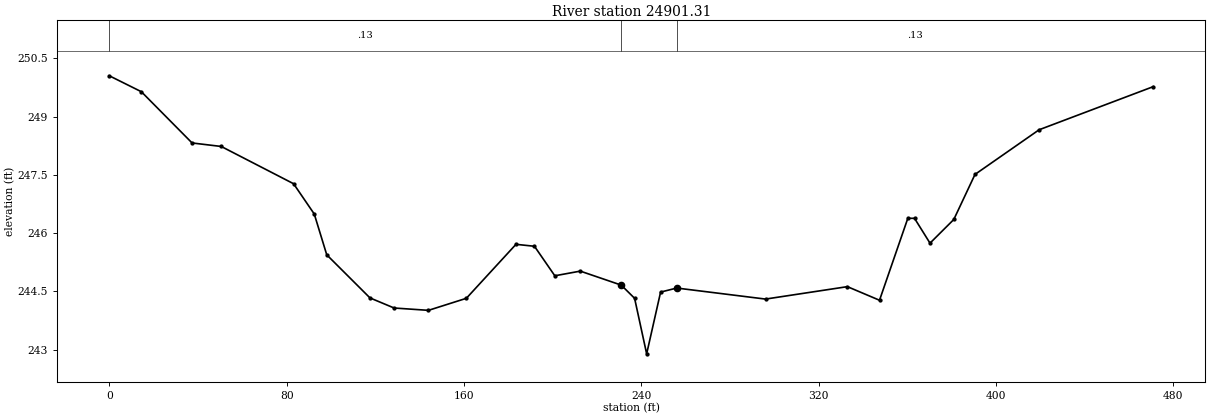
Type RM Length L Ch R = 1 ,24901.31,0,0,0
XS GIS Cut Line= 3
     1912611.321      433363.211     1912508.316      433316.391
     1912152.482      433353.847
#Sta/Elev= 30
       0  250.05   14.45  249.64   37.34  248.32    50.5  248.23   83.14  247.27
   92.47  246.49    98.1  245.44   117.6  244.33   128.5  244.07  143.98  244.01
  161.08  244.32  183.47  245.71   191.8  245.66  200.99   244.9  212.48  245.02
  230.95  244.66  236.98  244.32  242.42  242.89  248.71  244.48     256244.5841
  296.05   244.3  332.98  244.62  347.47  244.27  360.24  246.38  363.26  246.38
  370.25  245.74  380.99  246.35  390.55  247.51  419.48  248.66  470.95  249.77
#Mann= 3 , 0 , 0
       0     .13       0  230.95    .055       0     256     .13       0
Bank Sta=230.95,256
XS Rating Curve= 0
Exp/Cntr=.3,.1

River Reach=Big Middle Swamp,two
Reach XY= 30
      1912752.89       432505.32      1913200.47        431900.7
      1913987.85       431725.17      1914591.05       430578.92
      1915005.86       430350.93      1915783.22       430281.27
      1916508.34       430056.45      1916850.32       429546.65
      1916845.57       429217.34       1917304.7       428812.04
      1917691.01       428739.21      1917865.16       428558.72
      1918256.22       428482.73      1920056.35       429122.35
      1921489.17       429176.18      1921888.14       429093.85
      1922782.66       428356.07       1923449.2       428007.76
      1923826.01        427409.3      1924261.39       426994.49
      1924506.79       426225.05      1925067.26       425509.43
      1925201.83       425148.45      1925895.28        424407.5
       1926941.8        423897.7      1927522.84        423444.9
      1928507.61       423147.26      1929360.96       422624.79
      1930277.65        422463.3      1931381.15       421997.83

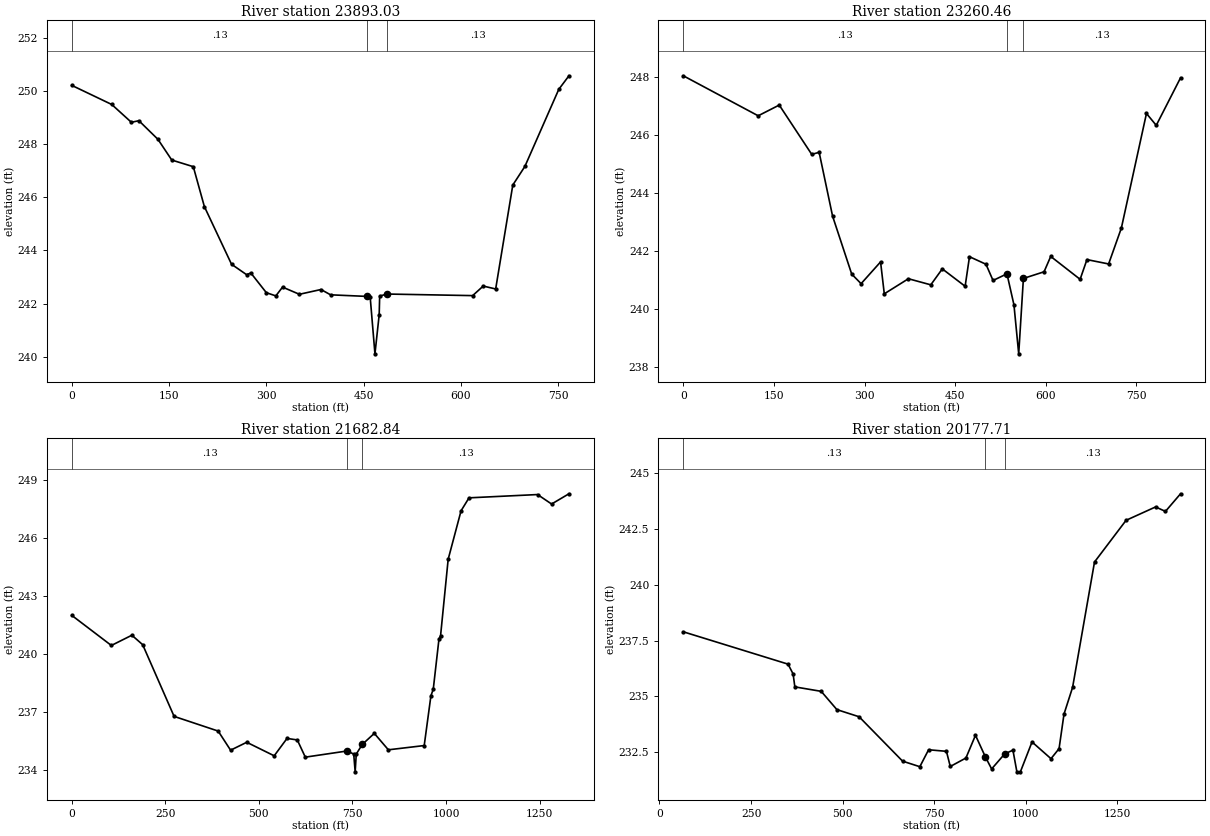
Type RM Length L Ch R = 1 ,23893.03,619.6,632.58,641.24
XS GIS Cut Line= 4
     1913154.436      432754.548     1913032.703      432585.995
     1912658.141      432333.165     1912555.136      432305.073
#Sta/Elev= 30
       0  250.21   61.72  249.49   91.97  248.82  103.57  248.88  132.92  248.18
  154.25   247.4  187.44  247.15   204.5  245.65  246.39  243.48  269.48  243.09
  276.21  243.15  300.07  242.41  314.67  242.29  325.05  242.62  351.02  242.35
  384.27  242.53  399.09  242.33  455.59  242.27  460.12  242.25  467.48  240.11
  474.02  241.58  474.76  242.28  485.66  242.36  618.12   242.3  634.41  242.66
  653.59  242.55  680.01  246.46  698.64  247.16   750.9  250.06  766.59  250.57
#Mann= 3 , 0 , 0
       0     .13       0  455.59    .055       0  485.66     .13       0
Bank Sta=455.59,485.66
XS Rating Curve= 0
Exp/Cntr=.3,.1

Type RM Length L Ch R = 1 ,23260.46,1579.99,1577.62,1522.31
XS GIS Cut Line= 2
     1913587.826      432275.465     1912961.185      431741.973
#Sta/Elev= 30
       0  248.05  123.93  246.67  158.77  247.04  212.54  245.34  224.82  245.41
  247.05  243.21  278.73  241.21  294.24  240.88  326.48  241.63  332.64  240.53
  372.56  241.05  409.61  240.84  428.64  241.39  466.44  240.79  473.65  241.81
  500.94  241.55  512.65  240.99  535.65  241.22  547.24  240.15  555.12  238.46
  562.88  241.06  597.08  241.29   608.1  241.82  656.74  241.03  668.06  241.71
  703.94  241.56  725.04   242.8  766.55  246.75  782.77  246.34  822.98  247.98
#Mann= 3 , 0 , 0
       0     .13       0  535.65    .055       0  562.88     .13       0
Bank Sta=535.65,562.88
XS Rating Curve= 0
Exp/Cntr=.3,.1

Type RM Length L Ch R = 1 ,21682.84,1337.5,1505.12,1622.8
XS GIS Cut Line= 3
     1914800.007      431598.597     1914079.558      430891.014
     1913860.851      430659.441
#Sta/Elev= 30
       0     242  105.87  240.44  160.71  240.97  189.57  240.48  273.49  236.77
  391.22  236.01  424.42  235.02  467.58  235.43  540.91  234.73  575.21  235.63
  602.63  235.55  624.01  234.66  735.89  234.98  753.34  234.82   757.2   233.9
  760.12  234.82  776.28  235.32  808.33  235.89  845.86  235.04  941.65  235.26
   959.6  237.84   965.8  238.17  981.07  240.77  985.38  240.95 1005.66   244.9
 1040.11  247.41 1061.34  248.08 1244.44  248.25 1281.96  247.76 1328.34  248.29
#Mann= 3 , 0 , 0
       0     .13       0  735.89    .055       0  776.28     .13       0
Bank Sta=735.89,776.28
XS Rating Curve= 0
Exp/Cntr=.5,.3

Type RM Length L Ch R = 1 ,20177.71,94.57,96.74,90.4
XS GIS Cut Line= 3
 1915243.4098615  431092.1770003     1915528.766      429831.595
 1915543.1168615  429768.1990003
#Sta/Elev= 30
      65  237.89  350.91  236.44  364.75     236  369.49  235.42  441.47  235.22
   484.3   234.4  544.96  234.08  663.58  232.09  710.69  231.84  734.64   232.6
  783.34  232.53  793.84  231.85  836.52  232.23  862.64  233.25  889.96  232.27
  906.73  231.74  942.63  232.42   964.9  232.58  975.69  231.61  985.23  231.61
    1017  232.95 1068.77   232.2 1090.81  232.65  1104.3   234.2 1127.76   235.4
 1187.59  241.02 1273.76  242.89 1354.26  243.49 1381.25  243.29 1422.48  244.08
#Mann= 3 , 0 , 0
      65     .13       0  889.96    .055       0  942.63     .13       0
Bank Sta=889.96,942.63
XS Rating Curve= 0
Exp/Cntr=.5,.3