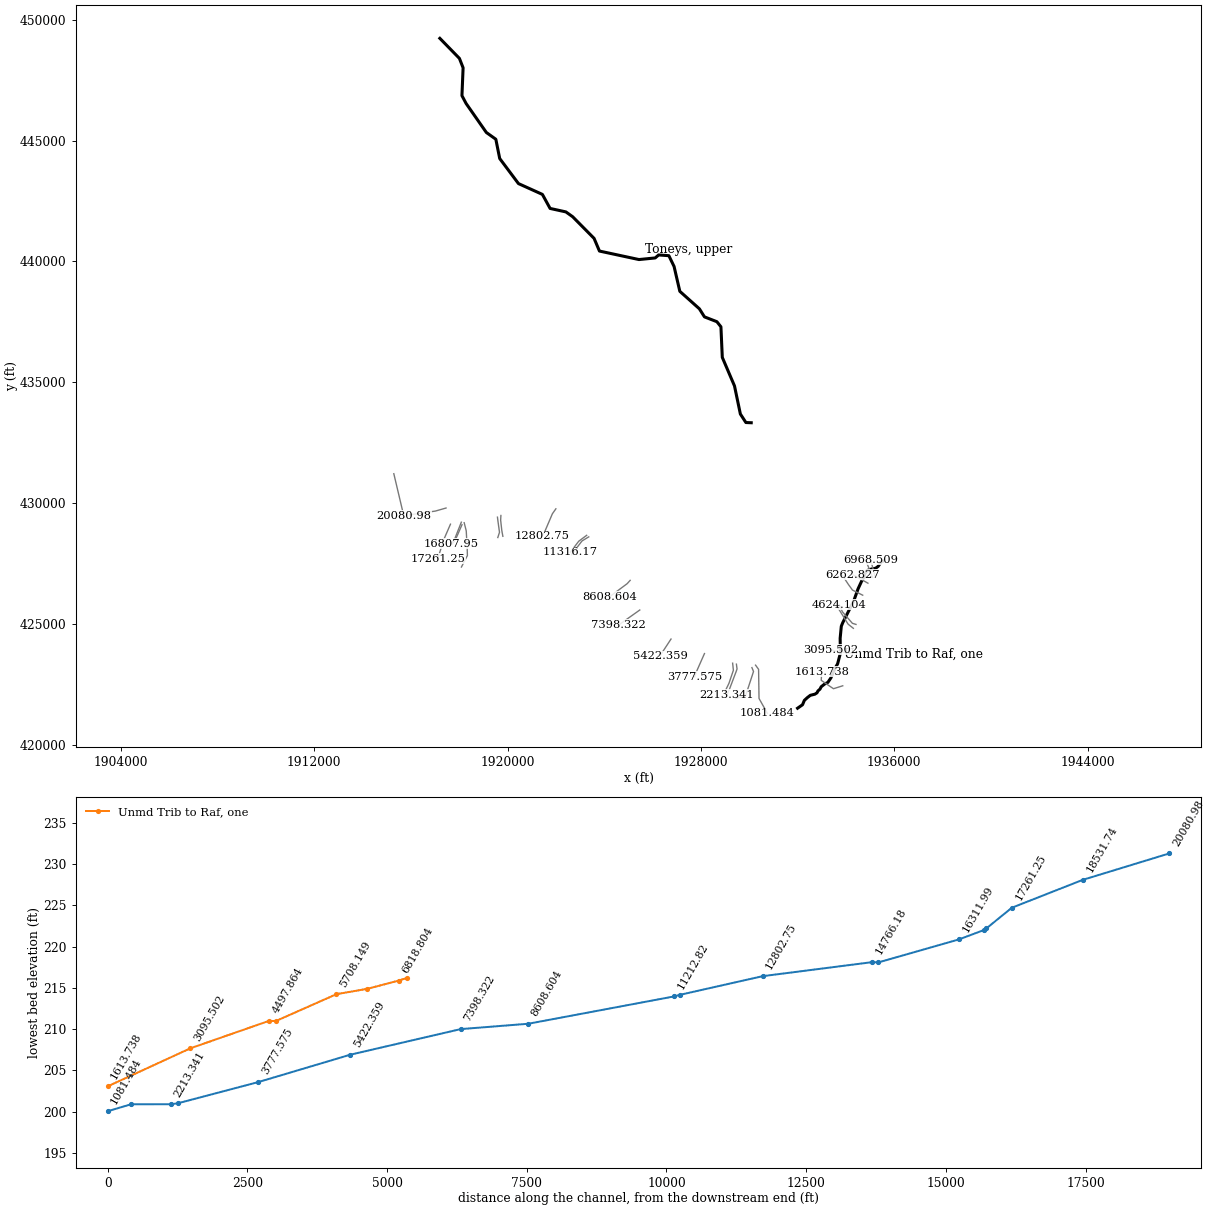
HEC-RAS study upraft.prj: Upper Raft Swamp

--- upraft.g04 (geometry) --- (continued)

Type RM Length L Ch R = 3 ,20108   ,,,
BEGIN DESCRIPTION:
McNeil Farm Rd.; structure size estimated using similar road class and ortho photos
END DESCRIPTION:
Bridge Culvert--1,0,-1,-1, 0
Deck Dist Width WeirC Skew NumUp NumDn MinLoCord MaxHiCord MaxSubmerge Is_Ogee
43,20,2.6,0, 60, 60, , , .95, 0, 0,0,,
       0   97.12  110.68   130.2  148.13   224.3  267.28  336.27  376.65  397.92
  419.85  438.29  463.78   476.5  491.23   506.1  523.21  530.66   535.8   542.9
  548.73  559.46  564.63  573.15  580.13  652.24  660.07  661.32  761.42  763.67
   767.2  810.97  839.44  895.38  899.66  903.77  903.77  934.77  936.68 1000.78
 1010.78 1023.37  1044.3 1064.28 1073.66 1139.31 1259.64 1269.39 1289.76 1303.05
 1385.52  1421.1 1472.23 1555.67 1573.76 1600.01 1635.84  1656.9 1685.79 1698.25
  239.97   239.1  238.84  238.71  238.44  237.89  237.35  236.86  236.68  236.47
  236.08   236.1  235.85  235.83  235.51  235.69  235.54  235.55  235.67  235.65
  235.46  235.39  235.18   235.1  235.24  235.25  235.15  235.05  235.07  235.05
  234.75  234.91  234.66     235  235.08   235.4  235.46  235.51  235.53  235.52
   235.6  235.87  235.79  235.96  236.18  236.47  237.98  238.24   238.4  238.66
  239.63  239.93  240.17  241.18  241.21  241.51  241.46  241.76  241.84  242.05
                                                                                
                                                                                
                                                                                
                                                     234     234
                                                                                
                                                                                
       0   97.12  110.68   130.2  148.13   224.3  267.28  376.65  397.92  419.85
  438.29   476.5  491.23   506.1  523.21   535.8   542.9  548.73  559.46  564.63
  573.15  580.13  652.24  661.32  761.42  763.67   767.2  810.97  839.44  918.97
  930.78  958.91  963.77  988.77  990.32  994.77  996.68 1010.78 1023.37  1044.3
 1064.28 1073.66 1108.22 1150.42 1166.93 1167.28 1167.89 1176.77 1259.64 1269.39
 1289.76 1405.05 1472.23 1555.67 1573.76  1593.2 1635.84  1656.9 1685.79 1698.25
  239.97   239.1  238.84  238.71  238.44  237.89  237.35  236.68  236.47  236.08
   236.1  235.83  235.51  235.69  235.54  235.67  235.65  235.46  235.39  235.18
   235.1  235.24  235.25  235.05  235.07  235.05  234.75  234.91  234.66  235.14
  235.37   235.4  235.46  235.55   235.4  235.51  235.53   235.6  235.87  235.79
  235.96  236.18  236.27  236.57  236.78  236.87  236.79  236.99  237.98  238.24
   238.4  239.82  240.17  241.18  241.21  241.47  241.46  241.76  241.84  242.05
                                                                                
                                                                                
                                                                                
                     234     234     234     234
                                                                                
                                                                                
Pier Skew, UpSta & Num, DnSta & Num=  ,922, 2 ,978, 2 , 0 , 0 , 0 ,,
       2       2
       0     234
       2       2
       0     234
BR Coef=-1 , 1 , 0 ,, 0 ,,.54,.8,0,1.2,1,
WSPro=,,,, 1 ,,,, 0 ,,,, 0 ,,,,-1 ,-1 ,-1 , 0 , 0 , 0 , 0 , 0
BC Design=,, 0 ,, 0 ,,,,,,

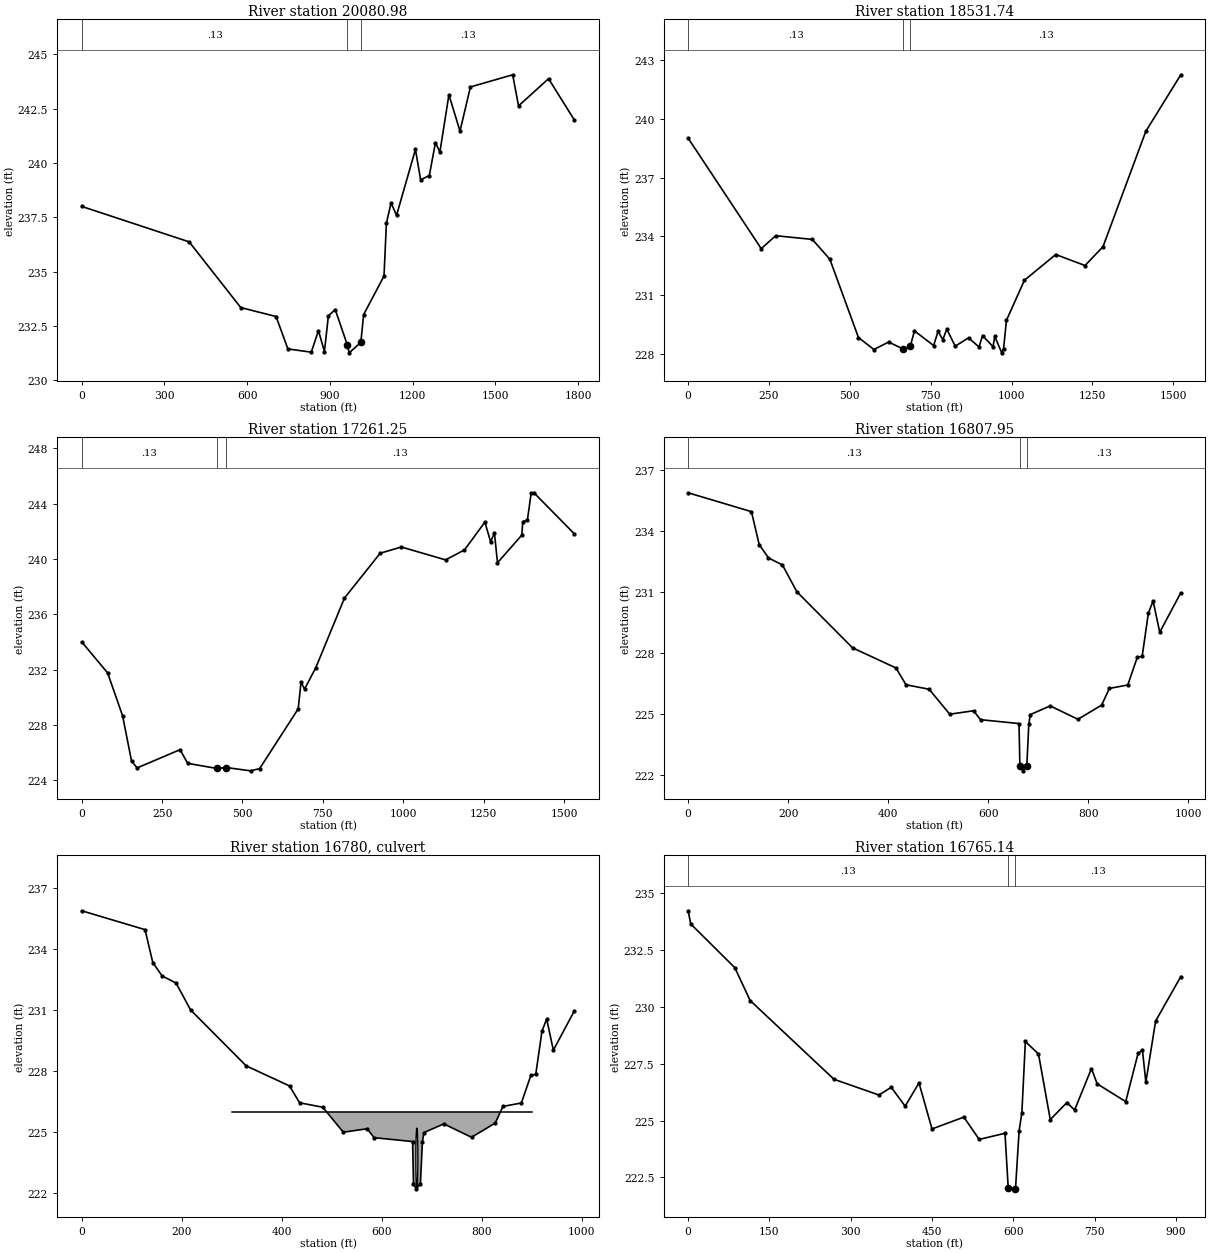
Type RM Length L Ch R = 1 ,20080.98,1744.1,1549.24,1329.82
XS GIS Cut Line= 2
     1915294.929      431218.149     1915706.614      429479.193
#Sta/Elev= 30
       0     238  389.79  236.37  576.92  233.35  704.93  232.94  747.76  231.45
  832.68   231.3  858.76  232.29   880.3  231.33  894.71  232.97  919.54  233.26
  964.02  231.61  970.13  231.27 1012.38  231.75 1022.63  233.03 1096.47   234.8
 1105.19  237.23 1121.97  238.16 1141.97  237.59  1210.5  240.62 1229.34  239.22
 1260.82  239.42 1283.02  240.93 1299.24   240.5 1331.92  243.13 1372.09  241.46
  1409.9  243.49 1563.24  244.05  1584.4  242.62  1693.3  243.87 1787.02  241.97
#Mann= 3 , 0 , 0
       0     .13       0  964.02    .055       0 1012.38     .13       0
Bank Sta=964.02,1012.38
XS Rating Curve= 0
Exp/Cntr=.5,.3

Type RM Length L Ch R = 1 ,18531.74,1039.21,1270.49,1339.35
XS GIS Cut Line= 3
     1917455.544      429798.697     1917014.629      429672.722
     1915961.016      429518.116
#Sta/Elev= 30
       0  239.01  226.03  233.38  270.81  234.04  384.03  233.85  438.24  232.84
  526.69  228.85  574.54  228.24  619.98  228.62  665.64  228.26  686.85   228.4
  699.84  229.19  759.17  228.44  772.84  229.17  787.59  228.74  799.82  229.28
  825.84  228.41     867  228.83  899.71  228.37   910.4  228.95  943.03  228.38
  947.99  228.91  969.85  228.07  975.43  228.28   984.4  229.73 1039.96  231.77
 1136.68  233.08 1227.37  232.52 1282.92  233.48 1415.35  239.36 1523.45  242.24
#Mann= 3 , 0 , 0
       0     .13       0  665.64    .055       0  686.85     .13       0
Bank Sta=665.64,686.85
XS Rating Curve= 0
Exp/Cntr=.3,.1

Type RM Length L Ch R = 1 ,17261.25,410.64,453.31,387.91
XS GIS Cut Line= 3
     1917638.422      429129.561     1917360.798       428488.89
     1917109.869      427693.392
#Sta/Elev= 30
       0  234.01   80.49  231.77  127.17  228.66  154.81  225.41  172.15   224.9
  305.76  226.22  329.72  225.23  421.11  224.86  449.57  224.93  524.95  224.69
  553.34  224.85  673.29  229.17   682.1   231.1  693.18   230.6  728.28  232.16
  817.25  237.18  928.25  240.42  994.09  240.87 1131.68  239.94 1190.55  240.66
  1254.1  242.67 1271.84  241.24 1283.67   241.9 1293.23  239.73 1368.83  241.73
 1371.96   242.7 1386.21  242.82 1397.75  244.74 1406.62  244.79 1532.37  241.82
#Mann= 3 , 0 , 0
       0     .13       0  421.11    .055       0  449.57     .13       0
Bank Sta=421.11,449.57
XS Rating Curve= 0
Exp/Cntr=.5,.3

Type RM Length L Ch R = 1 ,16807.95,50,42.81,46.49
XS GIS Cut Line= 4
      1918087.94      429212.823     1917832.015      428563.515
     1917715.898      428381.046     1917670.873      428326.542
#Sta/Elev= 30
       0   235.9  126.54  234.97  142.05  233.35  160.64  232.69  188.62  232.34
  217.46  231.02  328.73  228.26  415.42  227.27  435.56  226.44  481.85  226.22
  522.97  224.99  570.54  225.16  584.56  224.72  661.47  224.53  663.26  222.43
  669.24   222.2  677.11  222.46  681.06   224.5  684.02  224.97  723.85   225.4
  779.23  224.74  826.71  225.44   842.1  226.26  878.93  226.43  897.92  227.79
  907.69  227.84  920.14  229.97  929.54  230.57  942.84  229.03  984.91  230.97
#Mann= 3 , 0 , 0
       0     .13       0  663.26    .055       0  677.11     .13       0
Bank Sta=663.26,677.11
XS Rating Curve= 0
Exp/Cntr=.5,.3

Type RM Length L Ch R = 2 ,16780   ,,,
BEGIN DESCRIPTION:
unnamed road; structure size estimated from similar road class
END DESCRIPTION:
Bridge Culvert--1,0,-1,-1, 0
Deck Dist Width WeirC Skew NumUp NumDn MinLoCord MaxHiCord MaxSubmerge Is_Ogee
11,20,2.6,0, 2, 2, , , .95, 0, 0,0,,
     300     900
     226     226
                
     300     900
     226     226
                
Culvert=3,3,3.98,20,.03,.5,1,34,1,222.2,670,222,598,Culvert #1  , 0 ,11
Culvert Bottom n=.03
BC Design=,, 0 ,, 0 ,,,,,,

Type RM Length L Ch R = 1 ,16765.14,403.6,453.15,508.36
XS GIS Cut Line= 5
      1918116.38      429108.554     1917936.284       428696.22
     1917853.343      428513.751     1917763.293      428373.936
      1917701.68      428305.214
#Sta/Elev= 30
       0  234.21    4.84  233.63   86.16  231.71  114.38  230.27  269.15  226.81
  352.09  226.12  374.74  226.46  400.39  225.63  425.94  226.65  449.95  224.63
  508.68  225.15  537.11  224.17  584.62  224.44  590.63  222.02  603.99     222
   610.7  224.55  615.77  225.34  622.24  228.47  646.45  227.92  668.18  225.04
  698.92  225.79  713.08  225.46  744.15  227.28  754.77  226.61  807.41  225.83
   830.2  227.95  838.28  228.09  844.53  226.68  862.58  229.37  908.99  231.32
#Mann= 3 , 0 , 0
       0     .13       0  590.63    .055       0  603.99     .13       0
Bank Sta=590.63,603.99
XS Rating Curve= 0
Exp/Cntr=.5,.3

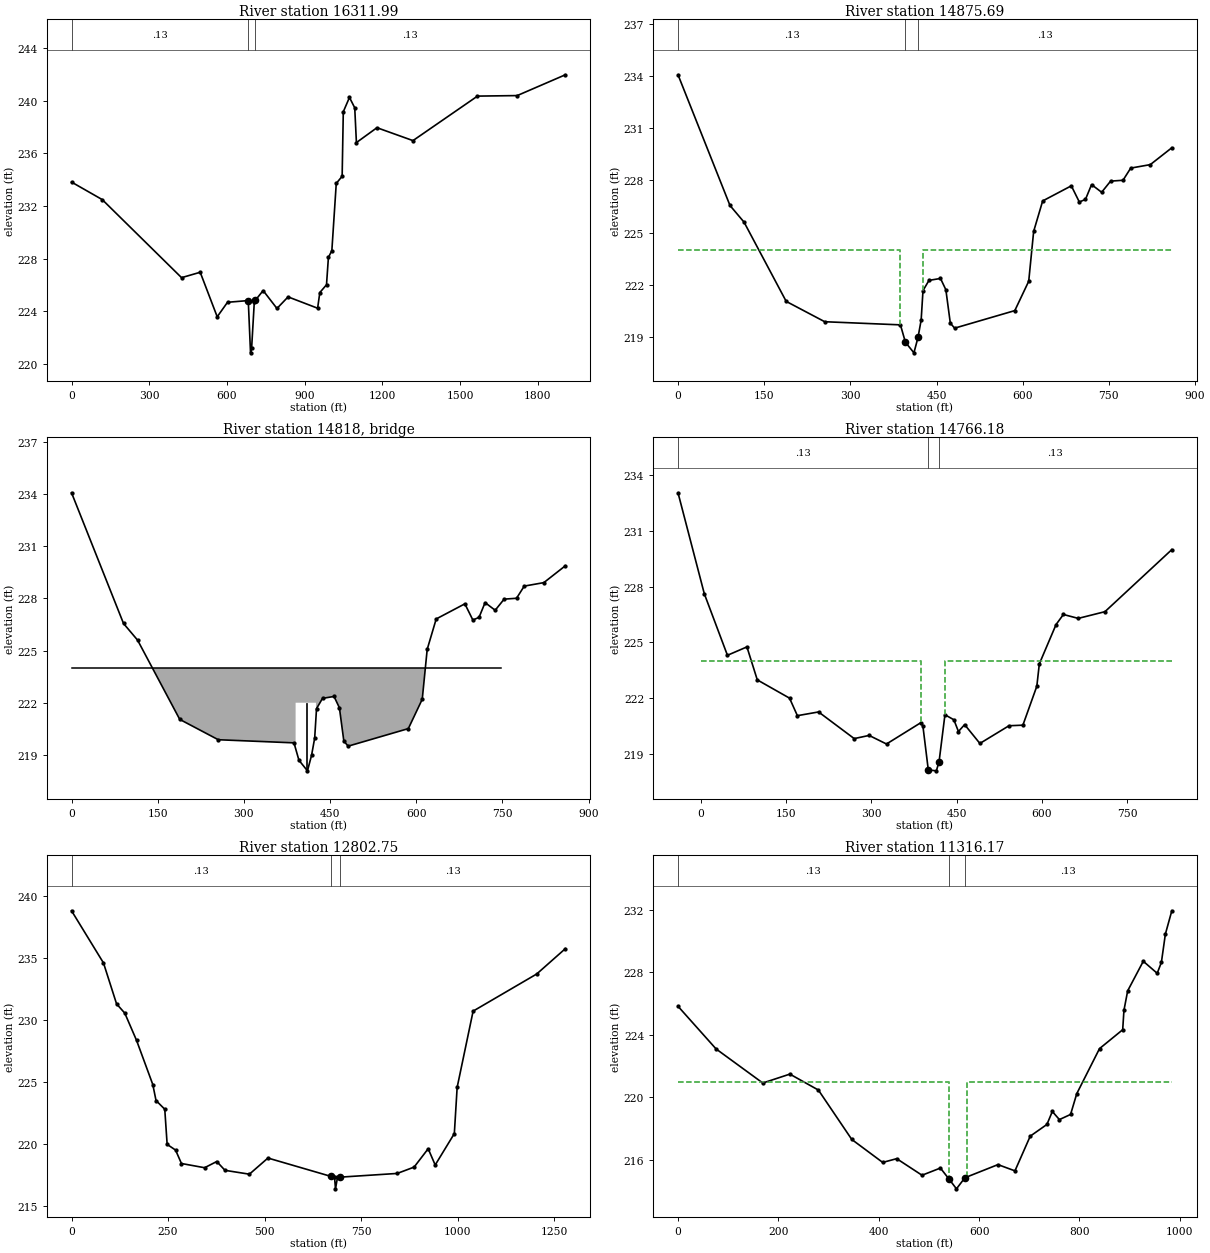
Type RM Length L Ch R = 1 ,16311.99,1418.41,1436.3,1436.78
XS GIS Cut Line= 5
     1918205.671      429191.724     1918291.563      428853.881
     1918331.889      428094.821     1918339.359      427832.772
     1918092.246      427357.793
#Sta/Elev= 30
       0  233.82  118.43  232.49   424.7  226.56  496.67  226.97  562.32  223.59
   602.1  224.69  682.23  224.82  690.96  220.85  695.24  221.23  705.51  224.71
  709.99  224.85  739.64  225.58  792.99  224.22  835.91   225.1  949.91  224.24
  958.49  225.43  984.26  226.02  991.59   228.1 1004.88  228.61 1021.91  233.72
 1044.64  234.26 1049.07  239.16 1072.87  240.25 1093.25  239.46 1099.69  236.82
 1179.03  237.95 1318.03  236.97 1567.09  240.35 1720.48  240.39 1906.29  241.97
#Mann= 3 , 0 , 0
       0     .13       0  682.23    .055       0  709.99     .13       0
Bank Sta=682.23,709.99
XS Rating Curve= 0
Exp/Cntr=.5,.3

Type RM Length L Ch R = 1 ,14875.69,112.69,109.51,109.89
XS GIS Cut Line= 4
     1919582.583      429420.313     1919604.571       429248.07
     1919666.872      428793.642     1919597.242      428577.422
#Sta/Elev= 30
       0  234.08   90.44  226.56  114.95   225.6  188.31  221.04  255.38  219.87
  387.16  219.69  395.78  218.69  410.61  218.08   417.8  218.98   423.2  219.97
  426.39  221.66  436.83  222.25  456.86  222.36   466.2  221.71  473.94  219.79
  481.45   219.5  586.19  220.51  610.41   222.2  619.01  225.07  634.69  226.82
  684.57  227.69  698.49  226.76  709.21  226.91  719.78  227.76  737.34  227.32
  752.92  227.96  774.51  228.01  787.92  228.71  822.04  228.91  859.47  229.88
#Mann= 3 , 0 , 0
       0     .13       0  395.78    .055       0   417.8     .13       0
#XS Ineff= 2 , 0
       0  387.16     224  426.39       0     224
Permanent Ineff=
       F       F
Bank Sta=395.78,417.8
XS Rating Curve= 0
Exp/Cntr=.5,.3

Type RM Length L Ch R = 3 ,14818   ,,,
BEGIN DESCRIPTION:
SR1134; no.25 from NCDOT database
END DESCRIPTION:
Bridge Culvert--1,0,-1,-1, 0
Deck Dist Width WeirC Skew NumUp NumDn MinLoCord MaxHiCord MaxSubmerge Is_Ogee
53.48,29.3,2.6,0, 11, 11, , , .95, 0, 1.5,1.5,,
       0    4.43    5.26  385.98     390  406.67  408.67  408.67  425.42  425.48
  746.84
     224     224     224     224     224     224     224     224     224     224
     224
                                     222     222     222     222     222
        
       0    4.43    5.26  385.98     390  406.67  408.67  408.67  425.42  425.48
  746.84
     224     224     224     224     224     224     224     224     224     224
     224
                                     222     222     222     222     222
        
Pier Skew, UpSta & Num, DnSta & Num=  ,408.67, 2 ,408.67, 2 , 0 , 0 , 0 ,,
       2       2
     210     226
       2       2
     210     226
BR Coef=-1 , 1 , 0 ,, 0 ,,,.8,0,1.2,1,
WSPro=,,,, 1 ,,,, 0 ,,,, 0 ,,,,-1 ,-1 ,-1 , 0 , 0 , 0 , 0 , 0
BC Design=,, 0 ,, 0 ,,,,,,

Type RM Length L Ch R = 1 ,14766.18,2011.76,1963.44,1891.01
XS GIS Cut Line= 6
     1919725.508      429489.943     1919725.508      429489.943
     1919714.514      429295.712     1919762.155      428874.266
  1919799.080029  428668.1014645     1919806.132      428628.728
#Sta/Elev= 30
     -40  233.03    6.26  227.61   46.89  224.31   81.15  224.76   99.39  222.99
  156.08  222.01  169.86  221.07  207.11  221.27  269.75  219.84  295.99  220.01
  326.53  219.55  387.21   220.7  390.64  220.49     400  218.16  414.17  218.11
   418.9  218.59  429.27  221.12  444.96  220.85     453  220.22  463.88  220.59
  490.71  219.58  541.89  220.53   566.3  220.56   590.8  222.65   595.2  223.85
  624.63  225.96  637.51   226.5   663.6  226.29  710.56  226.65  828.12  229.98
#Mann= 3 , 0 , 0
     -40     .13       0     400    .055       0   418.9     .13       0
#XS Ineff= 2 , 0
       0  387.39     224  429.58       0     224
Permanent Ineff=
       F       F
Bank Sta=400,418.9
XS Rating Curve= 0
Exp/Cntr=.5,.3

Type RM Length L Ch R = 1 ,12802.75,1517.54,1486.58,1435.04
XS GIS Cut Line= 4
     1921999.715      429765.353     1921856.279      429563.238
     1921549.846      428846.056      1921419.45      428630.902
#Sta/Elev= 30
       0   238.8   82.74   234.6  116.68   231.3  137.92  230.56  168.47  228.36
  210.49  224.81  218.88  223.52  241.53  222.82  247.66  219.99  269.54  219.53
   284.7  218.45  344.72  218.11  376.24  218.61  397.58   217.9  460.75  217.59
  508.84  218.89  671.21  217.42  681.29  217.37  683.84  216.41  689.05  217.34
  695.24  217.35  843.73  217.65  887.45  218.16  923.97  219.64  942.13  218.33
  991.72  220.86     999  224.58 1040.38  230.72 1205.13  233.71 1279.33  235.75
#Mann= 3 , 0 , 0
       0     .13       0  671.21    .055       0  695.24     .13       0
Bank Sta=671.21,695.24
XS Rating Curve= 0
Exp/Cntr=.5,.3

Type RM Length L Ch R = 1 ,11316.17,101.88,103.35,102.89
XS GIS Cut Line= 3
     1923272.829       428669.03      1922945.69      428425.344
     1922595.184      427968.017
#Sta/Elev= 30
       0  225.82   75.89  223.09  168.97  220.91  222.89  221.48  279.79  220.46
  346.31   217.3  407.92  215.83  435.84  216.07   486.3  215.01  522.92  215.47
  539.52  214.79  554.93  214.14  571.77  214.85  637.64  215.69   671.5  215.29
  701.95  217.51  735.21  218.26  745.99  219.09  760.08  218.57  782.34   218.9
   794.7  220.23     840  223.11  886.23  224.32  888.71  225.56  896.17  226.81
  927.25   228.7  955.01  227.93  963.35  228.63   971.3  230.44  984.12  231.93
#Mann= 3 , 0 , 0
       0     .13       0  539.52    .055       0  571.77     .13       0
#XS Ineff= 2 , 0
       0     540     221   575.5       0     221
Permanent Ineff=
       F       F
Bank Sta=539.52,571.77
XS Rating Curve= 0
Exp/Cntr=.5,.3

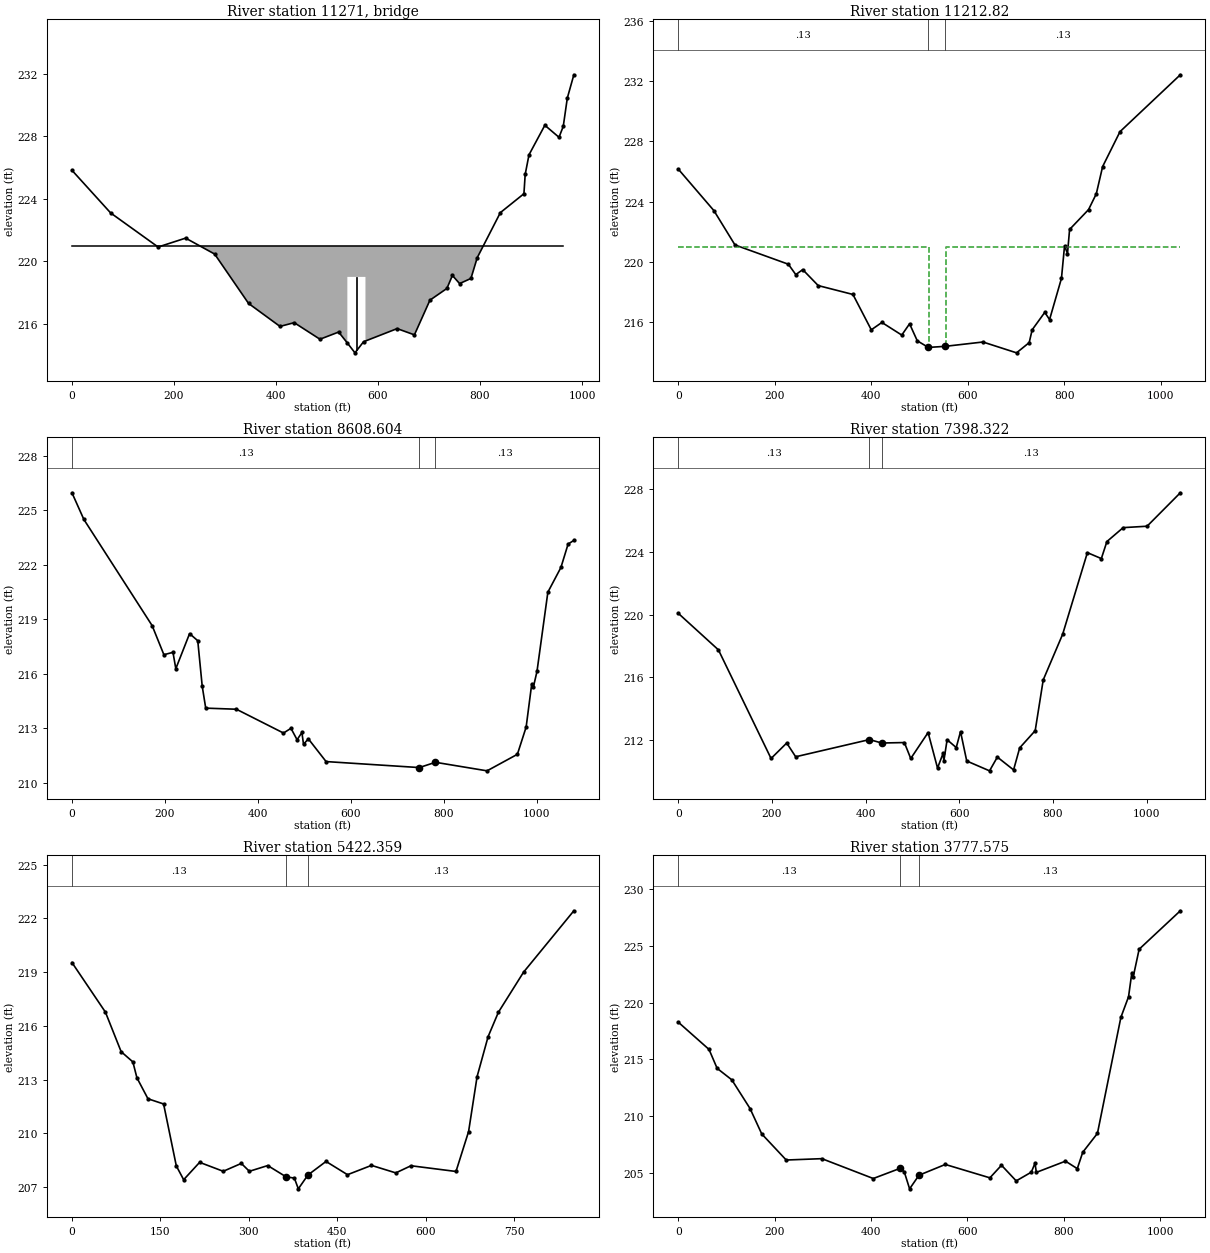
Type RM Length L Ch R = 3 ,11271   ,,,
BEGIN DESCRIPTION:
SR1116; no.24 from NCDOT database
END DESCRIPTION:
Bridge Culvert--1,0,-1,-1, 0
Deck Dist Width WeirC Skew NumUp NumDn MinLoCord MaxHiCord MaxSubmerge Is_Ogee
45.84,29.3,2.6,0, 6, 6, , , .95, 0, 1.5,1.5,,
       0  507.14     540   575.5   575.5  962.09
     221     221     221     221     221     221
                     219     219
       0  507.14     520   555.5   555.5  962.09
     221     221     221     221     221     221
                     219     219
Pier Skew, UpSta & Num, DnSta & Num=  ,558.83, 2 ,538.83, 2 , 0 , 0 , 0 ,,
       2       2
     210     219
       2       2
     210     219
BR Coef=-1 , 1 , 0 ,, 0 ,,,.8,0,1.2,1,
WSPro=,,,, 1 ,,,, 0 ,,,, 0 ,,,,-1 ,-1 ,-1 , 0 , 0 , 0 , 0 , 0
BC Design=,, 0 ,, 0 ,,,,,,

Type RM Length L Ch R = 1 ,11212.82,2581.44,2604.22,2494.01
XS GIS Cut Line= 3
     1923359.622      428605.605     1923079.217      428435.359
     1922648.595      427867.873
#Sta/Elev= 30
       0  226.15   73.63   223.4  117.25  221.12  227.88  219.84   243.3  219.15
  257.71  219.48   289.8  218.42  361.77  217.83  399.81  215.48  421.79  215.97
  462.98  215.13  479.17  215.88  495.13  214.75  518.06  214.31  552.36  214.38
  631.28  214.67  700.93  213.95  727.15  214.63  733.28  215.48  759.44  216.64
  769.36  216.16  794.02   218.9  800.42  221.06  806.53  220.55  810.88  222.15
  850.19  223.47  866.25  224.52  879.37  226.33  915.39  228.65 1040.41  232.43
#Mann= 3 , 0 , 0
       0     .13       0  518.06    .055       0  552.36     .13       0
#XS Ineff= 2 , 0
       0     520     221   555.5       0     221
Permanent Ineff=
       F       F
Bank Sta=518.06,552.36
XS Rating Curve= 0
Exp/Cntr=.5,.3

Type RM Length L Ch R = 1 ,8608.604,1188.25,1210.28,1180.28
XS GIS Cut Line= 3
     1925072.996       426806.67     1924948.983      426669.603
     1924231.013       426134.39
#Sta/Elev= 30
       0  225.95   25.71  224.48  172.63  218.64   197.9  217.04  217.47  217.17
  223.56  216.27   253.2   218.2   270.8  217.81  280.38  215.31  287.94   214.1
  353.96  214.04  455.35  212.73  471.43  212.99   484.6  212.36  494.98  212.76
  498.45  212.11  508.86  212.41  547.01  211.16  747.65  210.83  782.46  211.12
   893.5  210.65  958.81  211.56  977.66  213.06  989.61  215.42  993.22  215.26
 1000.99  216.12  1024.4  220.48 1052.51  221.84 1067.98  223.13 1080.35  223.33
#Mann= 3 , 0 , 0
       0     .13       0  747.65    .055       0  782.46     .13       0
Bank Sta=747.65,782.46
XS Rating Curve= 0
Exp/Cntr=.3,.1

Type RM Length L Ch R = 1 ,7398.322,1897.83,1975.96,2014.21
XS GIS Cut Line= 2
     1925471.143      425579.595     1924596.525       424959.53
#Sta/Elev= 30
       0  220.07   85.44  217.74   197.9  210.79  231.36  211.78  250.48   210.9
  408.09     212  434.37  211.78  482.62  211.81  496.28  210.79  533.35  212.45
  553.48  210.18  565.28  211.11  567.08  210.65  573.97  211.99  593.45  211.49
  602.61  212.51  615.88  210.63  664.58     210  681.28  210.88  715.94  210.06
  728.99  211.47  762.12  212.57  779.29  215.82  820.79  218.74   873.6  223.96
  903.42  223.58   915.3  224.67  950.02  225.56  1001.1  225.65 1072.12  227.79
#Mann= 3 , 0 , 0
       0     .13       0  408.09    .055       0  434.37     .13       0
Bank Sta=408.09,434.37
XS Rating Curve= 0
Exp/Cntr=.3,.1

Type RM Length L Ch R = 1 ,5422.359,1552.96,1644.79,1629.18
XS GIS Cut Line= 3
     1926763.488      424378.627     1926352.287      423752.035
     1926306.598      423660.657
#Sta/Elev= 30
       0  219.54   56.78  216.77   83.48  214.56  103.36  213.99  110.26   213.1
     129  211.93   155.5  211.64  177.09  208.18  189.55  207.41  216.65  208.38
  256.72  207.88  287.37  208.32  301.04  207.88  332.21   208.2  363.39  207.57
   377.4   207.5  384.11   206.9  400.35  207.67  431.11  208.43  467.55  207.69
  508.27  208.21  549.54  207.79  575.24  208.19  651.65  207.87  673.02   210.1
  687.45  213.17  706.13   215.4  723.56  216.76  766.26     219  851.63  222.43
#Mann= 3 , 0 , 0
       0     .13       0  363.39    .055       0  400.35     .13       0
Bank Sta=363.39,400.35
XS Rating Curve= 0
Exp/Cntr=.3,.1

Type RM Length L Ch R = 1 ,3777.575,1402.16,1445.78,1435.67
XS GIS Cut Line= 3
     1928147.212      423778.143     1927794.754       422981.85
     1927742.538      422818.675
#Sta/Elev= 30
       0  218.27   63.53  215.88    80.4  214.21  110.85   213.2  148.72  210.67
     173  208.43  223.85  206.13  297.83  206.25  404.62   204.5  459.89  205.39
  468.86   205.1  480.04  203.59  499.52  204.79  554.16  205.74  646.73  204.56
  670.83  205.67  701.37  204.29  732.76  205.06  740.41  205.85  743.19  205.04
   803.7  206.03  828.21  205.37   839.5  206.81  870.06  208.48  918.68   218.7
  934.61  220.52  941.52  222.65  944.34  222.27  956.62  224.71 1042.14   228.1
#Mann= 3 , 0 , 0
       0     .13       0  459.89    .055       0  499.52     .13       0
Bank Sta=459.89,499.52
XS Rating Curve= 0
Exp/Cntr=.5,.3

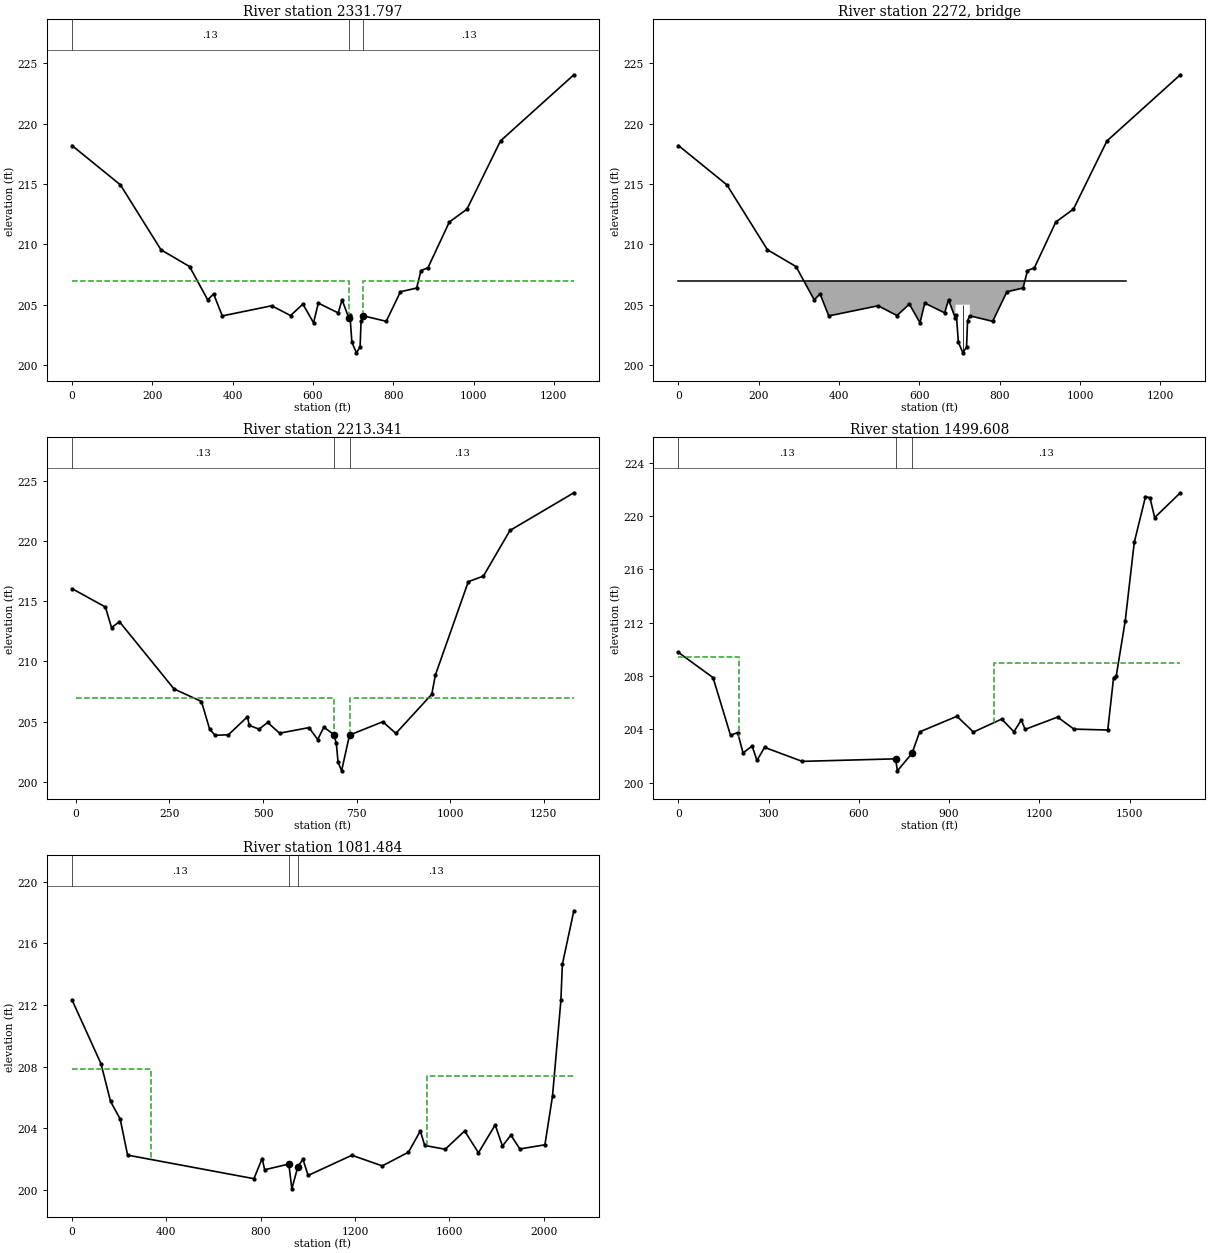
Type RM Length L Ch R = 1 ,2331.797,119.95,118.46,109.27
XS GIS Cut Line= 4
     1929312.281      423379.997      1929343.61      423087.587
     1929160.854      422549.762     1928993.763      422199.915
#Sta/Elev= 30
       0  218.19  120.64  214.93  221.69  209.55  292.86  208.16  338.07   205.4
  352.77  205.89  374.34  204.07  497.43  204.91  544.31   204.1   575.1  205.05
   601.6   203.5  613.48  205.13  663.03  204.32  672.62   205.4   689.4   203.9
  692.24  204.11  697.09  201.89  708.38  201.01  717.49   201.5  720.02  203.66
  725.26  204.08  782.58  203.62  817.94  206.07  858.31  206.38  869.23  207.83
  886.31  208.05  939.79  211.85  983.73  212.92 1067.15  218.57 1249.81  224.05
#Mann= 3 , 0 , 0
       0     .13       0   689.4    .055       0  725.26     .13       0
#XS Ineff= 2 , 0
       0     690     207  725.42       0     207
Permanent Ineff=
       F       F
Bank Sta=689.4,725.26
XS Rating Curve= 0
Exp/Cntr=.5,.3

Type RM Length L Ch R = 3 ,2272    ,,,
BEGIN DESCRIPTION:
SR1135; No. 98 from NCDOT database
END DESCRIPTION:
Bridge Culvert--1,0,-1,-1, 0
Deck Dist Width WeirC Skew NumUp NumDn MinLoCord MaxHiCord MaxSubmerge Is_Ogee
41.5,29.3,2.6,0, 10, 10, , , .95, 0, 1.5,1.5,,
       0  679.35     690  706.75  708.74  708.75  725.42   726.3 1110.23 1114.48
     207     207     207     207     207     207     207     207     207     207
                     205     205     205     205     205
       0  679.35     690  706.75  708.74  708.75  725.42   726.3 1110.23 1114.48
     207     207     207     207     207     207     207     207     207     207
                     205     205     205     205     205
Pier Skew, UpSta & Num, DnSta & Num=  ,708.75, 2 ,708.75, 2 , 0 , 0 , 0 ,,
       2       2
     180     210
       2       2
     180     210
BR Coef=-1 , 1 , 0 ,, 0 ,,,.8,0,1.2,1,
WSPro=,,,, 1 ,,,, 0 ,,,, 0 ,,,,-1 ,-1 ,-1 , 0 , 0 , 0 , 0 , 0
BC Design=,, 0 ,, 0 ,,,,,,

Type RM Length L Ch R = 1 ,2213.341,705.24,713.73,713.56
XS GIS Cut Line= 5
     1929468.929      423338.224     1929495.037      423139.803
     1929442.821      422993.598     1929171.298      422278.239
     1929077.309      422079.819
#Sta/Elev= 30
     -10  216.05   79.29  214.52   95.63  212.81  116.79   213.3  262.71  207.71
  335.89  206.67  357.45  204.39   372.1  203.86  407.98  203.91  458.71  205.41
  463.27  204.69  489.66  204.37  512.53  204.93  544.32  204.04  623.07   204.5
  646.09  203.51  662.58  204.54  689.26  203.92   695.9   203.2  700.46  201.65
  709.91  200.91  731.11  203.88  820.07  204.99  854.83  204.02  950.72  207.27
  960.34  208.87 1048.24  216.62  1088.6  217.09 1159.55  220.88 1330.09  224.01
#Mann= 3 , 0 , 0
     -10     .13       0  689.26    .055       0  731.11     .13       0
#XS Ineff= 2 , 0
       0  688.68     207  731.63       0     207
Permanent Ineff=
       F       F
Bank Sta=689.26,731.11
XS Rating Curve= 0
Exp/Cntr=.5,.3

Type RM Length L Ch R = 1 ,1499.608,364.98,418.12,497.32
XS GIS Cut Line= 4
     1930110.305      423196.844     1930176.228      423035.033
     1929846.613       422028.21     1929427.104      421914.343
#Sta/Elev= 30
       0  209.78  115.14  207.89  173.22  203.57  196.99  203.77  214.84  202.24
     245  202.76  261.26  201.68  286.42  202.66  411.62  201.61   722.1   201.8
  728.07   200.9  776.64  202.21  802.03  203.82  926.01  204.99  980.99  203.81
 1074.75  204.78 1115.55  203.83 1140.09  204.71 1152.87  204.01 1260.74  204.93
    1315  204.03 1427.52  203.96 1446.94  207.89 1455.87  208.03 1485.63  212.14
  1515.7  218.03    1553  221.46 1567.84  221.38 1583.56  219.89 1668.82  221.75
#Mann= 3 , 0 , 0
       0     .13       0   722.1    .055       0  776.64     .13       0
#XS Ineff= 2 , 0
          201.32   209.4 1048.03          208.98
Permanent Ineff=
       F       F
Bank Sta=722.1,776.64
XS Rating Curve= 0
Exp/Cntr=.3,.1

Type RM Length L Ch R = 1 ,1081.484,0,0,0
XS GIS Cut Line= 4
      1930260.13      423298.725     1930385.983      423124.928
     1930403.962      421920.336     1930751.556      421303.057
#Sta/Elev= 30
       0  212.34  123.28  208.18  163.61  205.74  204.51  204.59  235.87  202.25
  771.46  200.72  806.14  202.03     817   201.3  919.44  201.67  932.22  200.06
  957.67   201.5  979.34  201.98 1001.08  200.93 1186.57  202.24  1315.6  201.55
 1426.46  202.44 1477.02  203.82 1495.37  202.88 1582.33  202.63 1664.75  203.82
 1723.35   202.4 1794.13  204.21 1825.13  202.84 1860.69  203.55 1898.69  202.65
    2005  202.92 2037.21  206.08 2072.82  212.31 2078.98  214.64 2127.72  218.12
#Mann= 3 , 0 , 0
       0     .13       0  919.44    .055       0  957.67     .13       0
#XS Ineff= 2 , 0
          337.17  207.85 1504.93          207.38
Permanent Ineff=
       F       F
Bank Sta=919.44,957.67
XS Rating Curve= 0
Exp/Cntr=.3,.1

River Reach=Unmd Trib to Raf,one
Reach XY= 30
      1935541.48       427602.55      1935455.77       427564.46
      1935331.97       427383.51      1935227.21       427307.33
      1935065.32       427278.76      1934874.85       427212.09
      1934770.09       427059.72      1934741.52       426916.87
      1934684.38        426850.2      1934503.44       426459.75
      1934322.49       425955.01      1933865.37       425050.29
      1933808.23       424907.44      1933760.61       424412.22
      1933770.14        423793.2      1933655.86       423355.13
      1933522.53       423117.04      1933379.68        422774.2
      1933251.11       422583.73      1933117.79       422517.07
      1932974.94       422402.79      1932927.32       422307.56
      1932841.61       422231.37      1932803.52       422155.18
      1932717.81       422098.04      1932527.34       422050.43
      1932403.53       421955.19      1932279.73       421840.91
      1932203.54       421659.97      1931998.79       421517.12

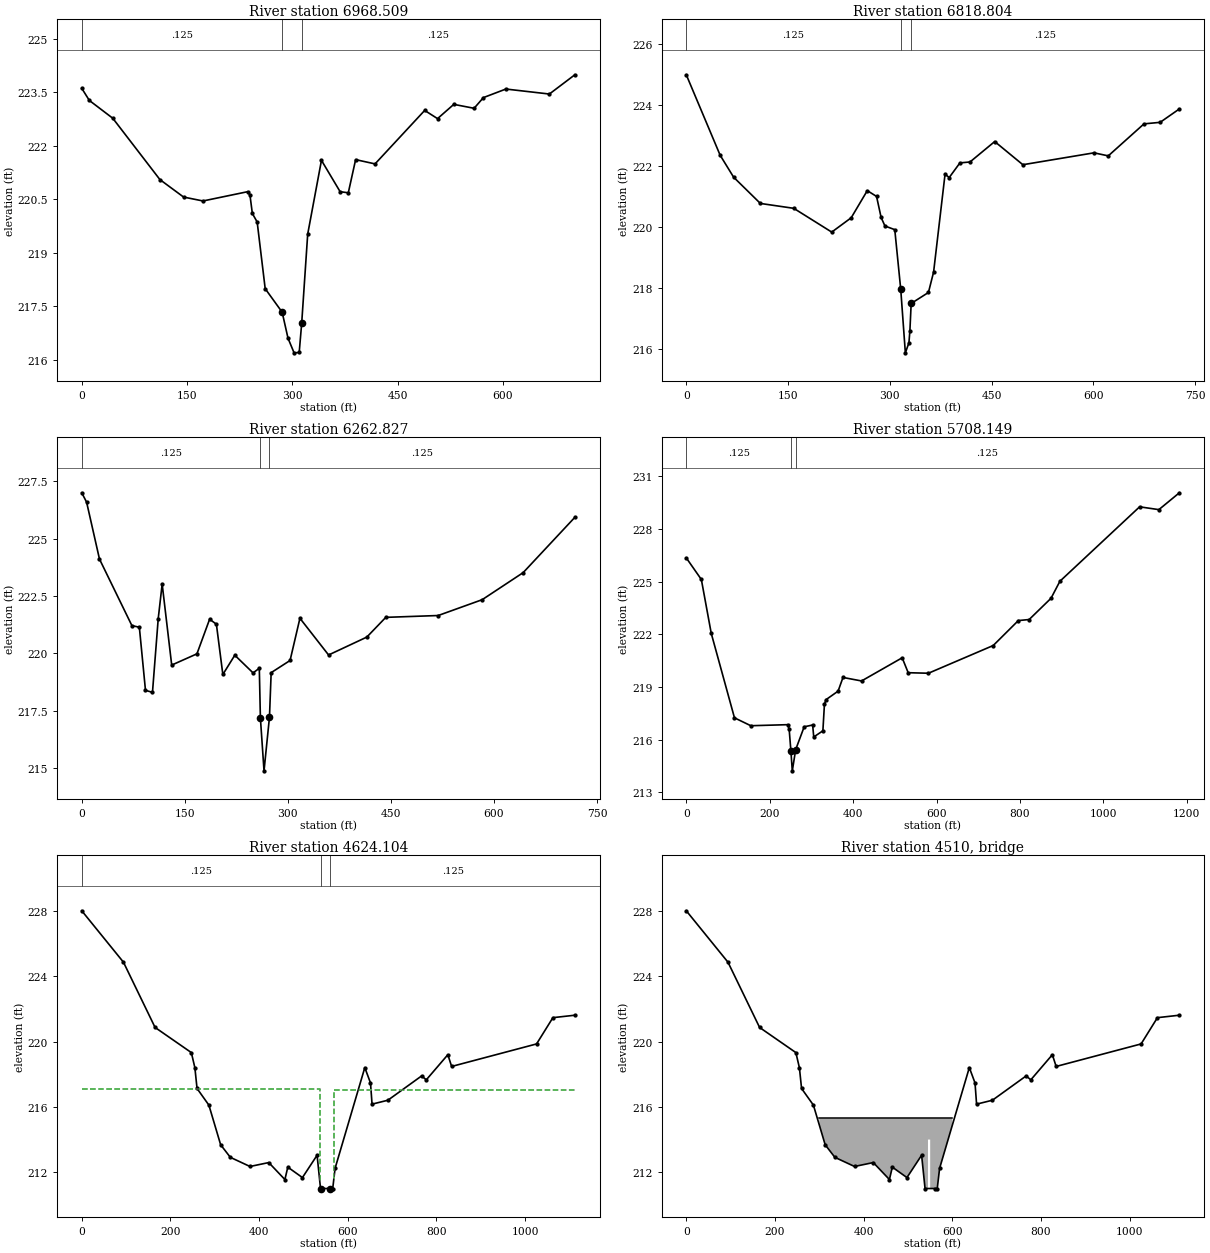
Type RM Length L Ch R = 1 ,6968.509,129.31,149.71,158.74
XS GIS Cut Line= 2
      1935200.03      426982.315     1935021.248      427661.687
#Sta/Elev= 30
       0  223.61    10.8  223.27   44.21  222.77  111.34  221.05  145.06  220.56
  172.72  220.45  236.26  220.71  239.61  220.62  243.03   220.1  249.91  219.86
  261.33  217.99   285.5  217.33  293.84   216.6   302.5  216.19  309.79   216.2
  313.37  217.03  321.89  219.52  341.49  221.59   368.1  220.71  379.74  220.68
  390.17  221.61  417.83  221.49  488.55  222.99  506.88  222.76  530.03  223.16
  558.96  223.05  572.22  223.35  604.22  223.59  666.21  223.45   702.5  223.99
#Mann= 3 , 0 , 0
       0    .125       0   285.5     .05       0  313.37    .125       0
Bank Sta=285.5,313.37
XS Rating Curve= 0
Exp/Cntr=.3,.1

Type RM Length L Ch R = 1 ,6818.804,441.97,555.98,615.16
XS GIS Cut Line= 2
     1935103.781      426930.105     1934832.224      427604.317
#Sta/Elev= 30
       0  224.99   49.94  222.35   69.82  221.63  109.22  220.77  158.42  220.61
  214.43  219.83  243.09   220.3   266.8  221.19  280.48     221   287.2  220.31
  292.85  220.03  307.33  219.91  316.13  217.95  322.93  215.87   328.2   216.2
  329.63   216.6   331.5  217.49  356.96  217.85  364.56  218.52  381.44  221.73
  387.56  221.62  403.37   222.1  418.21  222.13  454.65   222.8  496.15  222.04
     601  222.43  622.02  222.33  674.69  223.38  698.48  223.43  726.85  223.87
#Mann= 3 , 0 , 0
       0    .125       0  316.13     .05       0   331.5    .125       0
Bank Sta=316.13,331.5
XS Rating Curve= 0
Exp/Cntr=.3,.1

Type RM Length L Ch R = 1 ,6262.827,550.07,554.68,556.22
XS GIS Cut Line= 2
     1934909.452      426689.456     1934282.996      427039.973
#Sta/Elev= 30
       0     227    7.06  226.59    25.8  224.11   72.99  221.21   83.84  221.14
   92.76  218.39  102.95   218.3  111.34  221.52  117.06  223.02  130.94  219.49
  167.67  219.98  186.15  221.49  196.01  221.27  205.39  219.08   222.8  219.92
  249.37  219.15  258.47  219.35  260.05  217.19  265.34  214.88  273.27  217.22
  275.73  219.16  303.25  219.69  317.61  221.53  359.33  219.93  414.99  220.71
  442.61  221.57  518.88  221.65  582.93  222.34  642.61  223.52  717.85  225.93
#Mann= 3 , 0 , 0
       0    .125       0  260.05     .05       0  273.27    .125       0
#XS Ineff= 2 , 0
       0     117     223               0
Permanent Ineff=
       F       F
Bank Sta=260.05,273.27
XS Rating Curve= 0
Exp/Cntr=.3,.1

Type RM Length L Ch R = 1 ,5708.149,1131.44,1084.05,1035.39
XS GIS Cut Line= 4
     1934693.792      426192.576     1934270.365      426404.254
     1934097.542       426642.63     1933869.965      426988.942
#Sta/Elev= 30
       0  226.36   36.14  225.13   59.87  222.06  115.52  217.25  154.69   216.8
  243.17  216.86  246.64  216.61  250.76  215.38  254.17  214.23  262.29  215.44
  282.68  216.74  302.96  216.84  305.61  216.16  327.51  216.51   331.2  218.01
  334.71  218.28  363.95  218.77  375.71  219.55  420.22  219.35  517.62  220.67
  532.03  219.82  580.53  219.79  735.95  221.37   796.1  222.79  822.09  222.85
  874.45  224.06   895.8  225.03 1086.89  229.27 1133.05  229.11 1182.22  230.07
#Mann= 3 , 0 , 0
       0    .125       0  250.76     .05       0  262.29    .125       0
Bank Sta=250.76,262.29
XS Rating Curve= 0
Exp/Cntr=.5,.3

Type RM Length L Ch R = 1 ,4624.104,149.07,126.24,106.3
XS GIS Cut Line= 4
     1934416.095      424983.161     1934266.708      425029.126
      1933853.02      425506.017     1933726.615      425804.791
#Sta/Elev= 30
       0  228.02   94.02  224.87  165.35  220.87  247.13  219.33  255.12   218.4
  259.99  217.13   286.7  216.11  313.24  213.68   335.1  212.91   379.4  212.35
  421.75  212.59  458.11  211.55  464.67  212.31  497.66  211.67  530.72  213.04
  538.46     211  560.46     211  565.89  210.98  571.32  212.24  638.32  218.41
  651.16  217.47  654.67  216.17  690.35  216.41  766.46   217.9  776.99  217.66
   825.6   219.2  834.13  218.48 1025.68  219.86 1062.52  221.47 1112.03  221.62
#Mann= 3 , 0 , 0
       0    .125       0  538.46     .05       0  560.46    .125       0
#XS Ineff= 2 , 0
          536.84  217.11  568.42          217.05
Permanent Ineff=
       F       F
Bank Sta=538.46,560.46
XS Rating Curve= 0
Exp/Cntr=.5,.3

Type RM Length L Ch R = 3 ,4510    ,,,
BEGIN DESCRIPTION:
Andrews Rd; opening size estimated from similar road class
END DESCRIPTION:
Bridge Culvert--1,0,-1,-1, 0
Deck Dist Width WeirC Skew NumUp NumDn MinLoCord MaxHiCord MaxSubmerge Is_Ogee
49,20,2.6,0, 5, 5, 215, , .95, 0, 0,0,,
     300  545.04  550.07  552.86     600
   215.3   215.3   215.3   215.3   215.3
             214     214
     200  545.04  550.07  552.86     700
   215.3   215.3   215.3   215.3   215.3
             214     214
BR Coef=-1 , 1 , 0 ,, 0 ,,,.8,0,1.2,1,
WSPro=,,,, 1 ,,,, 0 ,,,, 0 ,,,,-1 ,-1 ,-1 , 0 , 0 , 0 , 0 , 0
BC Design=,, 0 ,, 0 ,,,,,,

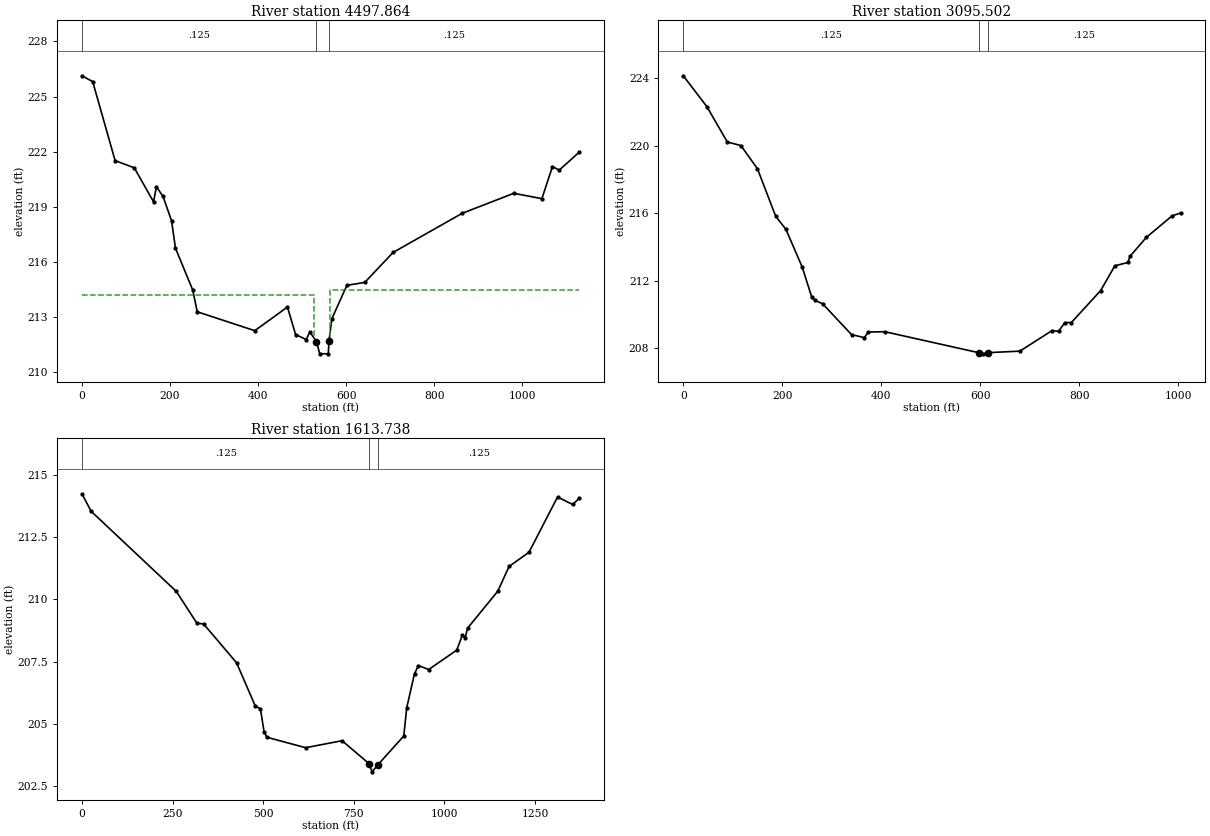
Type RM Length L Ch R = 1 ,4497.864,1297.32,1402.36,1516.6
XS GIS Cut Line= 3
     1934306.928      424822.283     1934088.592      424994.652
     1933640.431      425718.606
#Sta/Elev= 30
       0  226.13   24.37  225.81   75.32  221.51  118.82  221.12  162.56  219.27
  169.19  220.09  184.15  219.56  203.48  218.24  212.44  216.74  251.53  214.47
  261.92  213.28   392.6  212.25  466.85  213.54  485.27  212.04  509.43  211.77
  517.67  212.18  532.78  211.66     540     211  559.53  210.99  561.18  211.68
  567.49  212.89  601.83  214.72  642.51  214.88  706.78  216.51  863.64  218.64
  980.89  219.73 1044.87  219.44 1068.91  221.19 1084.08  220.99 1129.62  221.97
#Mann= 3 , 0 , 0
       0    .125       0  532.78     .05       0  561.18    .125       0
#XS Ineff= 2 , 0
          527.27  214.19  562.66          214.47
Permanent Ineff=
       F       F
Bank Sta=532.78,561.18
XS Rating Curve= 0
Exp/Cntr=.5,.3

Type RM Length L Ch R = 1 ,3095.502,1522.18,1481.76,1399.15
XS GIS Cut Line= 4
     1934352.893        423805.3     1934094.338      423799.554
     1933559.991      423879.994     1933364.639      423943.196
#Sta/Elev= 30
       0  224.14   47.66  222.31   88.88  220.22  116.28  220.01   149.7  218.64
  186.66  215.82  207.28  215.05  240.35   212.8  259.49  211.03  266.05  210.84
   281.2  210.65  339.71  208.82  365.52  208.64  373.76  208.97  407.01  208.99
  596.36  207.75  605.87  207.68  615.95  207.75  679.78  207.84  744.99  209.06
  757.86  209.01  770.63  209.53  783.69  209.53  842.78  211.42  871.58  212.89
  898.01  213.09  902.11  213.45  935.07  214.57  986.84  215.84 1004.31  216.02
#Mann= 3 , 0 , 0
       0    .125       0  596.36     .05       0  615.95    .125       0
Bank Sta=596.36,615.95
XS Rating Curve= 0
Exp/Cntr=.3,.1

Type RM Length L Ch R = 1 ,1613.738,0,0,0
BEGIN DESCRIPTION:
cp RTRIB
END DESCRIPTION:
XS GIS Cut Line= 4
     1933867.726      422444.723       1933483.8       422322.99
     1932978.141       422669.46     1932996.869      423025.294
#Sta/Elev= 30
       0  214.24   25.09  213.54  260.17  210.32  317.15  209.04   335.7  209.01
  426.65  207.45  478.01  205.72  492.44   205.6  502.41  204.69  510.08  204.46
  617.05  204.04  717.68  204.32  792.95  203.39  800.41  203.07  816.92  203.36
  887.99  204.51  896.06  205.64  917.68  207.02  928.59  207.34  956.59  207.18
 1034.27  207.96 1049.53  208.56 1057.46  208.45 1063.97  208.84 1147.56  210.33
 1178.42  211.32 1233.52  211.89 1312.22  214.11 1353.94  213.81 1372.06  214.06
#Mann= 3 , 0 , 0
       0    .125       0  792.95     .05       0  816.92    .125       0
Bank Sta=792.95,816.92
XS Rating Curve= 0
Exp/Cntr=.3,.1

River Reach=Toneys          ,upper
Reach XY= 30
      1917199.47       449230.13      1918008.96       448400.43
      1918161.33       448011.13      1918113.72       446858.81
      1918285.14       446535.01      1919123.19       445335.07
      1919515.68       445055.07      1919676.12       444257.39
       1920451.7       443220.88      1921442.13       442773.28
      1921760.28       442192.86      1922413.52        442049.5
      1922694.46       441849.51      1923580.13       440954.32
      1923802.71      440429.701      1925437.19       440078.17
      1926108.59       440144.83      1926251.44       440268.63
     1926674.185      440237.749       1926889.5       439792.47
      1927127.59       438763.94      1927937.07       438040.17
      1928146.59       437706.85      1928660.85       437506.86
      1928827.75       437296.85      1928884.65       436030.73
      1929389.39       434849.84      1929632.23       433687.98
      1929860.79       433335.62      1930081.74      433326.812