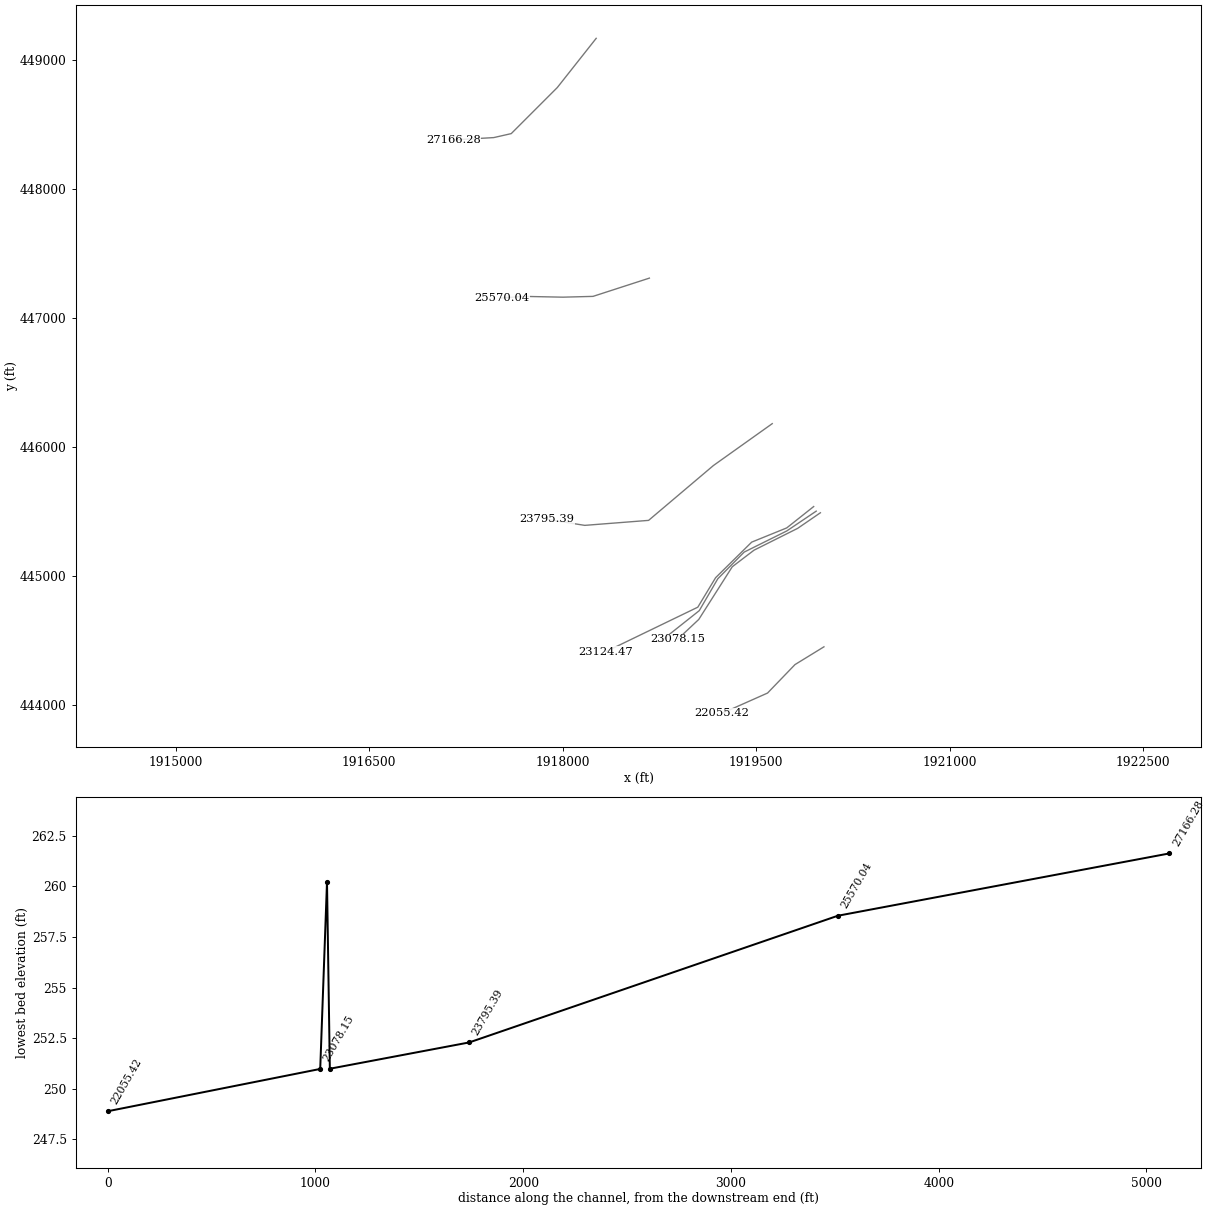
HEC-RAS study upraft.prj: Upper Raft Swamp

--- upraft.g04 (geometry) --- (continued)

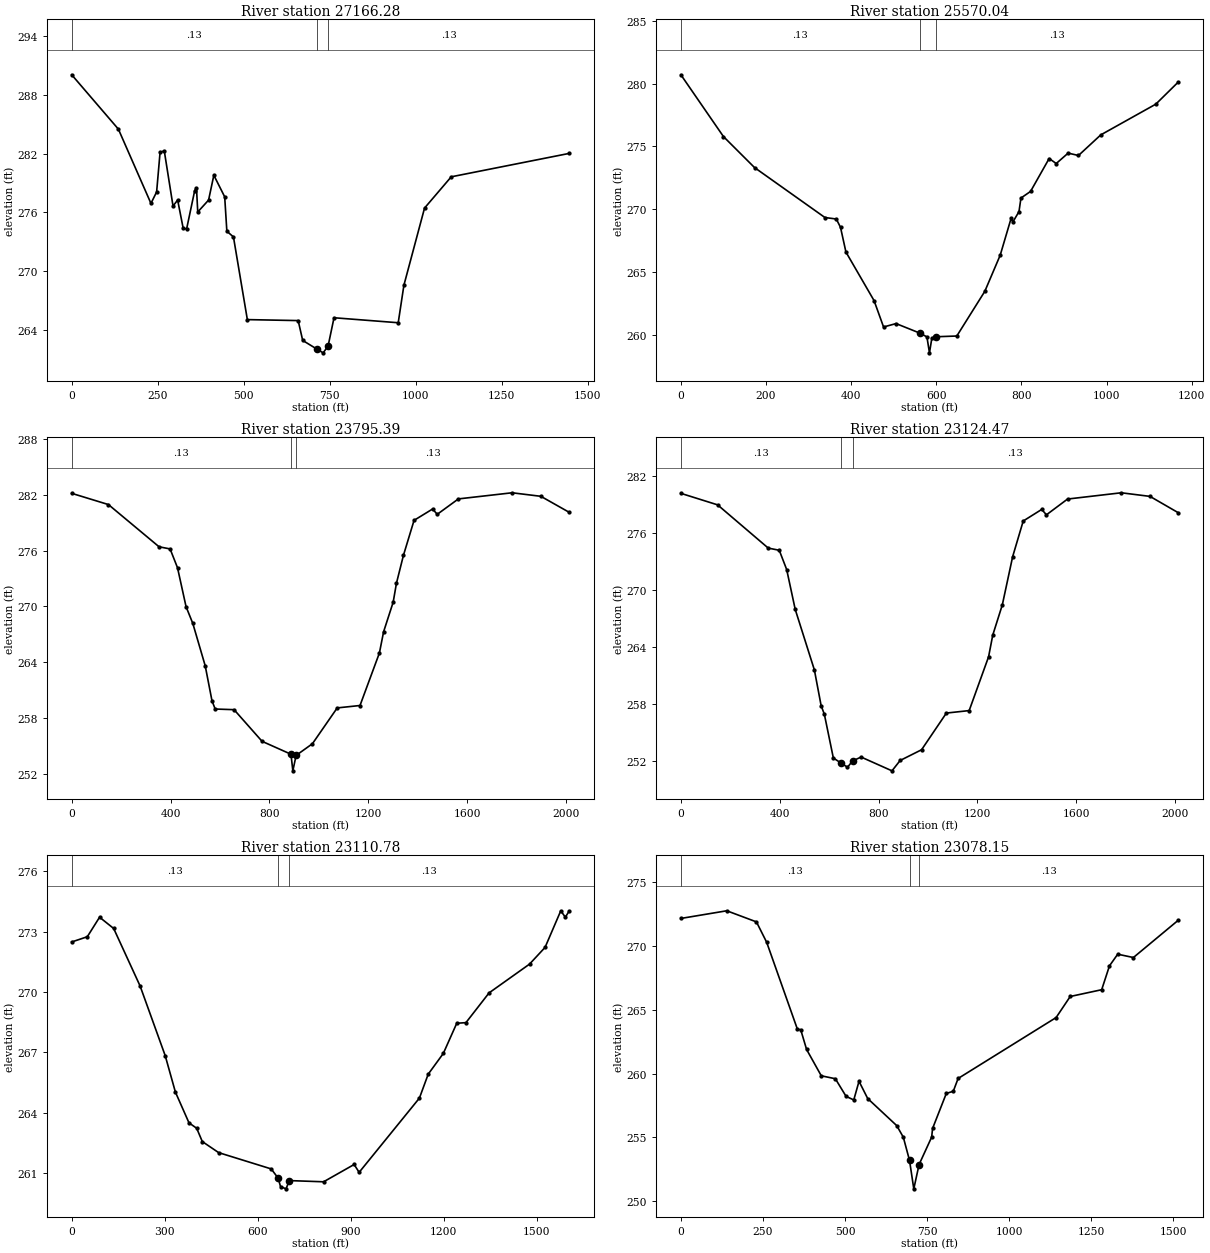
Type RM Length L Ch R = 1 ,27166.28,1635.72,1596.24,1519.48
XS GIS Cut Line= 5
     1918259.883      449166.564     1917958.195      448784.836
     1917601.094      448427.735     1917465.642      448396.951
      1917151.64       448378.48
#Sta/Elev= 30
       0  290.08  135.58  284.52  230.27  276.92  246.75  278.09  256.72  282.13
  268.97   282.3   294.4  276.65  307.86  277.26  323.91  274.38  333.94  274.31
  357.38  278.23  362.59  278.52  366.24  276.04  397.74  277.26  413.01   279.8
  444.57  277.59  450.85  274.07  470.02  273.49  510.41  265.03  658.11  264.93
  671.22   262.9  712.19  262.02  730.62  261.63  744.96  262.31  762.25  265.22
  948.85  264.71  965.38  268.55 1025.31  276.44 1102.89  279.64 1445.02  282.03
#Mann= 3 , 0 , 0
       0     .13       0  712.19    .055       0  744.96     .13       0
Bank Sta=712.19,744.96
XS Rating Curve= 0
Exp/Cntr=.3,.1

Type RM Length L Ch R = 1 ,25570.04,1699.22,1774.65,1827.84
XS GIS Cut Line= 5
     1918672.395      447307.179     1918235.255       447165.57
     1918001.293      447159.413     1917699.605       447165.57
     1917527.211      447153.256
#Sta/Elev= 30
       0   280.7   99.97  275.78  172.97  273.31  338.37  269.33  365.12  269.21
     375  268.55  387.73  266.58  453.82  262.71  476.12  260.61  505.55  260.88
  561.48  260.12  578.01  259.82  583.99  258.55  589.62  259.73  598.38  259.83
  648.21  259.89  714.01  263.45  750.17  266.33  776.01  269.29  779.69  268.96
  794.28   269.8   798.9  270.88  821.49  271.41  865.15  274.03  881.75  273.63
  909.77  274.46  934.01  274.27  986.36  275.91  1115.7  278.36 1168.13  280.11
#Mann= 3 , 0 , 0
       0     .13       0  561.48    .055       0  598.38     .13       0
Bank Sta=561.48,598.38
XS Rating Curve= 0
Exp/Cntr=.3,.1

Type RM Length L Ch R = 1 ,23795.39,654.47,670.92,667.13
XS GIS Cut Line= 5
     1919625.204      446178.718     1919168.924      445853.909
     1918666.243      445428.563     1918171.295      445389.895
      1917877.42      445436.297
#Sta/Elev= 30
       0  282.19  148.56  280.98  353.55  276.43  398.19   276.2  428.23  274.17
  462.77  269.98  490.15  268.17  540.31  263.61  567.73  259.84  580.65  258.95
  657.12  258.88  770.42  255.47  887.42  254.08  895.01  252.29  908.18  253.95
  974.23  255.21  1074.6  259.07 1166.83  259.33 1245.38  264.99 1262.26  267.27
 1301.04  270.46  1314.4  272.51 1342.73  275.52  1385.6  279.28 1460.54   280.5
 1479.52  279.93 1565.02  281.59 1782.46  282.25 1898.75  281.87 2012.54  280.16
#Mann= 3 , 0 , 0
       0     .13       0  887.42    .055       0  908.18     .13       0
Bank Sta=887.42,908.18
XS Rating Curve= 0
Exp/Cntr=.3,.1

Type RM Length L Ch R = 1 ,23124.47,24.12,13.69,12.53
XS GIS Cut Line= 6
     1919946.382      445535.715      1919737.54      445370.217
     1919465.651      445259.885     1919185.881      444984.056
     1919047.967      444755.512 1918334.1804371  444410.3861374
#Sta/Elev= 30
       0  280.19  148.56  278.98  353.55  274.43  398.19   274.2  428.23  272.17
  462.77  267.98  540.31  261.61  567.73  257.84  580.65  256.95  617.09  252.34
   648.1  251.81  674.35  251.37  695.38  252.04  729.55  252.44  854.43  250.99
  887.42  252.08  974.23  253.21  1074.6  257.07 1166.83  257.33 1245.38  262.99
 1262.26  265.27 1301.04  268.46 1342.73  273.52  1385.6  277.28 1460.54   278.5
 1479.52  277.93 1565.02  279.59 1782.46  280.25 1898.75  279.87 2012.54  278.16
#Mann= 3 , 0 , 0
       0     .13       0   648.1    .055       0  695.38     .13       0
Bank Sta=648.1,695.38
XS Rating Curve= 0
Exp/Cntr=.3,.1

Type RM Length L Ch R = 1 ,23110.78,31.86,32.64,24.89
XS GIS Cut Line= 6
     1919966.084      445500.251      1919737.54      445346.417
     1919407.175      445182.496     1919202.904      444975.702
     1919059.157      444728.559     1918760.316      444491.504
#Sta/Elev= 30
       0  272.49   50.31  272.75   89.89  273.72  135.42  273.16  220.73   270.3
   301.7  266.84  334.58  265.03  378.46   263.5  403.31  263.23   421.4  262.57
  474.16  262.02  643.84  261.21     666260.7558  673.99  260.33  691.83  260.22
  701.89  260.63  812.86  260.57   911.4  261.43  927.56  261.04 1122.08  264.73
  1150.5  265.92  1199.2  266.95 1242.58  268.45 1272.22  268.48 1346.93  269.96
 1477.54  271.39 1527.55  272.22  1578.3  274.04    1593  273.72 1604.68  274.01
#Mann= 3 , 0 , 0
       0     .13       0     666    .055       0  701.89     .13       0
Bank Sta=666,701.89
XS Rating Curve= 0
Exp/Cntr=.3,.1

Type RM Length L Ch R = 1 ,23078.15,990.25,1022.73,1024.71
XS GIS Cut Line= 6
     1919998.553      445487.642     1919822.022      445366.592
     1919484.092      445197.627     1919315.127      445069.012
     1919055.375      444660.469     1918891.453      444506.635
#Sta/Elev= 30
       0  272.15  139.81  272.75  230.18  271.88  261.41  270.28  355.07  263.47
  365.03  263.44  382.99  261.89  427.71  259.83   470.6   259.6  503.26  258.22
  526.66  257.94  542.65   259.4   569.1  258.05  657.53  255.93  677.62  255.02
  696.47  253.21  709.52  250.98  725.59  252.88  763.94  255.03  766.79  255.71
  808.59  258.45  829.81  258.62  844.49  259.62 1143.06  264.39 1186.06  266.04
 1281.89  266.57  1305.6  268.44 1330.74  269.35  1378.5  269.09 1514.74     272
#Mann= 3 , 0 , 0
       0     .13       0  696.47    .055       0  725.59     .13       0
Bank Sta=696.47,725.59
XS Rating Curve= 0
Exp/Cntr=.3,.1

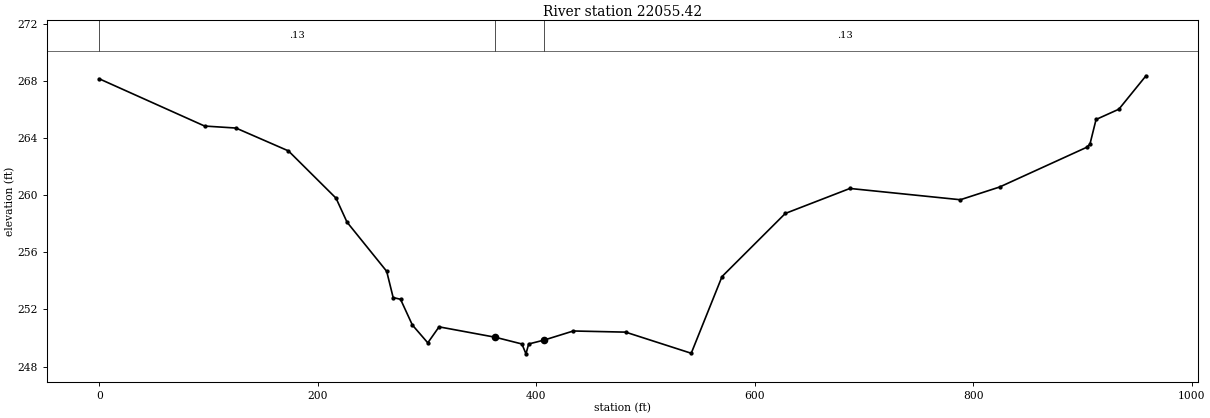
Type RM Length L Ch R = 1 ,22055.42,1362.82,1378.49,1357.78
XS GIS Cut Line= 4
     1920026.057      444448.159     1919801.453      444310.245
     1919588.671      444089.581     1919234.033      443931.965
#Sta/Elev= 30
       0  268.15   96.51  264.84   125.2   264.7  173.22   263.1  216.79  259.79
  226.86  258.11  263.15  254.67  269.09  252.83  275.84  252.71  286.65  250.91
  300.79  249.66  311.09  250.78   362.7  250.05  386.94  249.58  390.66  248.89
  393.12  249.58  407.09  249.85     434  250.49  481.86  250.41  541.93  248.93
  570.11   254.3  628.03  258.72  687.18  260.47  788.27  259.68  824.16  260.57
  903.86  263.35  906.89  263.57  912.49   265.3  933.38  266.02   958.2  268.36
#Mann= 3 , 0 , 0
       0     .13       0   362.7    .055       0  407.09     .13       0
Bank Sta=362.7,407.09
XS Rating Curve= 0
Exp/Cntr=.3,.1