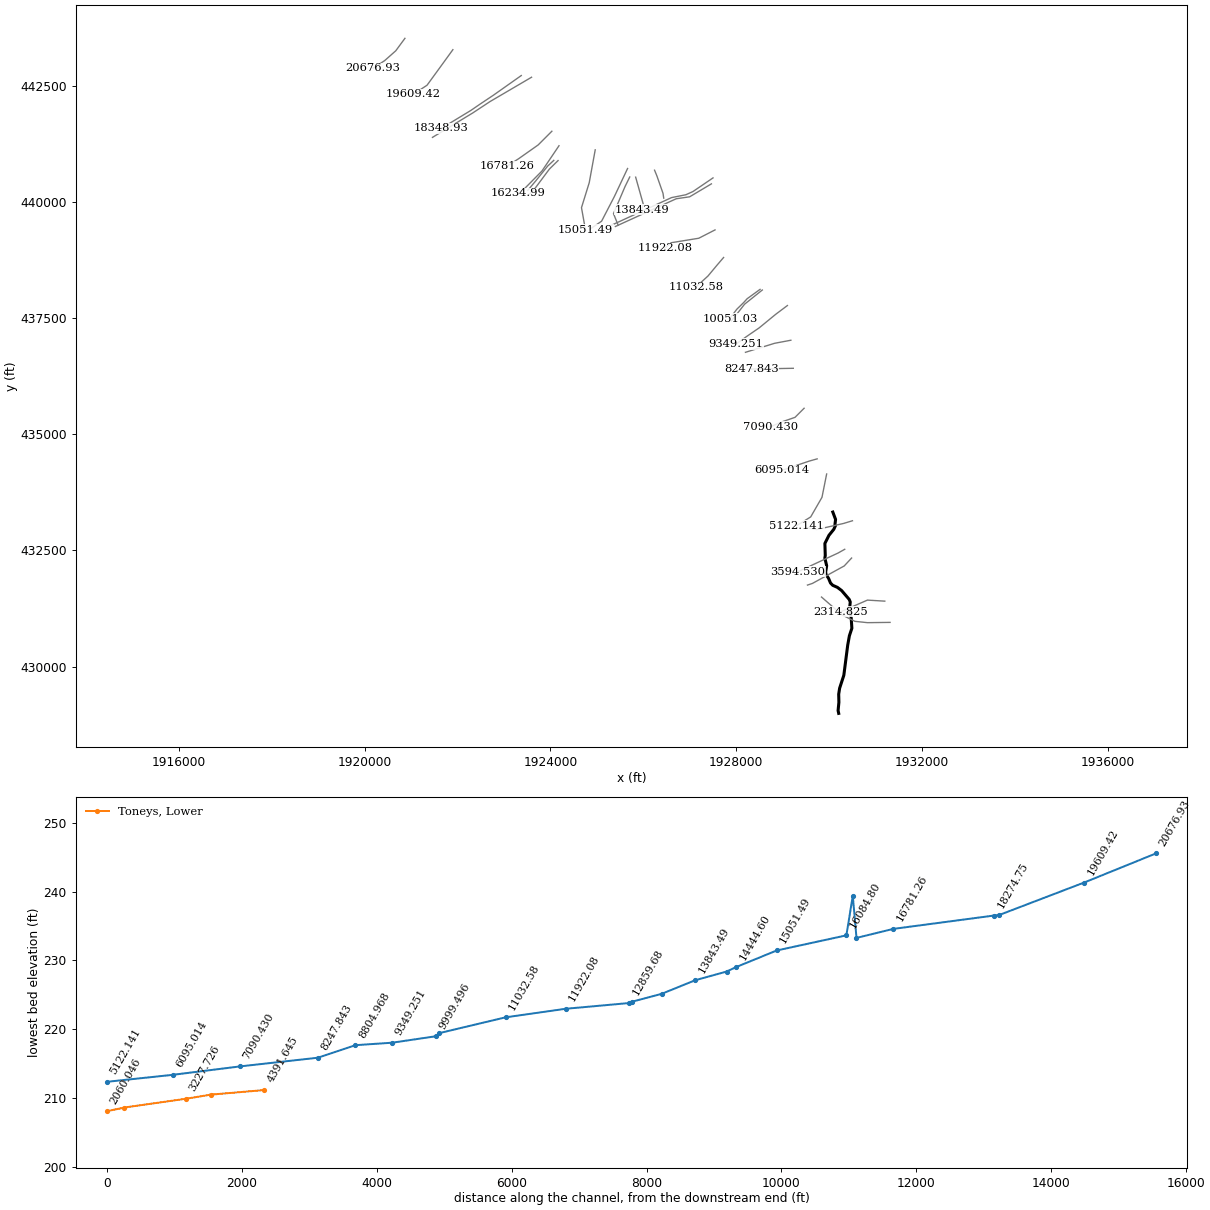
HEC-RAS study upraft.prj: Upper Raft Swamp

--- upraft.g04 (geometry) --- (continued)

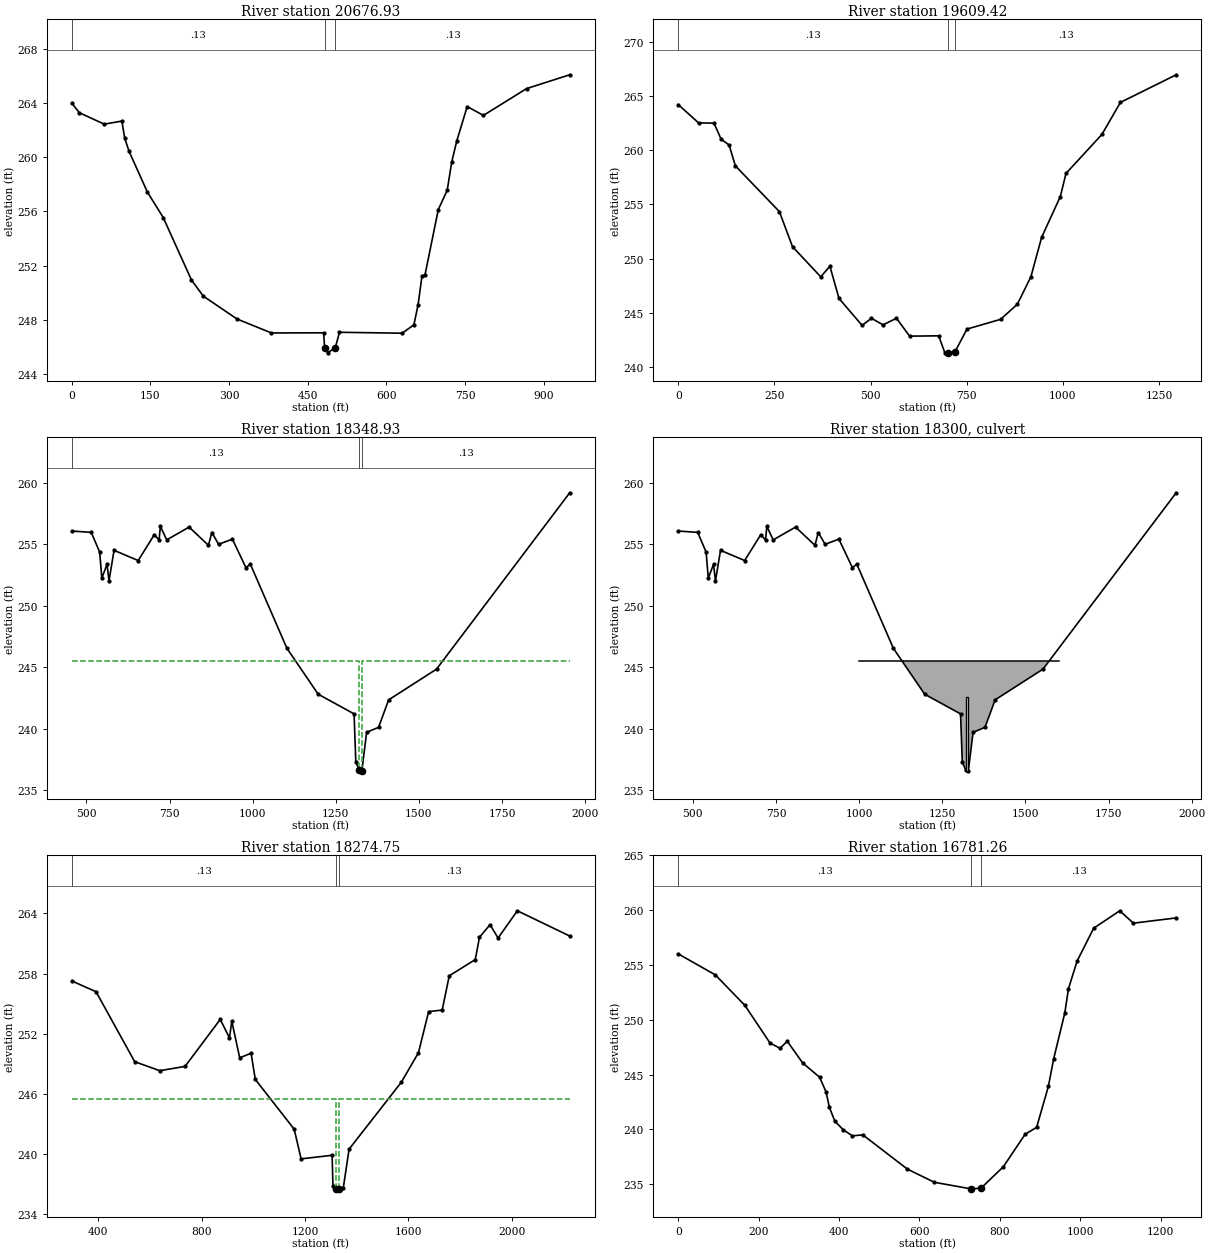
Type RM Length L Ch R = 1 ,20676.93,1037.85,1067.52,1069.53
XS GIS Cut Line= 4
     1920869.307      443526.101     1920672.286      443258.153
      1920431.92       443045.37     1920183.674      442883.813
#Sta/Elev= 30
       0  264.01   14.32   263.3   61.92  262.45   95.58  262.68     101  261.42
  109.12  260.46  144.28  257.43  174.44  255.55  228.35  250.93  250.92  249.74
  315.27  248.05  380.79  247.02  480.38  247.03  482.37  245.91  488.05  245.55
  502.67  245.93  510.57  247.07  630.14     247  652.58  247.62  660.65  249.12
  667.88   251.2   673.8  251.32  699.12  256.14   716.1  257.56   724.6  259.63
  734.26   261.2  754.24  263.75  785.19   263.1  867.62  265.08  949.79   266.1
#Mann= 3 , 0 , 0
       0     .13       0  482.37    .055       0  502.67     .13       0
Bank Sta=482.37,502.67
XS Rating Curve= 0
Exp/Cntr=.3,.1

Type RM Length L Ch R = 1 ,19609.42,1236.23,1260.48,1189.76
XS GIS Cut Line= 4
     1921901.696      443281.796     1921641.629      442923.217
     1921346.097      442517.354     1921054.506      442324.274
#Sta/Elev= 30
       0  264.21   53.06  262.52      93   262.5  111.56  261.02  132.27  260.48
  148.59  258.56  262.98  254.34  297.21   251.1  370.58  248.32   394.3   249.3
  418.02  246.33  478.03  243.84   502.4   244.5  532.48  243.89  567.43   244.5
  601.65  242.85   677.2  242.88  693.25  241.31  701.27  241.32  719.33  241.39
  750.75   243.5   838.2   244.4  881.66  245.79  916.96  248.33  945.02  251.98
  993.56  255.73  1008.2  257.86 1101.69  261.46 1149.68  264.41 1294.74  266.96
#Mann= 3 , 0 , 0
       0     .13       0  701.27    .055       0  719.33     .13       0
Bank Sta=701.27,719.33
XS Rating Curve= 0
Exp/Cntr=.5,.3

Type RM Length L Ch R = 1 ,18348.93,74.49,74.18,89.39
XS GIS Cut Line= 6
 1923374.4679196  442725.0759358 1923222.5120226  442617.8126831
     1922775.245      442302.094     1922491.258       442112.77
     1922290.101      441974.721 1921654.6186174  441588.6050316
#Sta/Elev= 30
     456  256.09  514.66  255.98  539.98  254.37  546.38  252.26  562.13  253.38
  567.99  252.04  583.25  254.52  655.79  253.69  704.13  255.79  718.64  255.36
  722.45  256.47  741.61  255.37  808.82  256.41  867.08  254.93  877.21  255.97
  897.69  255.01  939.08  255.43   979.6  253.12  993.15  253.39 1103.05  246.55
 1197.11  242.82 1304.99  241.22 1310.13  237.32 1320.57  236.65 1328.33  236.59
 1342.65  239.72 1378.59  240.13 1408.87  242.36 1552.87  244.86 1953.39   259.2
#Mann= 3 , 0 , 0
     456     .13       0 1320.57    .055       0 1328.33     .13       0
#XS Ineff= 2 , 0
       0 1320.57   245.5 1328.56       0   245.5
Permanent Ineff=
       F       F
Bank Sta=1320.57,1328.33
XS Rating Curve= 0
Exp/Cntr=.5,.3

Type RM Length L Ch R = 2 ,18300   ,,,
BEGIN DESCRIPTION:
US401; NCDOT small pipes; 46 2009
END DESCRIPTION:
Bridge Culvert--1,0,-1,-1, 0
Deck Dist Width WeirC Skew NumUp NumDn MinLoCord MaxHiCord MaxSubmerge Is_Ogee
6,60,2.6,0, 2, 2, , , .95, 0, 0,0,,
    1000    1600
   245.5   245.5
                
    1000    1600
   245.5   245.5
                
Culvert=2,6,6,60,.03,.5,1,8,1,236.6,1325,236.5,1325,Culvert #1  , 0 ,1
Culvert Bottom n=.03
BC Design=,, 0 ,, 0 ,,,,,,

Type RM Length L Ch R = 1 ,18274.75,1471.98,1493.49,1420.39
XS GIS Cut Line= 6
 1923595.7912204  442688.8196114 1923342.2151561  442540.2186291
     1922700.304      442164.045     1922329.543      441919.501
   1921584.20646  441467.4907678 1921462.7893934  441393.8572432
#Sta/Elev= 30
     298  257.27  392.01  256.19  541.44  249.21  638.39  248.31  736.23  248.74
  872.36  253.43  907.99  251.59  917.06  253.24  947.62   249.6  991.73  250.05
 1007.92  247.44 1158.45  242.47 1185.12  239.51 1305.16  239.87  1308.3  236.85
 1319.68  236.53 1330.21  236.52 1348.12  236.58 1370.73  240.48 1572.75  247.16
 1638.98   250.1 1678.42  254.21 1730.77  254.36 1758.16  257.78 1858.79   259.4
 1875.05  261.63 1916.03  262.88 1946.98  261.55 2021.67  264.27 2224.16  261.75
#Mann= 3 , 0 , 0
     298     .13       0 1319.68    .055       0 1330.21     .13       0
#XS Ineff= 2 , 0
       0 1319.86   245.5 1330.21       0   245.5
Permanent Ineff=
       F       F
Bank Sta=1319.68,1330.21
XS Rating Curve= 0
Exp/Cntr=.5,.3

Type RM Length L Ch R = 1 ,16781.26,595.72,546.27,612.08
XS GIS Cut Line= 4
     1924032.847      441526.061     1923737.028      441230.242
      1923317.95      440934.422     1923059.108      440768.024
#Sta/Elev= 30
       0     256   92.17  254.09  165.79  251.31  228.29  247.88  253.48  247.39
  271.23  248.04  309.86  246.05  351.73  244.76  367.83  243.42  376.04  242.02
  389.52  240.76  411.03  239.95  433.47  239.41  459.27   239.5  570.19  236.38
  637.09  235.18  727.87  234.58  753.36  234.64   809.1   236.6  863.03  239.55
   891.8  240.19  921.05  243.93  934.33  246.46  961.89  250.62  971.02  252.83
  992.44  255.34  1033.7  258.34 1098.58  259.93 1132.54   258.8 1239.03  259.28
#Mann= 3 , 0 , 0
       0     .13       0  727.87    .055       0  753.36     .13       0
Bank Sta=727.87,753.36
XS Rating Curve= 0
Exp/Cntr=.3,.1

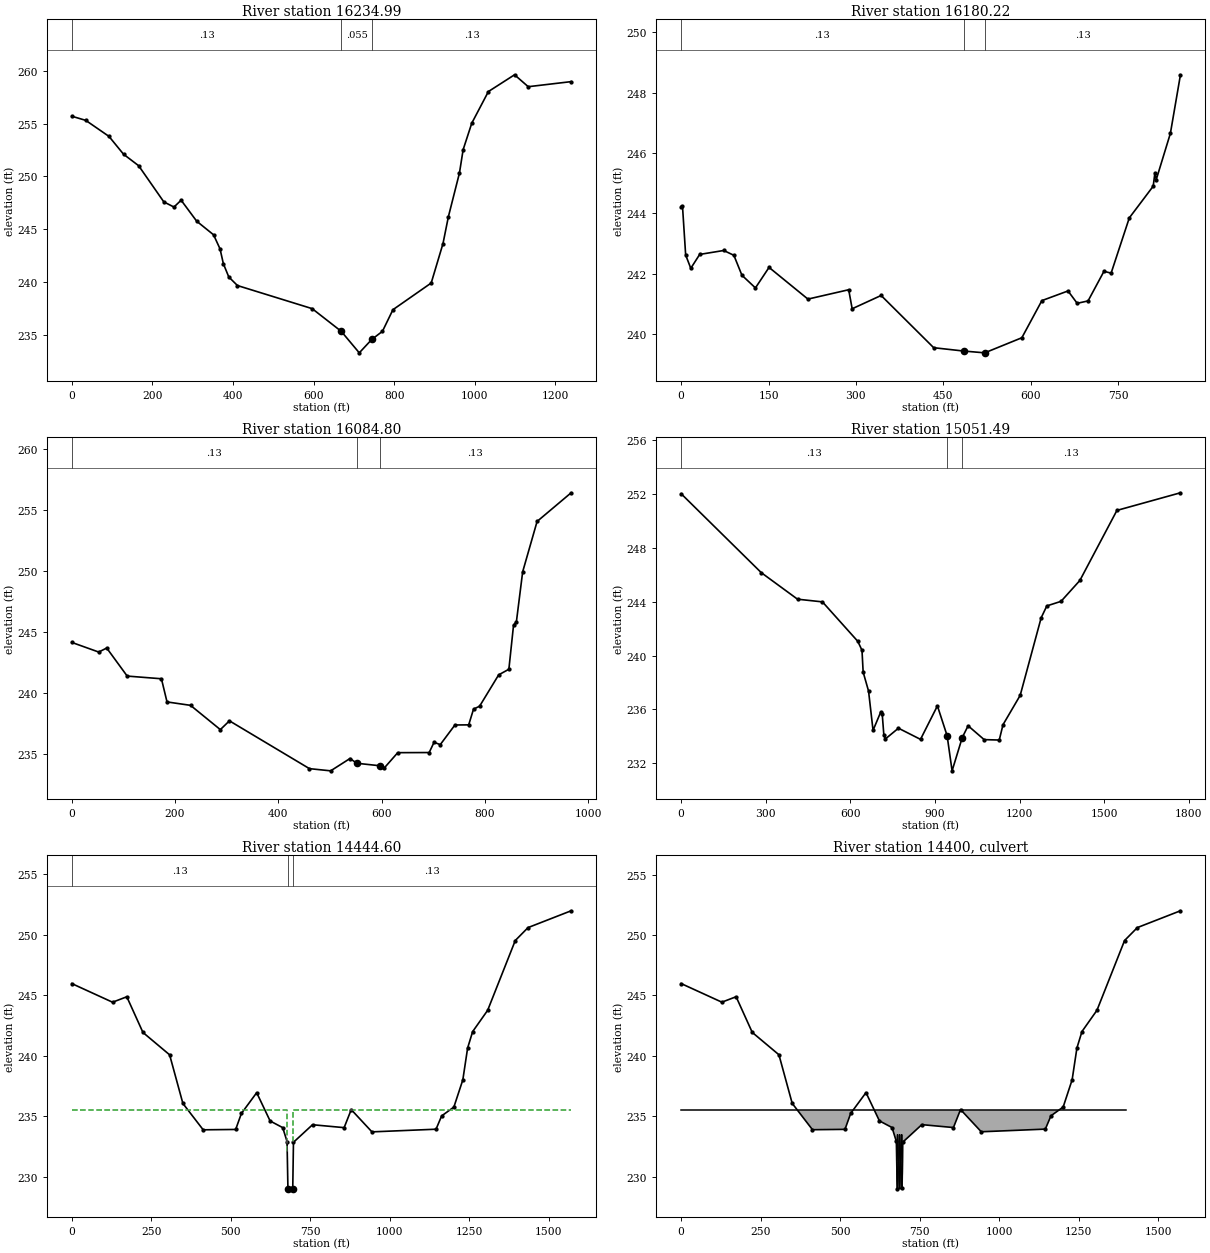
Type RM Length L Ch R = 1 ,16234.99,40.27,54.77,57.73
XS GIS Cut Line= 4
     1924186.664      441213.993     1923819.455      440669.369
     1923443.995      440289.782     1923311.965      440186.634
#Sta/Elev= 30
       0   255.7   34.49  255.31   92.17  253.79  128.31   252.1  165.79  251.01
  228.29  247.58  253.48  247.09  271.23  247.74  309.86  245.75  351.73  244.46
  367.83  243.12  376.04  241.72  389.52  240.46  411.03  239.65  596.37  237.46
  668.54  235.31  713.29  233.27   744.3  234.54  770.78  235.31  796.84  237.36
   891.8  239.89  921.05  243.63  934.33  246.16  961.89  250.32  971.02  252.53
  992.44  255.04  1033.7  258.04 1098.58  259.63 1132.54   258.5 1239.03  258.98
#Mann= 3 , 0 , 0
       0     .13       0  668.54    .055       0   744.3     .13       0
Bank Sta=668.54,744.3
XS Rating Curve= 0
Exp/Cntr=.3,.1

Type RM Length L Ch R = 1 ,16180.22,80.7,95.42,89.13
XS GIS Cut Line= 4
     1924074.217      440898.518     1923943.205       440776.24
     1923682.928      440453.078     1923513.486      440252.193
#Sta/Elev= 30
       0  244.22    2.31  244.25    7.78  242.62   16.57  242.18   31.86  242.64
   73.12  242.77   90.56  242.61  104.34  241.95  127.51  241.53  150.89  242.21
  217.63  241.16  287.58  241.47  293.54  240.84  343.24  241.28  433.45  239.55
  484.64  239.44  521.05  239.38  584.76  239.88  619.16  241.11  664.01  241.43
  679.73  241.02  698.41   241.1  725.68  242.08  737.97  242.02  769.18  243.85
  810.22   244.9  813.12  245.34  815.45  245.12   839.7  246.65  856.96  248.59
#Mann= 3 , 0 , 0
       0     .13       0  484.64    .055       0  521.05     .13       0
Bank Sta=484.64,521.05
XS Rating Curve= 0
Exp/Cntr=.3,.1

Type RM Length L Ch R = 1 ,16084.80,1002.77,1033.31,1052.02
XS GIS Cut Line= 4
     1924166.613      440894.315     1923980.068      440711.657
     1923673.047      440299.704     1923540.911      440159.796
#Sta/Elev= 30
       0  244.17   52.12  243.38    67.6  243.71  107.27  241.41   173.6  241.19
  184.42  239.29     230  239.01  287.71  237.02  305.35  237.74  460.34  233.82
  501.46  233.64  538.89  234.65  552.19  234.26  596.23  234.06  604.78  233.85
  631.37  235.13  692.28  235.14  701.73  235.98  713.77  235.79  742.17   237.4
  768.83  237.41   778.2   238.7  789.96  238.94   826.9  241.51  846.67  241.97
  855.71  245.58   861.3  245.88  873.39  249.96  901.34  254.09   967.3  256.44
#Mann= 3 , 0 , 0
       0     .13       0  552.19    .055       0  596.23     .13       0
Bank Sta=552.19,596.23
XS Rating Curve= 0
Exp/Cntr=.3,.1

Type RM Length L Ch R = 1 ,15051.49,625.62,606.89,558.77
XS GIS Cut Line= 4
     1924966.527      441125.472     1924837.106      440416.738
     1924670.708      439880.565     1924756.988      439399.859
#Sta/Elev= 30
       0  252.04  284.27  246.17  412.65   244.2  501.01     244  626.24  241.07
  641.21   240.4  645.32  238.78  664.48  237.37  680.41  234.45  707.02  235.78
  713.05  235.63  718.76  234.09   724.1  233.81  770.43  234.61  848.66  233.78
  908.61  236.27  943.04  234.05  960.63  231.44  996.59  233.91 1017.39  234.79
 1074.38  233.76 1127.85  233.73 1141.17  234.87 1202.05  237.05 1276.47  242.82
 1296.54   243.7 1346.91  244.04  1413.6  245.59 1545.05   250.8 1770.24  252.11
#Mann= 3 , 0 , 0
       0     .13       0  943.04    .055       0  996.59     .13       0
Bank Sta=943.04,996.59
XS Rating Curve= 0
Exp/Cntr=.5,.3

Type RM Length L Ch R = 1 ,14444.60,140.8,135.48,171.3
XS GIS Cut Line= 4
     1925662.857      440723.316     1925379.154      440120.932
     1925103.223      439588.503      1924850.61      439417.503
#Sta/Elev= 30
       0  245.98  128.12  244.44  172.94  244.89  223.73  241.94  307.63  240.09
  349.37  236.07  413.19  233.89  515.39  233.92  533.33  235.24  581.49  236.96
  623.77  234.62   663.4  234.07  676.97  232.92  679.77  229.01  694.92  229.03
  697.16  232.86  757.06  234.31  856.56  234.07  878.88  235.56  944.03  233.72
  1145.6  233.94 1163.28  235.04 1201.72  235.77 1229.88  238.02 1244.94  240.65
 1260.75  242.01 1307.96  243.77 1394.84  249.54 1435.03  250.61 1570.58     252
#Mann= 3 , 0 , 0
       0     .13       0  679.77    .055       0  694.92     .13       0
#XS Ineff= 2 , 0
       0   677.6   235.5   697.2       0   235.5
Permanent Ineff=
       F       F
Bank Sta=679.77,694.92
XS Rating Curve= 0
Exp/Cntr=.5,.3

Type RM Length L Ch R = 2 ,14400   ,,,
BEGIN DESCRIPTION:
opening size estimated from similar road class
END DESCRIPTION:
Bridge Culvert--1,0,-1,-1, 0
Deck Dist Width WeirC Skew NumUp NumDn MinLoCord MaxHiCord MaxSubmerge Is_Ogee
55,20,2.6,0, 2, 2, , , .95, 0, 0,0,,
       0    1400
   235.5   235.5
                
       0    1400
   235.5   235.5
                
Multiple Barrel Culv=1,4.5,,20,.028,.5,1,1,1,229,228.5, 3,Culvert #1  , 0 ,55
   680.8   494.8   687.3   501.3   693.8   507.8
Culvert Bottom n=.028
BC Design=,, 0 ,, 0 ,,,,,,

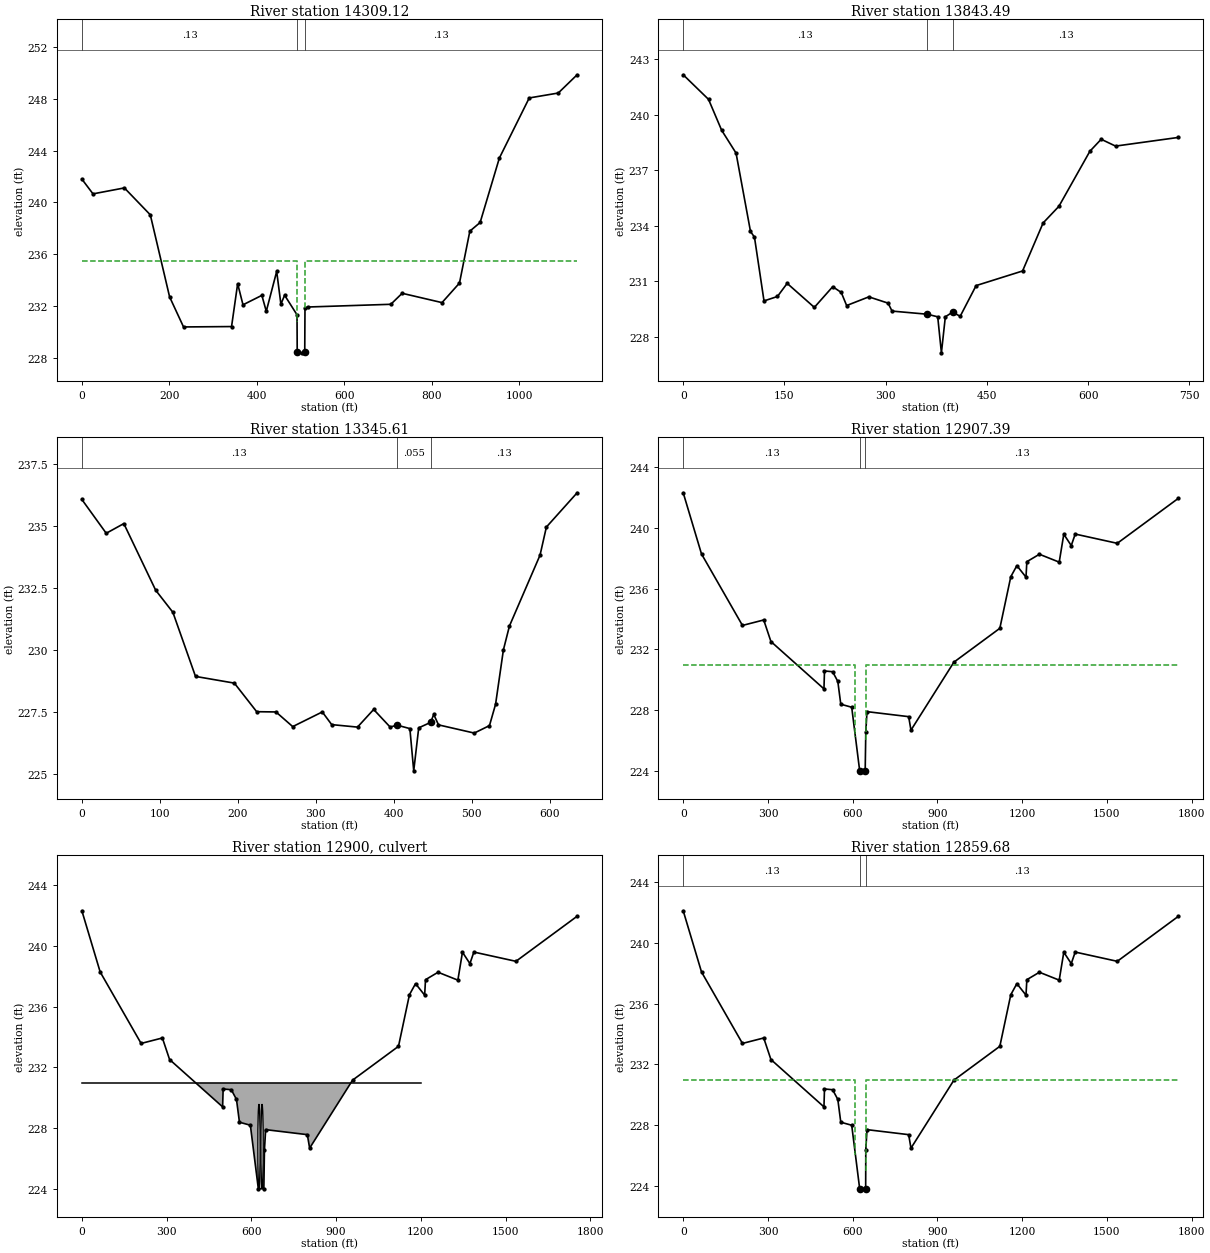
Type RM Length L Ch R = 1 ,14309.12,375.02,465.63,567.88
XS GIS Cut Line= 4
     1925709.493      440540.658     1925608.448      440334.681
     1925359.722      439751.729     1925460.767      439503.003
#Sta/Elev= 30
       0   241.8   25.45  240.66   97.16  241.12  156.39  239.04  200.49   232.7
  232.31  230.38  342.05  230.41  355.98  233.72  368.19  232.09  411.27  232.82
  421.39  231.59  445.17  234.67  454.79  232.14  463.28  232.83  491.61  231.32
  492.07  228.46  503.93  228.38  509.28  228.46  509.84  231.81  515.87  231.92
  705.96  232.13  731.87  232.98  822.93  232.26  862.86  233.77  886.54  237.78
  910.06  238.45  954.03  243.43 1022.25  248.07 1088.55  248.45 1131.69  249.86
#Mann= 3 , 0 , 0
       0     .13       0  492.07    .055       0  509.28     .13       0
#XS Ineff= 2 , 0
       0   491.7   235.5   510.9       0   235.5
Permanent Ineff=
       F       F
Bank Sta=492.07,509.28
XS Rating Curve= 0
Exp/Cntr=.5,.3

Type RM Length L Ch R = 1 ,13843.49,461.84,497.88,483.99
XS GIS Cut Line= 3
     1925837.039      440537.339     1926002.077      439951.455
     1925964.943      439831.803
#Sta/Elev= 30
       0  242.17   37.52  240.84   56.93  239.17   78.33  237.93   99.72  233.69
  105.62  233.38  119.74  229.93  139.65  230.17  154.05  230.88  194.35  229.58
  221.56   230.7   234.2  230.39  242.19  229.68  275.12  230.15  303.62  229.81
  309.49  229.38  361.74  229.21  377.18  229.07  382.65  227.12  388.46  229.07
  399.11  229.32   410.5   229.1  434.09  230.76  502.92  231.55  533.38  234.15
  556.76  235.05  602.68  238.03  619.42  238.68  640.73  238.31  733.97  238.78
#Mann= 3 , 0 , 0
       0     .13       0  361.74    .055       0  399.11     .13       0
Bank Sta=361.74,399.11
XS Rating Curve= 0
Exp/Cntr=.3,.1

Type RM Length L Ch R = 1 ,13345.61,602.07,438.22,345.25
XS GIS Cut Line= 4
      1926244.11      440687.199     1926294.068      440564.801
     1926426.458      440187.614     1926441.446      440085.199
#Sta/Elev= 30
       0  236.06   31.26   234.7   53.83  235.09   94.68  232.41  116.78  231.52
   145.8  228.94  195.66  228.67  224.29  227.52  249.03  227.51  270.54  226.92
  308.46  227.51  320.56     227  353.66   226.9  374.39  227.61  395.57   226.9
  404.26  226.98  420.85  226.84  425.79  225.14  432.19  226.87  447.46  227.09
   451.5  227.41  457.57  226.99  503.46  226.66  522.98  226.96  530.81  227.82
  540.87  230.01  548.62  230.97  587.86  233.82  595.99  234.95  635.45  236.33
#Mann= 3 , 0 , 0
       0     .13       0  404.26    .055       0  447.46     .13       0
Bank Sta=404.26,447.46
XS Rating Curve= 0
Exp/Cntr=.5,.3

Type RM Length L Ch R = 1 ,12907.39,52.79,47.71,45.04
XS GIS Cut Line= 6
     1927502.548      440521.205     1927070.792      440227.611
     1926917.827       440158.53      1926609.43      440096.851
     1925814.999      439731.709 1925272.7623883    439482.48237
#Sta/Elev= 30
       0  242.32   64.76  238.29  209.76  233.58  285.06  233.94  310.56  232.52
  498.32   229.4  500.19  230.58  529.02  230.53  547.39  229.89  557.89  228.39
  596.58  228.19  624.82     224  644.29  224.01  646.43  226.57  650.71   227.9
  798.24  227.57  806.37  226.68  958.38  231.16 1120.99  233.39 1159.81  236.79
 1181.36  237.52 1213.62  236.76 1216.67  237.78  1261.1  238.27 1331.24  237.75
 1347.45  239.59 1373.89  238.84 1387.87   239.6  1536.8  238.99 1753.47  241.96
#Mann= 3 , 0 , 0
       0     .13       0  624.82    .055       0  644.29     .13       0
#XS Ineff= 2 , 0
       0   609.8     231     646       0     231
Permanent Ineff=
       F       F
Bank Sta=624.82,644.29
XS Rating Curve= 0
Exp/Cntr=.5,.3

Type RM Length L Ch R = 2 ,12900   ,,,
BEGIN DESCRIPTION:
SR 1143; NCDOT small pipes 46 2003
END DESCRIPTION:
Bridge Culvert--1,0,-1,-1, 0
Deck Dist Width WeirC Skew NumUp NumDn MinLoCord MaxHiCord MaxSubmerge Is_Ogee
16,18.8,2.6,0, 2, 2, , , .95, 0, 0,0,,
       0    1200
     231     231
                
       0    1200
     231     231
                
Multiple Barrel Culv=3,5.58,7.91,18.8,.03,.5,1,34,1,224,223.8, 2,Culvert #1  , 0 ,16
     627     627     638     638
Culvert Bottom n=.03
BC Design=,, 0 ,, 0 ,,,,,,

Type RM Length L Ch R = 1 ,12859.68,920.91,937.6,918.78
XS GIS Cut Line= 5
     1927468.007      440392.912     1926999.244      440114.121
     1926710.584      440072.179     1925876.679      439692.234
 1925400.5229342  439475.2870859
#Sta/Elev= 30
       0  242.12   64.76  238.09  209.76  233.38  285.06  233.74  310.56  232.32
  498.32   229.2  500.19  230.38  529.02  230.33  547.39  229.69  557.89  228.19
  596.58  227.99  624.82   223.8  645.99   223.8  646.43  226.37  650.71   227.7
  798.24  227.37  806.37  226.48  958.38  230.96 1120.99  233.19 1159.81  236.59
 1181.36  237.32 1213.62  236.56 1216.67  237.58  1261.1  238.07 1331.24  237.55
 1347.45  239.39 1373.89  238.64 1387.87   239.4  1536.8  238.79 1753.47  241.76
#Mann= 3 , 0 , 0
       0     .13       0  624.82    .055       0  645.99     .13       0
#XS Ineff= 2 , 0
       0  609.78     231  646.19       0     231
Permanent Ineff=
       F       F
Bank Sta=624.82,645.99
XS Rating Curve= 0
Exp/Cntr=.5,.3

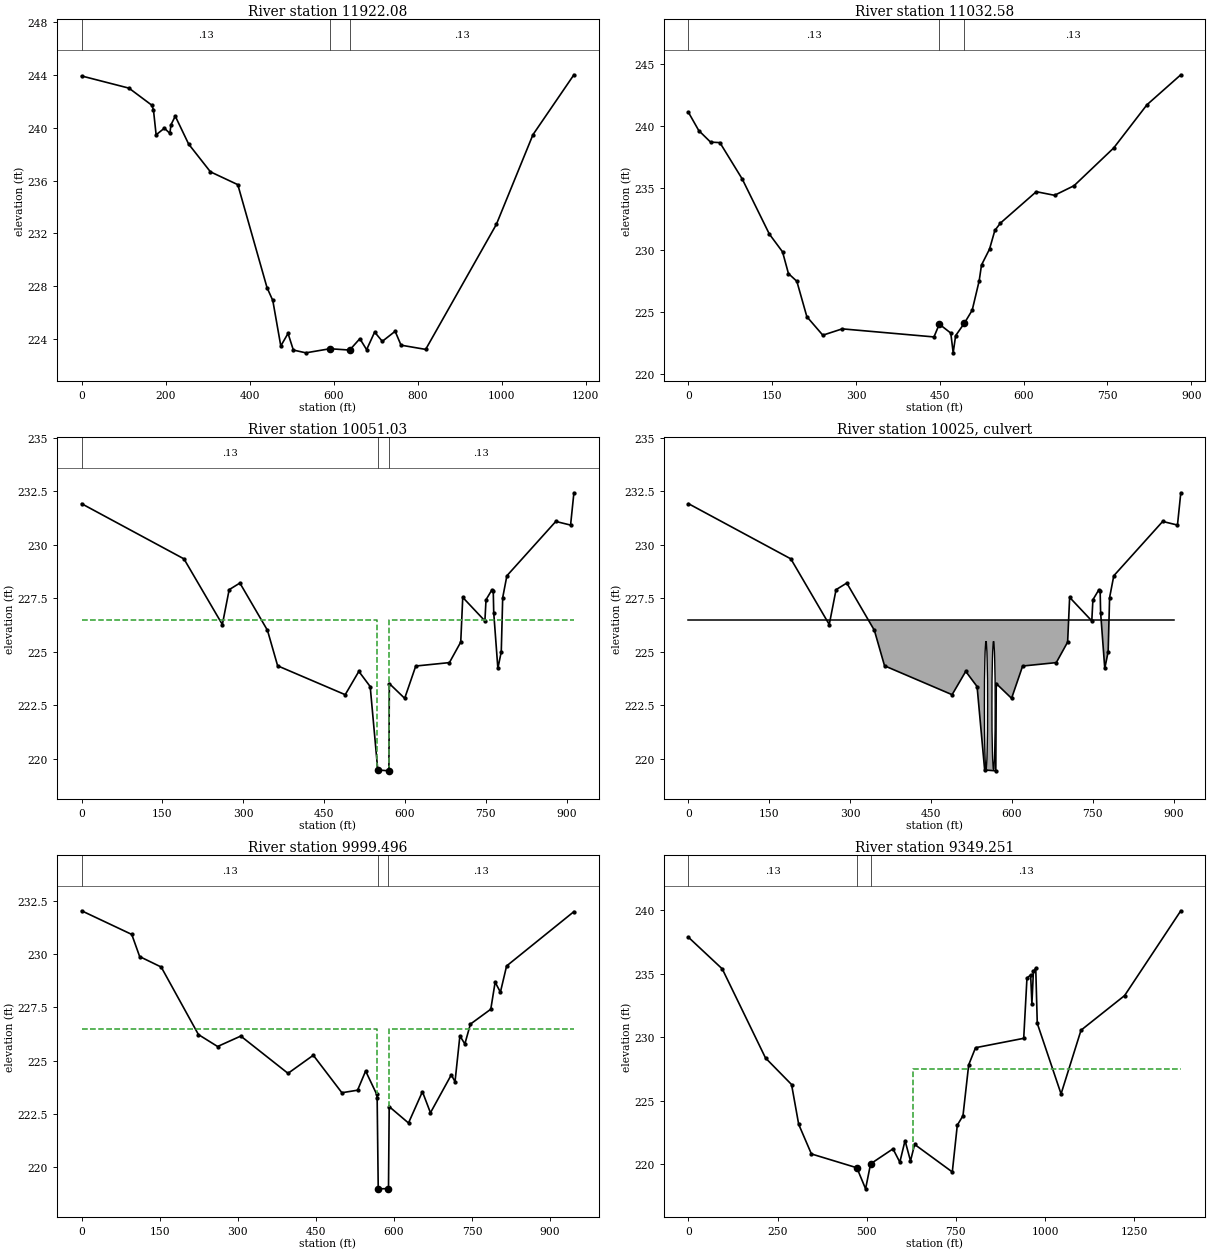
Type RM Length L Ch R = 1 ,11922.08,824.22,889.5,959.82
XS GIS Cut Line= 4
     1927546.123      439401.474     1927195.563      439221.977
     1926602.862      439125.603     1926467.938      439009.954
#Sta/Elev= 30
       0  243.91  112.75  242.99  167.09   241.7  171.05  241.35  177.43  239.46
  197.05  239.96  210.11  239.57  212.94  240.23  223.01  240.87  254.83  238.76
  306.72  236.66  371.87  235.69  441.45   227.9  455.18  226.93  474.23  223.49
  491.48  224.44  504.11  223.18  533.97  222.97  591.05  223.28  638.18  223.18
  662.43  224.04  678.53  223.21  697.63  224.54  715.92  223.84  746.46   224.6
  760.47  223.55  819.11  223.23  987.49  232.69 1074.56  239.47 1172.03     244
#Mann= 3 , 0 , 0
       0     .13       0  591.05    .055       0  638.18     .13       0
Bank Sta=591.05,638.18
XS Rating Curve= 0
Exp/Cntr=.3,.1

Type RM Length L Ch R = 1 ,11032.58,973.72,981.56,950.63
XS GIS Cut Line= 4
     1927730.439      438807.568     1927585.878      438638.914
     1927393.129      438407.616     1927128.101      438166.681
#Sta/Elev= 30
       0  241.08   18.41  239.62   39.53  238.69   56.21  238.65   96.24  235.72
  144.76  231.29  168.36  229.86  178.96  228.11  193.98  227.49  211.91  224.64
  240.49  223.15  275.27  223.66  439.49  223.01  449.05  224.04  469.59  223.32
  473.89  221.73  478.24  223.11  493.96  224.12  507.91  225.16   520.4  227.52
  524.59   228.8  538.97  230.08  548.46  231.58  558.41  232.17  622.65   234.7
   655.3  234.41  690.23  235.18  761.28  238.22  820.87   241.7  881.39  244.11
#Mann= 3 , 0 , 0
       0     .13       0  449.05    .055       0  493.96     .13       0
Bank Sta=449.05,493.96
XS Rating Curve= 0
Exp/Cntr=.5,.3

Type RM Length L Ch R = 1 ,10051.03,65.37,51.53,53.3
XS GIS Cut Line= 5
     1928515.333       438121.33     1928238.521      437920.641
     1928162.397      437837.598     1928013.611      437692.271
     1927863.094      437491.583
#Sta/Elev= 30
       0  231.93  189.92  229.35  261.16  226.28  273.79  227.91  293.69  228.22
  344.86  226.01  363.74  224.35  489.08     223  514.39  224.09  535.45  223.38
   549.5  219.48  570.16  219.44  570.98  223.52  599.43  222.83  619.98  224.34
  682.41   224.5  703.45  225.46  707.17  227.55  748.27  226.45  750.35  227.44
  760.78  227.88  763.76  227.87  764.65  226.83  772.34  224.23  778.64  225.01
   781.3  227.54  789.08  228.56  879.81   231.1  907.23  230.93  913.41  232.44
#Mann= 3 , 0 , 0
       0     .13       0   549.5    .055       0  570.16     .13       0
#XS Ineff= 2 , 0
       0  548.95   226.5  570.16       0   226.5
Permanent Ineff=
       F       F
Bank Sta=549.5,570.16
XS Rating Curve= 0
Exp/Cntr=.5,.3

Type RM Length L Ch R = 2 ,10025   ,,,
BEGIN DESCRIPTION:
SR 1116; NCDOT small pipes data 46 2029
END DESCRIPTION:
Bridge Culvert--1,0,-1,-1, 0
Deck Dist Width WeirC Skew NumUp NumDn MinLoCord MaxHiCord MaxSubmerge Is_Ogee
19,21,2.6,0, 2, 2, , , .95, 0, 0,0,,
       0     900
   226.5   226.5
                
       0     900
   226.5   226.5
                
Multiple Barrel Culv=1,6,,21,.028,.5,1,1,1,219.5,219, 2,Culvert #1  , 0 ,19
     552     573     566     587
Culvert Bottom n=.028
BC Design=,, 0 ,, 0 ,,,,,,

Type RM Length L Ch R = 1 ,9999.496,627.4,650.25,602.72
XS GIS Cut Line= 4
     1928563.775      438107.489     1928181.428      437801.266
     1928065.513       437652.48     1927899.426       437443.14
#Sta/Elev= 30
       0  232.03   96.38  230.92  111.55  229.88  152.91  229.39  224.45  226.22
  261.23  225.66  305.78  226.15  396.52   224.4  445.08  225.25     500  223.49
  530.15  223.61   545.6  224.51     567223.4102  567.73  223.24  569.83  218.98
  589.53  218.99  590.87  222.84  627.97  222.07  654.72  223.54  670.14  222.55
  710.17  224.33  717.33  224.01  726.67  226.16  736.23  225.78  746.82  226.71
  786.02  227.41  794.37  228.68   804.5  228.21   816.4  229.44  945.69  231.99
#Mann= 3 , 0 , 0
       0     .13       0  569.83    .055       0  589.53     .13       0
#XS Ineff= 2 , 0
       0     567   226.5     591       0   226.5
Permanent Ineff=
       F       F
Bank Sta=569.83,589.53
XS Rating Curve= 0
Exp/Cntr=.5,.3

Type RM Length L Ch R = 1 ,9349.251,579.04,544.28,490.12
XS GIS Cut Line= 5
     1929104.509      437773.495      1928851.08      437583.424
     1928497.335      437293.036     1928228.067      437108.244
     1928001.037      436944.571
#Sta/Elev= 30
       0  237.86   94.74  235.37  216.09  228.35  289.09  226.26  309.15  223.12
  344.76  220.79  472.27   219.7  496.76  218.04  510.81  220.01   573.6  221.19
  592.81  220.14   607.4  221.84  622.72  220.24  634.34  221.54  739.97  219.37
  754.02  223.06  769.95   223.8  785.95  227.81  805.14  229.16  940.28   229.9
   949.4  234.64  959.72   234.9  963.27  232.61   967.5  235.19  974.05  235.42
  978.31  231.08 1045.06  225.52 1101.03  230.54 1223.32  233.27 1380.91  239.95
#Mann= 3 , 0 , 0
       0     .13       0  472.27    .055       0  510.81     .13       0
#XS Ineff= 2 , 0
                          630.33          227.51
Permanent Ineff=
       F       F
Bank Sta=472.27,510.81
XS Rating Curve= 0
Exp/Cntr=.3,.1

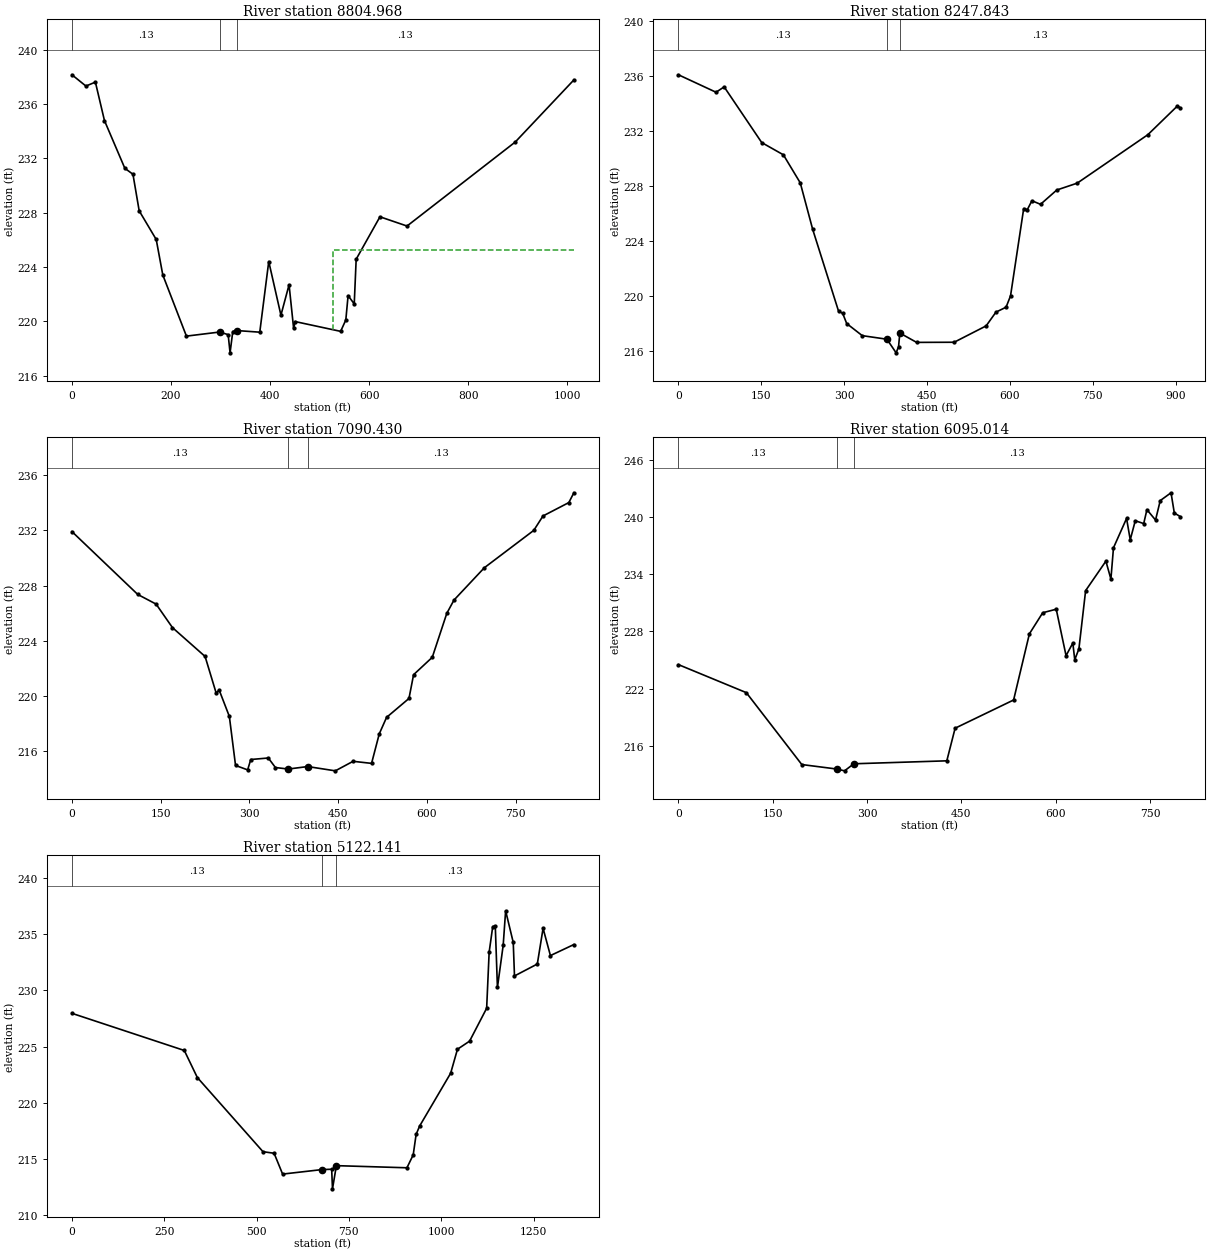
Type RM Length L Ch R = 1 ,8804.968,565.33,557.12,520.61
XS GIS Cut Line= 3
     1929179.049      437026.165     1928828.345       436960.15
     1928201.202      436766.231
#Sta/Elev= 30
       0  238.14   28.22  237.31   47.33   237.6   65.63  234.77  106.77  231.26
  123.16  230.82  135.74  228.13  170.14  226.02  183.41  223.41  231.12  218.91
  297.95  219.21  315.38  219.02  319.23  217.68  324.69  219.25  332.69  219.32
  379.19   219.2  397.32   224.4  421.91  220.45  438.34  222.69  447.55  219.48
  450.72  219.98  542.46  219.26  552.92   220.1   557.5  221.89  569.92  221.28
  573.82  224.57  621.84  227.69  676.49  227.01  894.91  233.19  1013.3  237.76
#Mann= 3 , 0 , 0
       0     .13       0  297.95    .055       0  332.69     .13       0
#XS Ineff= 2 , 0
                          526.07          225.28
Permanent Ineff=
       F       F
Bank Sta=297.95,332.69
XS Rating Curve= 0
Exp/Cntr=.3,.1

Type RM Length L Ch R = 1 ,8247.843,1128.43,1157.41,1200.15
XS GIS Cut Line= 3
     1929231.223      436421.874     1928328.383      436406.035
     1928328.383      436400.755
#Sta/Elev= 30
       0  236.08   68.09  234.81   82.78   235.2  150.76  231.15  189.95  230.26
   220.5  228.22  242.97  224.84  289.72   218.9  297.27  218.73  304.53  217.99
  332.72  217.11  377.31  216.85  393.99  215.86  398.37  216.31  400.66   217.3
  431.06  216.62  498.96  216.63  556.85  217.82  574.62  218.82  592.95  219.18
  600.99     220  624.82  226.35  631.33  226.27   639.7  226.92  655.28  226.66
   684.7   227.7   721.7   228.2  849.44  231.72  902.98  233.81  908.26  233.68
#Mann= 3 , 0 , 0
       0     .13       0  377.31    .055       0  400.66     .13       0
Bank Sta=377.31,400.66
XS Rating Curve= 0
Exp/Cntr=.3,.1

Type RM Length L Ch R = 1 ,7090.430,999.76,995.42,991.75
XS GIS Cut Line= 4
     1929463.533      435561.271     1929268.182       435365.92
     1928977.794      435265.604     1928734.925      435160.009
#Sta/Elev= 30
       0  231.91   111.2  227.36  142.26  226.66  169.87  224.96  225.04  222.87
  243.89   220.2  248.74  220.45  266.04  218.53  276.51  214.98  296.97  214.66
  302.24  215.41  331.87  215.52  343.93  214.83  365.54  214.72  398.48   214.9
  445.14  214.59  475.22  215.28  506.42  215.13  519.45  217.27  531.78  218.46
  569.65  219.83  577.43  221.55  609.04  222.81  633.56  225.99  645.68  226.95
  696.97  229.29  780.63     232  796.16  233.04  839.83  234.01  848.33  234.72
#Mann= 3 , 0 , 0
       0     .13       0  365.54    .055       0  398.48     .13       0
Bank Sta=365.54,398.48
XS Rating Curve= 0
Exp/Cntr=.3,.1

Type RM Length L Ch R = 1 ,6095.014,889.01,972.87,1066.68
XS GIS Cut Line= 3
     1929745.084      434472.044     1929577.441      434424.986
     1928986.278      434224.991
#Sta/Elev= 30
       0  224.51     108  221.57  196.22  214.03  251.74  213.56  264.19  213.37
  278.94  214.11  426.84  214.42  440.04  217.84  533.07   220.8  558.18  227.74
  579.37  229.95  600.87  230.32  616.48  225.45  627.25  226.77   630.3  225.02
  636.92  226.16   647.6  232.27  679.84  235.36  687.79  233.48   691.9  236.76
  712.72  239.84  718.56   237.6  726.56   239.6  739.98   239.3  745.09  240.76
  758.78  239.67  766.27  241.71  783.41  242.53  788.66  240.41   798.2  240.03
#Mann= 3 , 0 , 0
       0     .13       0  251.74    .055       0  278.94     .13       0
Bank Sta=251.74,278.94
XS Rating Curve= 0
Exp/Cntr=.3,.1

Type RM Length L Ch R = 1 ,5122.141,0,0,0
BEGIN DESCRIPTION:
CP TONUP
END DESCRIPTION:
XS GIS Cut Line= 4
     1929949.272      434146.293     1929848.957      433644.714
     1929606.087      433222.333      1929299.86      433032.261
#Sta/Elev= 30
       0  227.95  304.29  224.65  339.48  222.25  517.32  215.66  547.43  215.52
  570.48  213.67  677.03  214.07  703.32   214.1  705.56  212.36  716.05  214.42
  907.16  214.23  924.16  215.38  932.03   217.2  941.54  217.94 1025.53  222.63
 1043.97  224.76  1076.8  225.48 1123.01   228.4 1129.77  233.38 1139.49  235.66
 1146.44  235.67  1152.2  230.25 1167.78  233.99  1174.4  237.06 1195.02  234.25
 1198.39  231.27 1260.21  232.33 1275.81   235.5  1295.7  233.08 1359.16  234.06
#Mann= 3 , 0 , 0
       0     .13       0  677.03    .055       0  716.05     .13       0
Bank Sta=677.03,716.05
XS Rating Curve= 0
Exp/Cntr=.3,.1

River Reach=Toneys          ,Lower
Reach XY= 30
      1930081.74      433326.812     1930141.442      433167.257
     1930127.737      433055.567     1930138.015      433032.955
     1930103.069      432955.525     1929998.916      432826.019
     1929911.209      432650.603     1929919.431      432390.906
     1929910.523      432336.088     1929949.581      432170.951
     1929927.654      432033.908     1929937.247      431980.461
     1929990.694       431898.92     1930032.492      431798.878
     1930079.772      431750.228     1930181.184      431705.003
     1930270.948      431637.167       1930435.4      431445.306
     1930457.327      431391.174     1930440.882       431222.61
     1930477.883      431045.139     1930492.273      430824.499
     1930438.826      430662.788     1930402.509      430460.648
     1930318.913      429811.747     1930228.464      429533.549
     1930208.593      429405.414     1930212.704      429231.368
     1930195.574      429053.212      1930208.59      428992.227

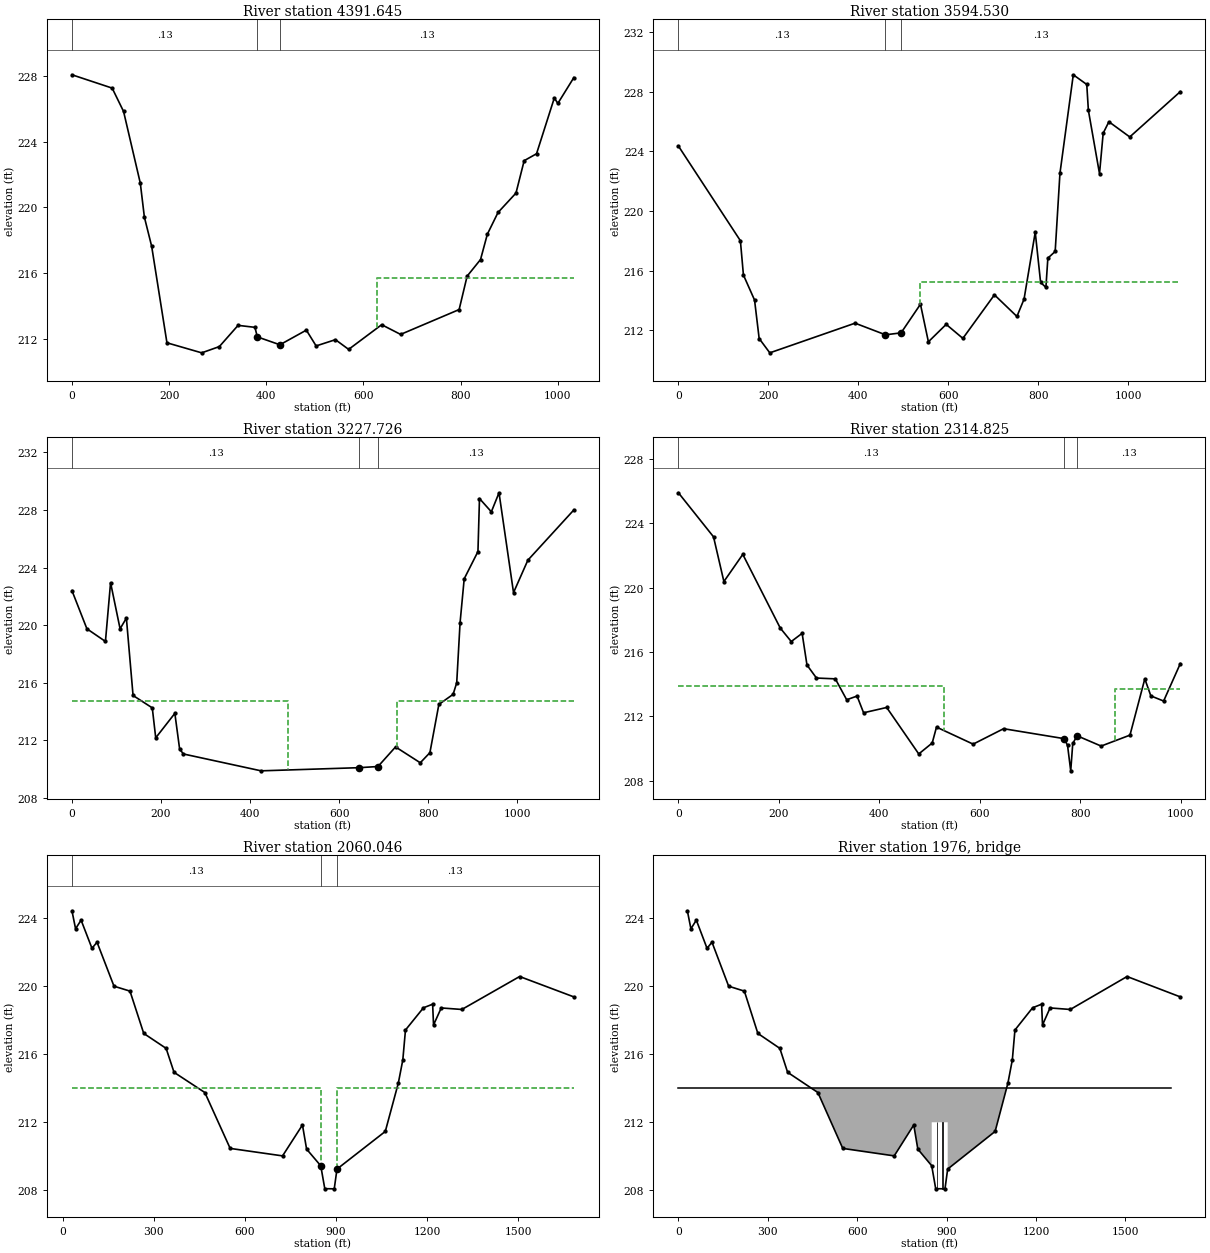
Type RM Length L Ch R = 1 ,4391.645,752.06,797.11,792.3
XS GIS Cut Line= 4
     1930504.867      433139.425      1930315.33      433081.989
     1929735.231      432949.888     1929499.745      432995.836
#Sta/Elev= 30
       0  228.06   82.76  227.25  106.25  225.83   140.7  221.47  149.06  219.41
  164.09  217.63   195.5  211.77  267.01  211.16  303.33  211.54   341.9  212.83
  376.61  212.71  381.48  212.13  427.97  211.65  482.41  212.54   502.5  211.58
  542.28  211.96  569.45  211.37  637.43  212.87  676.41  212.28  796.83  213.79
  813.26  215.82  840.87  216.83   854.9  218.37  876.86  219.69  913.82  220.87
  930.68  222.84  956.12  223.26  992.71  226.65  999.98  226.32 1032.93  227.89
#Mann= 3 , 0 , 0
       0     .13       0  381.48    .055       0  427.97     .13       0
#XS Ineff= 2 , 0
                          627.63           215.7
Permanent Ineff=
       F       F
Bank Sta=381.48,427.97
XS Rating Curve= 0
Exp/Cntr=.3,.1

Type RM Length L Ch R = 1 ,3594.530,343.16,366.8,360.51
XS GIS Cut Line= 4
     1930338.304      432524.865     1930194.715      432444.455
     1929700.769      432214.713     1929333.182      432042.406
#Sta/Elev= 30
       0  224.36  137.71  218.01  144.46  215.71  169.19  214.03  179.42  211.45
  203.08  210.49  392.57  212.48  460.15   211.7  494.76  211.83  537.86  213.75
  555.48  211.23  595.02   212.4  632.08  211.46  702.22  214.38  752.21  212.93
  768.03  214.09  792.91  218.58  804.85  215.21  816.63  214.88  820.94  216.84
  837.22  217.29  847.81  222.53  877.45  229.14  907.41  228.49  910.98  226.76
  935.71  222.51  943.88  225.22  956.58  225.99 1002.95  224.97  1115.3  228.01
#Mann= 3 , 0 , 0
       0     .13       0  460.15    .055       0  494.76     .13       0
#XS Ineff= 2 , 0
                          536.84          215.23
Permanent Ineff=
       F       F
Bank Sta=460.15,494.76
XS Rating Curve= 0
Exp/Cntr=.3,.1

Type RM Length L Ch R = 1 ,3227.726,885.96,912.9,860.38
XS GIS Cut Line= 4
     1930486.243      432336.801     1930327.423      432166.217
     1929642.145      431789.755     1929536.265      431754.462
#Sta/Elev= 30
       0   222.4   33.55  219.75   75.17  218.87   86.68  222.95  108.03  219.75
  122.19  220.49  137.16  215.12   180.3  214.26  188.04  212.18  230.96  213.88
   241.7   211.4  250.28  211.06  424.55  209.89  645.07  210.11  686.93  210.19
  726.35  211.55  781.84  210.45  803.46  211.15  823.57   214.5  855.54   215.2
  863.64     216  871.18  220.18  880.44  223.22  911.29  225.11  914.74  228.79
  941.37  227.87  958.59  229.19  991.14  222.26  1023.3  224.51 1126.56     228
#Mann= 3 , 0 , 0
       0     .13       0  645.07    .055       0  686.93     .13       0
#XS Ineff= 2 , 0
          485.53  214.73  730.26          214.73
Permanent Ineff=
       F       F
Bank Sta=645.07,686.93
XS Rating Curve= 0
Exp/Cntr=.3,.1

Type RM Length L Ch R = 1 ,2314.825,355.66,254.78,193.58
XS GIS Cut Line= 3
     1931201.505      431408.344     1930827.483      431431.012
     1930255.115      431181.663
#Sta/Elev= 30
       0  225.91   69.89  223.17   90.52  220.39  128.15  222.08  202.67   217.5
  224.59  216.66  246.25  217.17  255.89   215.2   274.8  214.39  312.35  214.34
  334.93  213.04  355.59  213.27  368.58  212.23  414.56  212.56   478.4  209.67
  505.16  210.35  513.72  211.34  586.65  210.28  647.23  211.24  768.12  210.62
  774.56   210.2  780.88  208.62  784.93  210.32  793.64   210.8  841.45  210.16
   898.8  210.84  928.35  214.34  940.38  213.28  965.78  212.96  999.03  215.29
#Mann= 3 , 0 , 0
       0     .13       0  768.12    .055       0  793.64     .13       0
#XS Ineff= 2 , 0
          529.61  213.92  868.42          213.68
Permanent Ineff=
       F       F
Bank Sta=768.12,793.64
XS Rating Curve= 0
Exp/Cntr=.5,.3

Type RM Length L Ch R = 1 ,2060.046,103.78,140.76,168.65
XS GIS Cut Line= 5
     1931314.708      430951.131     1930826.506      430945.387
     1930556.559      430974.105     1930280.868       431111.95
     1929838.615      431496.768
#Sta/Elev= 30
      30  224.45   41.95  223.39   60.12   223.9   96.02  222.24  112.66   222.6
  168.55  220.01  221.27  219.72  266.58  217.23  340.36  216.35  366.44  214.94
  468.01  213.75  551.44  210.46  724.13  210.02  789.71  211.84  803.34  210.42
     850209.4374   863.3  208.09  894.49  208.08  903.51209.2434 1062.74  211.46
 1105.58   214.3 1120.46  215.67 1129.21  217.43 1188.52  218.74 1218.72  218.95
 1221.72  217.73  1247.1  218.73 1315.02  218.64 1505.49  220.58 1684.17  219.38
#Mann= 3 , 0 , 0
      30     .13       0     850    .055       0  903.51     .13       0
#XS Ineff= 2 , 0
       0     850     214  903.51       0     214
Permanent Ineff=
       F       F
Bank Sta=850,903.51
XS Rating Curve= 0
Exp/Cntr=.5,.3

Type RM Length L Ch R = 3 ,1976    ,,,
BEGIN DESCRIPTION:
SR1138; NCDOT structure 26
END DESCRIPTION:
Bridge Culvert--1,0,-1,-1, 0
Deck Dist Width WeirC Skew NumUp NumDn MinLoCord MaxHiCord MaxSubmerge Is_Ogee
42.6,25.4,2.6,0, 8, 8, , , .95, 0, 1.5,1.5,,
       0    2.47  817.16     850  903.51 1637.28 1647.02 1654.17
     214     214     214     214     214     214     214     214
                             212     212
       0    2.47  817.16     850  903.51 1637.28 1647.02 1654.17
     214     214     214     214     214     214     214     214
                             212     212
Pier Skew, UpSta & Num, DnSta & Num=  ,867.92, 2 ,867.92, 2 , 0 , 0 , 0 ,,
       2       2
     200     218
       2       2
     200     218
Pier Skew, UpSta & Num, DnSta & Num=  ,886.59, 2 ,886.59, 2 , 0 , 0 , 0 ,,
       2       2
     200     218
       2       2
     200     218
BR Coef=-1 , 1 , 0 ,, 0 ,,,.8,0,1.2,1,
WSPro=,,,, 1 ,,,, 0 ,,,, 0 ,,,,-1 ,-1 ,-1 , 0 , 0 , 0 , 0 , 0
BC Design=,, 0 ,, 0 ,,,,,,