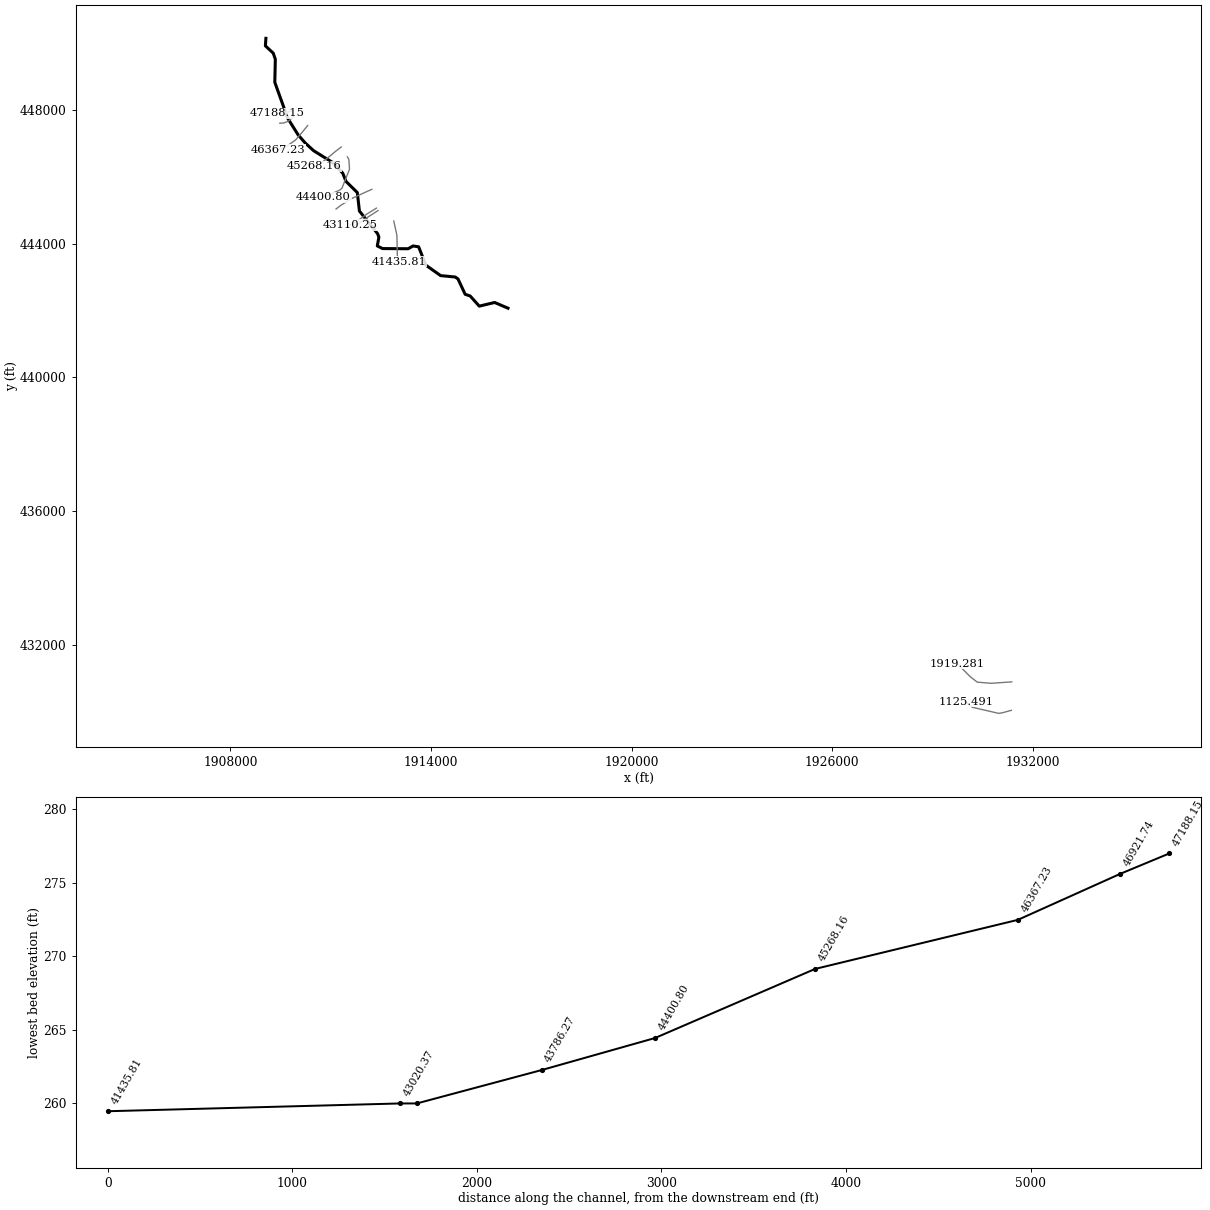
HEC-RAS study upraft.prj: Upper Raft Swamp

--- upraft.g04 (geometry) --- (continued)

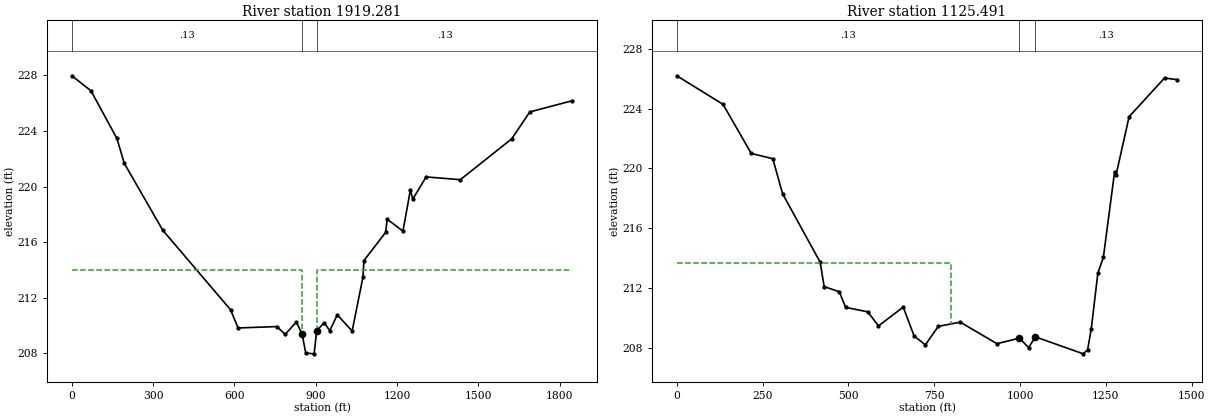
Type RM Length L Ch R = 1 ,1919.281,812.61,793.79,784.5
XS GIS Cut Line= 5
     1931368.284      430895.665     1930756.321      430852.175
     1930336.955      430886.346     1930135.039      431041.666
     1929740.525       431436.18
#Sta/Elev= 30
       0  227.96   70.47  226.88  166.03  223.46  193.53  221.66  335.23  216.86
  585.49  211.14  613.32  209.83   756.6  209.93  787.22  209.37  828.37  210.26
     850209.3621  862.86  208.03  893.86  207.97  903.51 209.639  931.17   210.2
  951.62  209.64  979.49  210.77 1034.26  209.61  1073.8  213.46 1077.94  214.68
 1157.75   216.7 1163.58  217.65  1221.7  216.79 1249.24  219.76 1258.06  219.09
 1307.15  220.69 1433.33  220.49 1622.82  223.42 1689.77  225.36 1846.93  226.17
#Mann= 3 , 0 , 0
       0     .13       0     850    .055       0  903.51     .13       0
#XS Ineff= 2 , 0
       0     850     214  903.51       0     214
Permanent Ineff=
       F       F
Bank Sta=850,903.51
XS Rating Curve= 0
Exp/Cntr=.5,.3

Type RM Length L Ch R = 1 ,1125.491,0,0,0
XS GIS Cut Line= 5
     1931357.053      430043.938     1931076.445      429968.098
     1930977.853       429952.93     1930189.116      430134.946
     1929991.932      430301.794
#Sta/Elev= 30
       0   226.2  134.65  224.29  217.07     221  279.63  220.65  308.33   218.3
  417.77  213.72  429.31  212.09  473.35  211.75  491.83   210.7  556.49   210.4
  587.55  209.46  659.71  210.72  691.32  208.79  724.08  208.19  761.96  209.43
   825.9  209.71  932.79  208.27   998.3  208.64 1025.36     208  1044.3  208.73
 1184.29  207.59 1196.99  207.87 1207.57  209.27 1226.76  212.99 1242.81  214.05
 1275.64  219.79 1279.84  219.57  1317.8  223.46 1420.97  226.05  1458.2  225.94
#Mann= 3 , 0 , 0
       0     .13       0   998.3    .055       0  1044.3     .13       0
#XS Ineff= 2 , 0
             800  213.64
Permanent Ineff=
       F       F
Bank Sta=998.3,1044.3
XS Rating Curve= 0
Exp/Cntr=.3,.1

River Reach=Raft Swamp      ,one
Reach XY= 30
      1909060.92       450141.94      1909045.27       449917.57
      1909280.08       449698.42      1909342.69       449515.79
      1909327.04       448827.03      1909713.16       447752.14
      1910023.63       447256.44      1910237.56        447011.2
      1910488.02       446781.61      1911067.21       446421.57
      1911359.41        446108.5      1911455.94       445863.26
      1911795.11       445529.31      1911857.72       444976.21
      1912402.99       444297.89      1912439.52       444193.53
      1912392.56       443932.63      1912549.09       443854.36
      1913316.13       443849.15      1913462.23       443932.63
       1913629.2       443906.54      1913843.13       443358.66
      1914286.66       443045.59      1914722.35       443003.85
      1914805.84       442946.45      1915019.77       442487.27
      1915171.09       442435.09      1915442.42       442132.46
       1915901.6       442242.03      1916301.79      442070.729

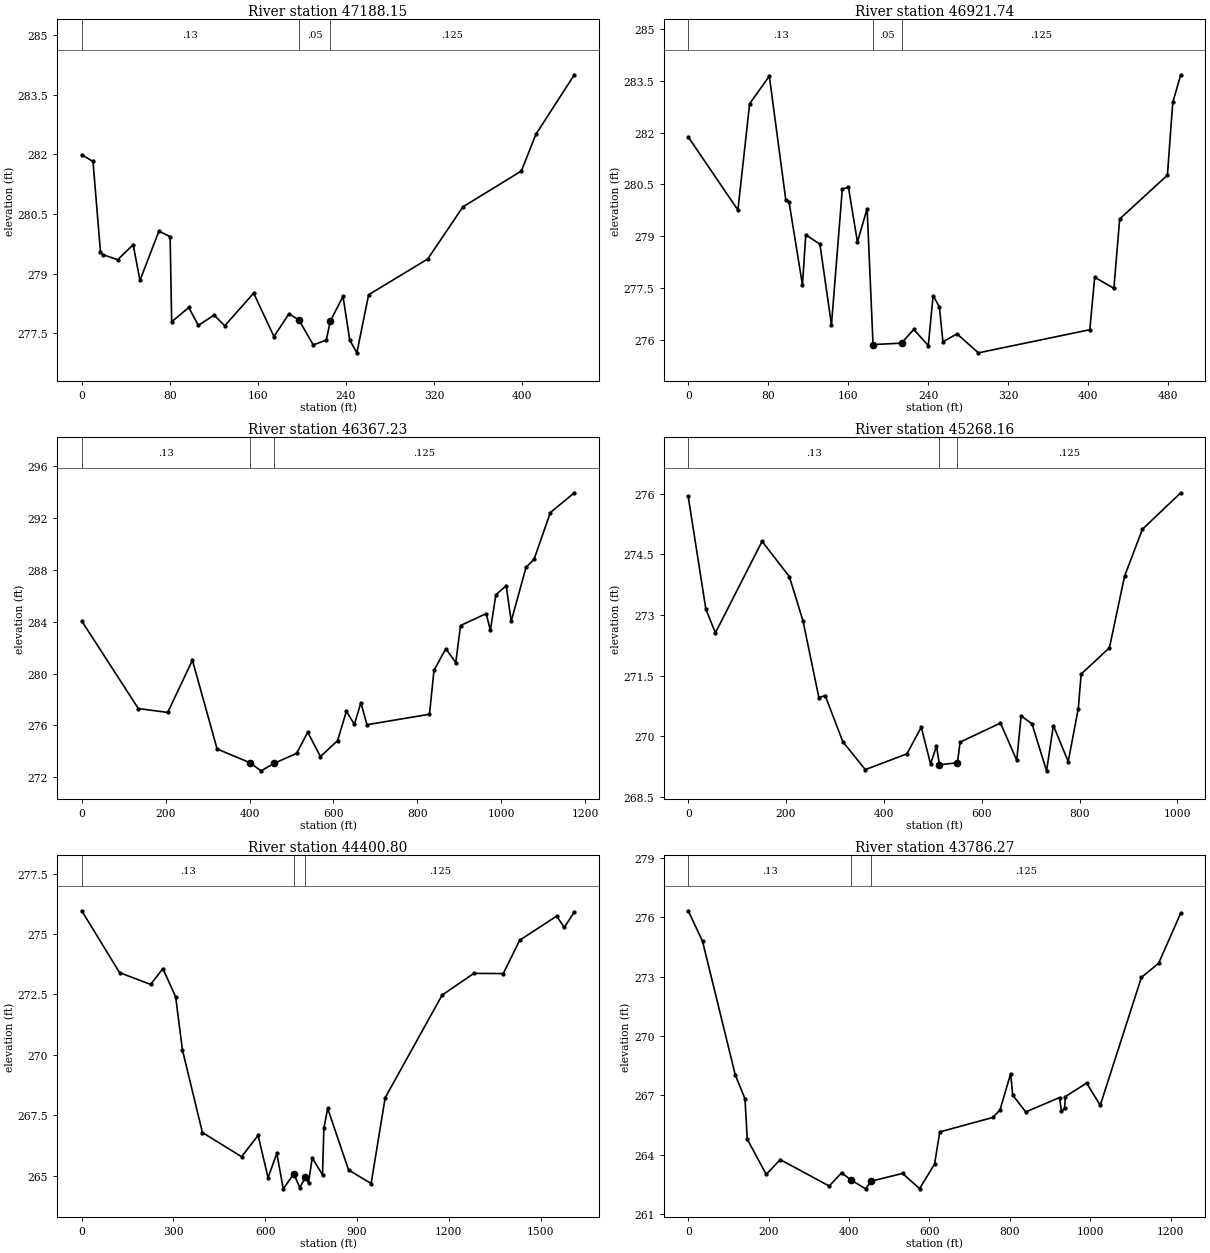
Type RM Length L Ch R = 1 ,47188.15,222.88,266.42,299.66
XS GIS Cut Line= 5
     1909843.554      447970.703     1909681.364      447929.088
     1909577.862      447908.815     1909514.907      447900.278
     1909403.935      447903.479
#Sta/Elev= 30
       0  281.99   10.24  281.82   17.01  279.55   19.07  279.48   32.66  279.35
   46.73  279.73   52.89  278.83   70.11  280.07   80.28  279.93    81.7  277.79
    97.2  278.15  105.95   277.7  120.22  277.96  129.89  277.69  156.16  278.51
  174.61  277.42   188.2  277.99  197.24  277.84   210.3  277.21  222.17  277.33
  225.71   277.8  237.34  278.43  243.47  277.33  249.92  277.01   260.6  278.47
  314.33  279.37  346.26  280.68  399.35  281.58  412.49   282.5  447.46     284
#Mann= 3 , 0 , 0
       0     .13       0  197.24     .05       0  225.71    .125       0
Bank Sta=197.24,225.71
XS Rating Curve= 0
Exp/Cntr=.3,.1

Type RM Length L Ch R = 1 ,46921.74,537.82,554.5,631.03
XS GIS Cut Line= 5
      1909899.44      447817.316     1909752.722      447678.601
     1909715.376      447657.261     1909604.671      447613.246
     1909476.627      447602.575
#Sta/Elev= 30
       0  281.88   49.69  279.76   61.43  282.84   81.12  283.64   97.61  280.05
  100.85  279.99  114.24  277.59  117.55  279.04   131.7  278.77  143.25  276.43
  154.11  280.37  160.24  280.42  169.23  278.83  178.91   279.8  184.83  275.86
  213.29   275.9   225.5   276.3  240.06  275.83  244.92  277.28  251.17  276.95
   254.7  275.94  268.79  276.17  290.19  275.62  401.57  276.29  406.47  277.81
  425.66  277.49  431.45   279.5  479.18  280.77  484.52  282.88  492.55  283.68
#Mann= 3 , 0 , 0
       0     .13       0  184.83     .05       0  213.29    .125       0
Bank Sta=184.83,213.29
XS Rating Curve= 0
Exp/Cntr=.3,.1

Type RM Length L Ch R = 1 ,46367.23,1125.61,1099.07,1064.32
XS GIS Cut Line= 5
     1910310.207      447534.051     1910174.743      447367.327
     1909947.581      447100.568     1909617.519      446869.238
     1909419.534      446811.926
#Sta/Elev= 30
       0  284.06  134.92   277.3  204.99     277  263.86  281.03  322.75  274.18
  400.82  273.12  427.65  272.49  458.18  273.06  512.27  273.84  538.84  275.47
  569.06  273.59  609.92  274.82  630.97  277.09  650.11  276.08  665.48  277.75
  680.01  276.05  829.09  276.86  839.71  280.24  867.97  281.92  891.74  280.85
  903.07  283.71  964.18  284.63  974.24  283.34   987.3  286.08 1011.94  286.79
 1023.87  284.04 1059.27   288.2 1078.48  288.83 1117.16  292.43 1174.36  293.96
#Mann= 3 , 0 , 0
       0     .13       0  400.82     .05       0  458.18    .125       0
Bank Sta=400.82,458.18
XS Rating Curve= 0
Exp/Cntr=.3,.1

Type RM Length L Ch R = 1 ,45268.16,751.18,867.36,898.95
XS GIS Cut Line= 4
     1911313.419      446892.684      1911154.51      446770.245
     1910664.757       446366.46     1910500.638      446316.963
#Sta/Elev= 30
       0  275.93   36.16  273.14    55.6  272.56  150.97  274.82  206.68  273.95
  234.53  272.86  267.09  270.96  279.94  271.01     316  269.87  361.95  269.18
  447.09  269.57  476.35  270.23  495.28  269.32  507.47  269.76  513.56   269.3
  550.35  269.35  555.71  269.86  638.26  270.33  671.49  269.41  680.45  270.51
  702.67  270.31  732.43  269.15  746.35  270.27  776.67  269.38  797.32  270.69
   803.1  271.54  860.91  272.19  891.86  273.96  928.38  275.12 1006.77  276.02
#Mann= 3 , 0 , 0
       0     .13       0  513.56     .05       0  550.35    .125       0
Bank Sta=513.56,550.35
XS Rating Curve= 0
Exp/Cntr=.3,.1

Type RM Length L Ch R = 1 ,44400.80,771.88,614.52,551.37
XS GIS Cut Line= 6
     1911498.379      446595.706     1911542.665      446517.554
       1911560.9      446225.786     1911336.865      445663.091
     1911274.343       445605.78      1910784.59      445384.349
#Sta/Elev= 30
       0  275.96  123.66   273.4  225.31  272.91  265.28  273.57  307.03   272.4
   329.4  270.19  394.59  266.78  522.51  265.78  576.58  266.66  609.27  264.91
  637.75  265.92  658.87  264.45  693.26  265.07  712.94   264.5  731.12  264.92
  741.45   264.7  753.55  265.73  787.26  265.03   791.6  266.95  804.12  267.78
  872.42  265.23  946.14  264.67  992.05  268.22 1178.22  272.47 1282.22  273.37
 1378.22  273.36  1431.8  274.74 1552.69  275.74 1577.52  275.27 1610.48  275.91
#Mann= 3 , 0 , 0
       0     .13       0  693.26     .05       0  731.12    .125       0
Bank Sta=693.26,731.12
XS Rating Curve= 0
Exp/Cntr=.3,.1

Type RM Length L Ch R = 1 ,43786.27,648.17,676.02,671.33
XS GIS Cut Line= 5
     1912230.159      445625.318     1912071.413      445556.121
     1911639.948       445356.67     1911302.103      445149.079
     1911159.638      445039.177
#Sta/Elev= 30
       0  276.34   35.61   274.8  117.11  268.03  141.14  266.83  146.93  264.78
  194.07     263  228.89  263.75  350.75  262.41  381.23  263.08  405.79  262.71
   441.1  262.27  455.42  262.66     533  263.05  575.43  262.28  612.76  263.53
  625.63  265.15  757.23  265.88  775.35  266.26  801.82  268.09  807.03  267.01
  839.51  266.16  923.54  266.89  928.05  266.19  935.94  266.35  938.08  266.94
  990.67  267.62 1024.68   266.5 1127.05  272.97 1169.78  273.68 1224.96  276.23
#Mann= 3 , 0 , 0
       0     .13       0  405.79     .05       0  455.42    .125       0
Bank Sta=405.79,455.42
XS Rating Curve= 0
Exp/Cntr=.5,.3

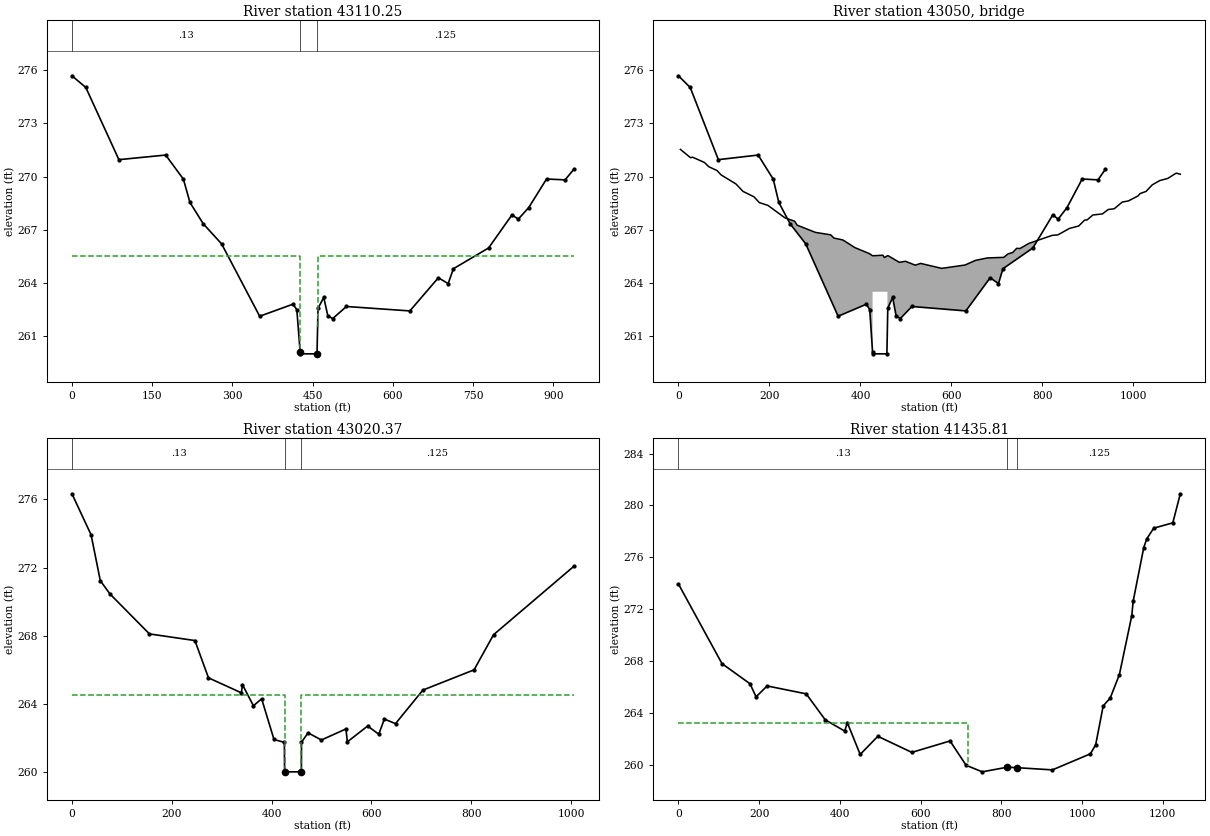
Type RM Length L Ch R = 1 ,43110.25,91.59,89.88,84.45
XS GIS Cut Line= 4
     1912364.483        445063.6     1912083.624      444888.572
     1911802.765      444685.051     1911574.821      444558.868
#Sta/Elev= 30
       0  275.68   25.93  275.02   87.76  270.95  175.19  271.21  208.37  269.85
  220.58  268.54  245.31  267.34  279.79   266.2  350.96  262.12  413.21   262.8
  420.43  262.49  426.64260.0889  426.87     260  458.11     260  460.07  262.57
  470.77  263.18  478.41  262.14  487.57  261.99  513.14  262.67  631.73  262.42
  684.99  264.29  703.33  263.96  713.14   264.8  778.91  265.97  822.49  267.83
  834.58   267.6  853.96  268.25  887.28  269.86  921.93  269.81  938.32  270.41
#Mann= 3 , 0 , 0
       0     .13       0  426.64     .05       0  458.11    .125       0
#XS Ineff= 2 , 0
       0  426.64   265.5  459.28       0   265.5
Permanent Ineff=
       F       F
Bank Sta=426.64,458.11
XS Rating Curve= 0
Exp/Cntr=.5,.3

Type RM Length L Ch R = 3 ,43050   ,,,
BEGIN DESCRIPTION:
L McLaughlin Rd; opening size estimated from similar road class and ortho photo
END DESCRIPTION:
Bridge Culvert--1,0,-1,-1, 0
Deck Dist Width WeirC Skew NumUp NumDn MinLoCord MaxHiCord MaxSubmerge Is_Ogee
31,20,2.6,0, 60, 60, , , .95, 0, 0,0,,
    4.34    26.6   31.07   57.23   66.83    84.6   93.84  126.43  141.95  166.32
   177.7  196.79  234.05  255.39  260.61  300.98  334.69  341.65  361.52  387.82
  419.73  426.64  449.36  452.49  459.28  461.07  485.57  498.74  520.59  532.18
  578.63  629.97  652.65  679.32   714.9  724.47  734.32  743.27  750.63  770.21
  821.29  833.95  859.19  879.66  892.47  897.95  910.76   931.7  944.55  957.58
  975.42  988.49 1009.68 1014.62 1027.72 1041.17 1057.59 1075.19 1093.77  1102.9
  271.53  271.06  271.09  270.79  270.55  270.34  270.09  269.58  269.16  268.85
  268.53  268.37  267.67  267.48  267.26  266.85  266.71  266.53  266.42  265.99
  265.65  265.53  265.56  265.43  265.53  265.53  265.16  265.22     265   265.1
  264.82  265.01  265.27  265.41  265.44  265.64  265.71  265.95  265.94  266.23
  266.68  266.71  267.07  267.21  267.54  267.55  267.83  267.89  268.14  268.18
  268.56  268.62   268.9  269.04  269.16  269.53  269.77  269.89  270.19  270.13
                                                                                
                                                                                
           263.5   263.5   263.5   263.5
                                                                                
                                                                                
                                                                                
    4.34    26.6   31.07   57.23   66.83    84.6   93.84  126.43  141.95  166.32
   177.7  196.79  234.05  255.39  260.61  300.98  334.69  341.65  361.52  387.82
  419.73  426.64  449.36  452.49  459.28  461.07  485.57  498.74  520.59  532.18
  578.63  629.97  652.65  679.32   714.9  724.47  734.32  743.27  750.63  770.21
  821.29  833.95  859.19  879.66  892.47  897.95  910.76   931.7  944.55  957.58
  975.42  988.49 1009.68 1014.62 1027.72 1041.17 1057.59 1075.19 1093.77  1102.9
  271.53  271.06  271.09  270.79  270.55  270.34  270.09  269.58  269.16  268.85
  268.53  268.37  267.67  267.48  267.26  266.85  266.71  266.53  266.42  265.99
  265.65  265.53  265.56  265.43  265.53  265.53  265.16  265.22     265   265.1
  264.82  265.01  265.27  265.41  265.44  265.64  265.71  265.95  265.94  266.23
  266.68  266.71  267.07  267.21  267.54  267.55  267.83  267.89  268.14  268.18
  268.56  268.62   268.9  269.04  269.16  269.53  269.77  269.89  270.19  270.13
                                                                                
                                                                                
           263.5   263.5   263.5   263.5
                                                                                
                                                                                
                                                                                
BR Coef=-1 , 1 , 0 ,, 0 ,,,.8,0,1.2,1,
WSPro=,,,, 1 ,,,, 0 ,,,, 0 ,,,,-1 ,-1 ,-1 , 0 , 0 , 0 , 0 , 0
BC Design=,, 0 ,, 0 ,,,,,,

Type RM Length L Ch R = 1 ,43020.37,1368.05,1584.56,1669.11
XS GIS Cut Line= 5
     1912413.328      444990.332     1912103.976      444790.882
     1911884.173      444644.347     1911749.849      444538.516
     1911582.962      444424.544
#Sta/Elev= 30
       0  276.33   38.33  273.92   56.78  271.23   76.03  270.45  155.18   268.1
  246.31  267.71  273.47  265.52  339.42  264.64  341.53  265.12  363.51  263.88
  379.94  264.29  404.72   261.9  425.41  261.73  425.91     260  426.64     260
  459.28     260  459.63     260  459.79  261.74  472.92  262.29  499.66  261.87
   548.9  262.52  551.57  261.76   592.3  262.69  614.59  262.21  625.76   263.1
  648.09  262.83  702.89   264.8  805.47  265.99   844.4  268.05 1005.34  272.07
#Mann= 3 , 0 , 0
       0     .13       0  426.64     .05       0  459.28    .125       0
#XS Ineff= 2 , 0
       0  426.64   264.5  459.28       0   264.5
Permanent Ineff=
       F       F
Bank Sta=426.64,459.28
XS Rating Curve= 0
Exp/Cntr=.5,.3

Type RM Length L Ch R = 1 ,41435.81,792.97,753.75,634.87
XS GIS Cut Line= 5
     1912885.496       444676.91     1912979.116      444249.516
     1912991.327      443655.235      1913015.75       443516.84
     1913052.384      443455.784
#Sta/Elev= 30
       0  273.95  107.95  267.81  177.34  266.26   192.4  265.25  219.85  266.09
  316.69  265.48  363.79  263.48  412.04  262.61  418.57  263.26  450.37  260.81
  494.16  262.21  578.36  260.97   673.1  261.85  712.69  259.98  752.74  259.47
  815.27  259.83  839.22  259.79  926.71  259.62 1020.97  260.86 1033.96  261.56
 1052.65  264.56 1069.85  265.15 1092.65  266.96 1123.36   271.5 1126.81  272.62
 1153.03  276.75 1160.42  277.42 1177.75  278.25 1225.03  278.66 1243.67   280.9
#Mann= 3 , 0 , 0
       0     .13       0  815.27     .05       0  839.22    .125       0
#XS Ineff= 2 , 0
          716.54  263.21
Permanent Ineff=
       F       F
Bank Sta=815.27,839.22
XS Rating Curve= 0
Exp/Cntr=.3,.1