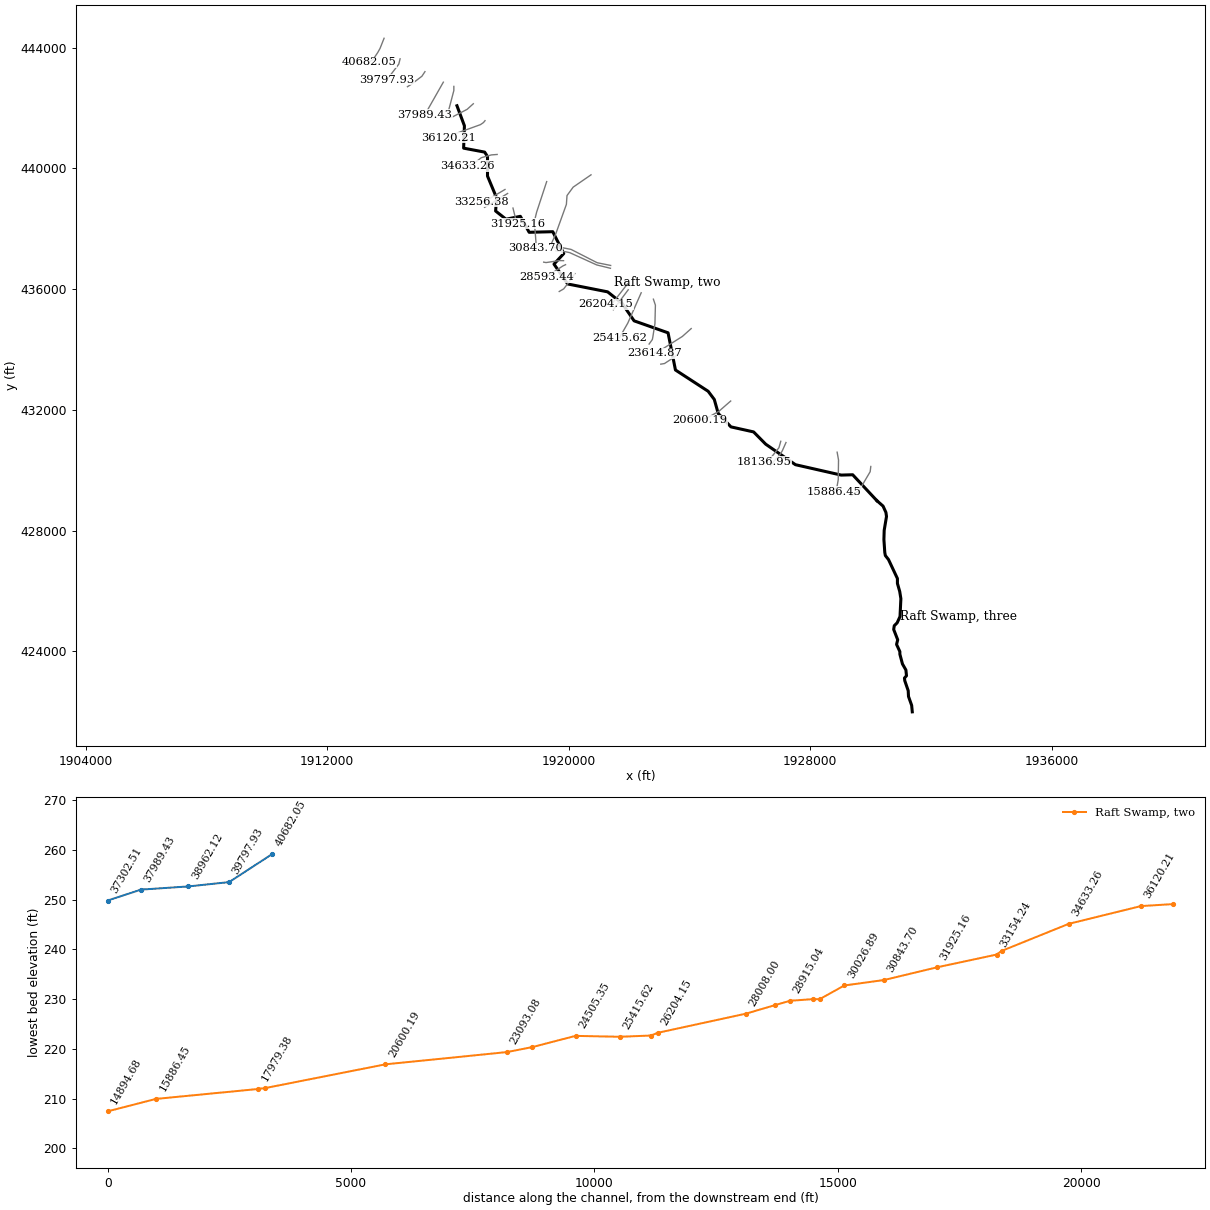
HEC-RAS study upraft.prj: Upper Raft Swamp

--- upraft.g04 (geometry) --- (continued)

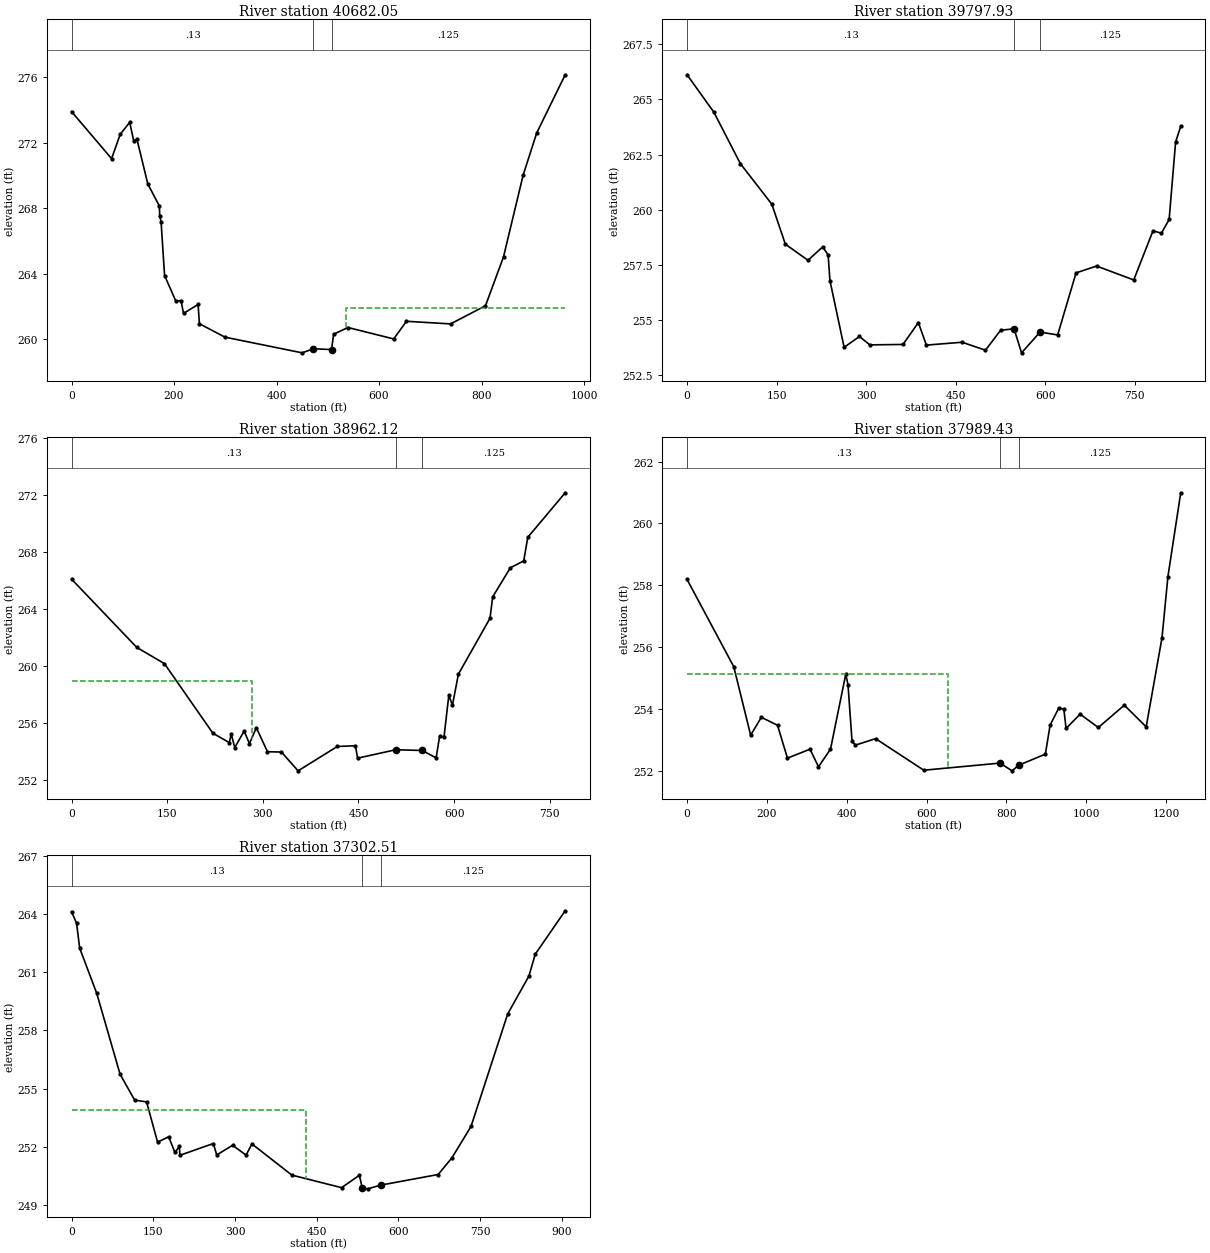
Type RM Length L Ch R = 1 ,40682.05,914.64,884.13,862.58
XS GIS Cut Line= 5
     1913887.869      444306.138     1913753.816      443969.741
     1913680.466      443838.217      1913521.12      443597.933
     1913382.008      443514.466
#Sta/Elev= 30
       0  273.91   78.14  271.03   94.99  272.52  113.49  273.25  121.42   272.1
  127.62  272.22  148.84  269.48  171.44  268.13  172.09  267.53  174.72  267.17
  181.53  263.88  203.58  262.31  213.68  262.35   218.5  261.56  246.97  262.11
  249.53  260.93  299.33  260.11  449.99  259.15     472   259.4  507.39  259.35
  511.42  260.29  539.33   260.7  628.68     260  653.48  261.08   739.6  260.92
  807.71  262.03  842.89  265.02   881.2  270.02  907.67   272.6  963.27  276.16
#Mann= 3 , 0 , 0
       0     .13       0     472     .05       0  507.39    .125       0
#XS Ineff= 2 , 0
                          535.55          261.91
Permanent Ineff=
       F       F
Bank Sta=472,507.39
XS Rating Curve= 0
Exp/Cntr=.3,.1

Type RM Length L Ch R = 1 ,39797.93,847.93,835.8,826.3
XS GIS Cut Line= 3
     1914418.639      443624.676      1914373.79      443448.729
     1913983.947      442934.689
#Sta/Elev= 30
       0  266.11   45.01  264.41   89.16  262.09  141.94  260.25  164.57  258.44
  202.52  257.71  227.12  258.32  236.23  257.95  239.24  256.79  263.02  253.77
  288.69  254.26  306.05  253.88  361.58   253.9  387.33  254.89  400.72  253.87
  460.56     254  499.71  253.64  524.98  254.54  547.55  254.61  560.13  253.52
  591.17  254.46  620.59  254.33  651.42  257.14  685.86  257.45  748.03  256.82
   780.2  259.04  794.44  258.94  807.29  259.56   818.1  263.06  826.72  263.78
#Mann= 3 , 0 , 0
       0     .13       0  547.55     .05       0  591.17    .125       0
Bank Sta=547.55,591.17
XS Rating Curve= 0
Exp/Cntr=.3,.1

Type RM Length L Ch R = 1 ,38962.12,895.95,972.69,977.37
XS GIS Cut Line= 4
     1915241.761      443200.365        1915140.      443047.724
     1914799.102      442788.235     1914661.726      442701.739
#Sta/Elev= 30
       0  266.11  102.41  261.31  145.63  260.18  221.69  255.29  247.48  254.63
  250.45  255.25  255.94  254.28  270.67  255.44  279.08  254.56  289.81  255.68
  307.29  253.99  329.26  253.97  355.29  252.65  416.81  254.36  445.25  254.41
  448.63  253.54  508.39  254.13  549.99  254.08  571.79  253.56  577.24  255.07
  584.16  255.03  591.72  257.96  597.36  257.25  606.74  259.44  656.29  263.36
  660.47  264.86  688.13   266.9   709.2  267.39  715.48  269.04  774.21  272.17
#Mann= 3 , 0 , 0
       0     .13       0  508.39     .05       0  549.99    .125       0
#XS Ineff= 2 , 0
          282.46  258.95
Permanent Ineff=
       F       F
Bank Sta=508.39,549.99
XS Rating Curve= 0
Exp/Cntr=.3,.1

Type RM Length L Ch R = 1 ,37989.43,629.45,686.92,705.65
XS GIS Cut Line= 3
     1915850.361      442851.891     1915243.173      441782.412
     1915243.173      441775.512
#Sta/Elev= 30
       0  258.19  117.06  255.37  159.28  253.16  186.06  253.74  226.64  253.48
  251.44  252.42  308.03  252.71  329.22  252.14  359.29  252.71  397.53  255.13
  403.14  254.79  413.32  252.96  421.78  252.84   472.3  253.05  593.02  252.03
  783.97  252.26  814.17  252.01  830.51  252.19   897.6  252.55  909.54  253.49
  931.33  254.04  943.89     254  949.47  253.38   984.6  253.84  1030.3  253.41
 1095.38  254.13 1150.17  253.43 1189.83  256.31 1204.57  258.28 1236.72  260.99
#Mann= 3 , 0 , 0
       0     .13       0  783.97     .05       0  830.51    .125       0
#XS Ineff= 2 , 0
          653.55  255.14
Permanent Ineff=
       F       F
Bank Sta=783.97,830.51
XS Rating Curve= 0
Exp/Cntr=.3,.1

Type RM Length L Ch R = 1 ,37302.51,0,0,0
XS GIS Cut Line= 4
     1916198.309      442711.915     1916198.309      442574.538
     1916045.669      441994.503     1915999.876      441831.687
#Sta/Elev= 30
       0  264.13    9.21  263.54   14.96  262.25   46.23  259.92   89.11  255.74
   115.9   254.4  137.75  254.31  157.98  252.23  178.33  252.51  189.74   251.7
  198.07  252.01  198.75  251.55  260.29  252.16  266.56  251.57  295.73  252.07
  320.37  251.56  331.19  252.14  404.41  250.53  495.82  249.88  528.39  250.52
  533.63  249.88  543.92  249.82  567.24  250.01  673.03  250.56  698.11  251.41
  733.33  253.04  800.72  258.85  839.68  260.81  851.35  261.94  906.29  264.18
#Mann= 3 , 0 , 0
       0     .13       0  533.63     .05       0  567.24    .125       0
#XS Ineff= 2 , 0
          431.28  253.91
Permanent Ineff=
       F       F
Bank Sta=533.63,567.24
XS Rating Curve= 0
Exp/Cntr=.3,.1

River Reach=Raft Swamp      ,two
Reach XY= 30
      1916301.79      442070.729      1916548.62       441407.17
      1916522.53       440666.23      1917219.12       440535.78
      1917313.04       440389.68      1917313.04       439742.66
     1917615.022      439017.949      1917581.76       438584.28
      1917926.14       438312.95     1918401.378       438409.07
     1918692.776      437879.988     1919474.884      437899.732
       1919838.5       437175.45      1919514.99       436825.85
      1919968.95       436168.39      1921291.69        435907.5
      1921766.52       435531.81       1922168.3        434947.4
      1923292.76       434550.84        1923538.       433319.42
      1924620.71         432615.      1924824.21       432343.67
      1924954.66       431879.28       1925374.7       431435.76
      1926126.08       431268.78      1926527.86       430861.79
      1927511.43       430183.46      1929027.23       429839.08
      1929408.14       429849.51      1930208.59      428992.227

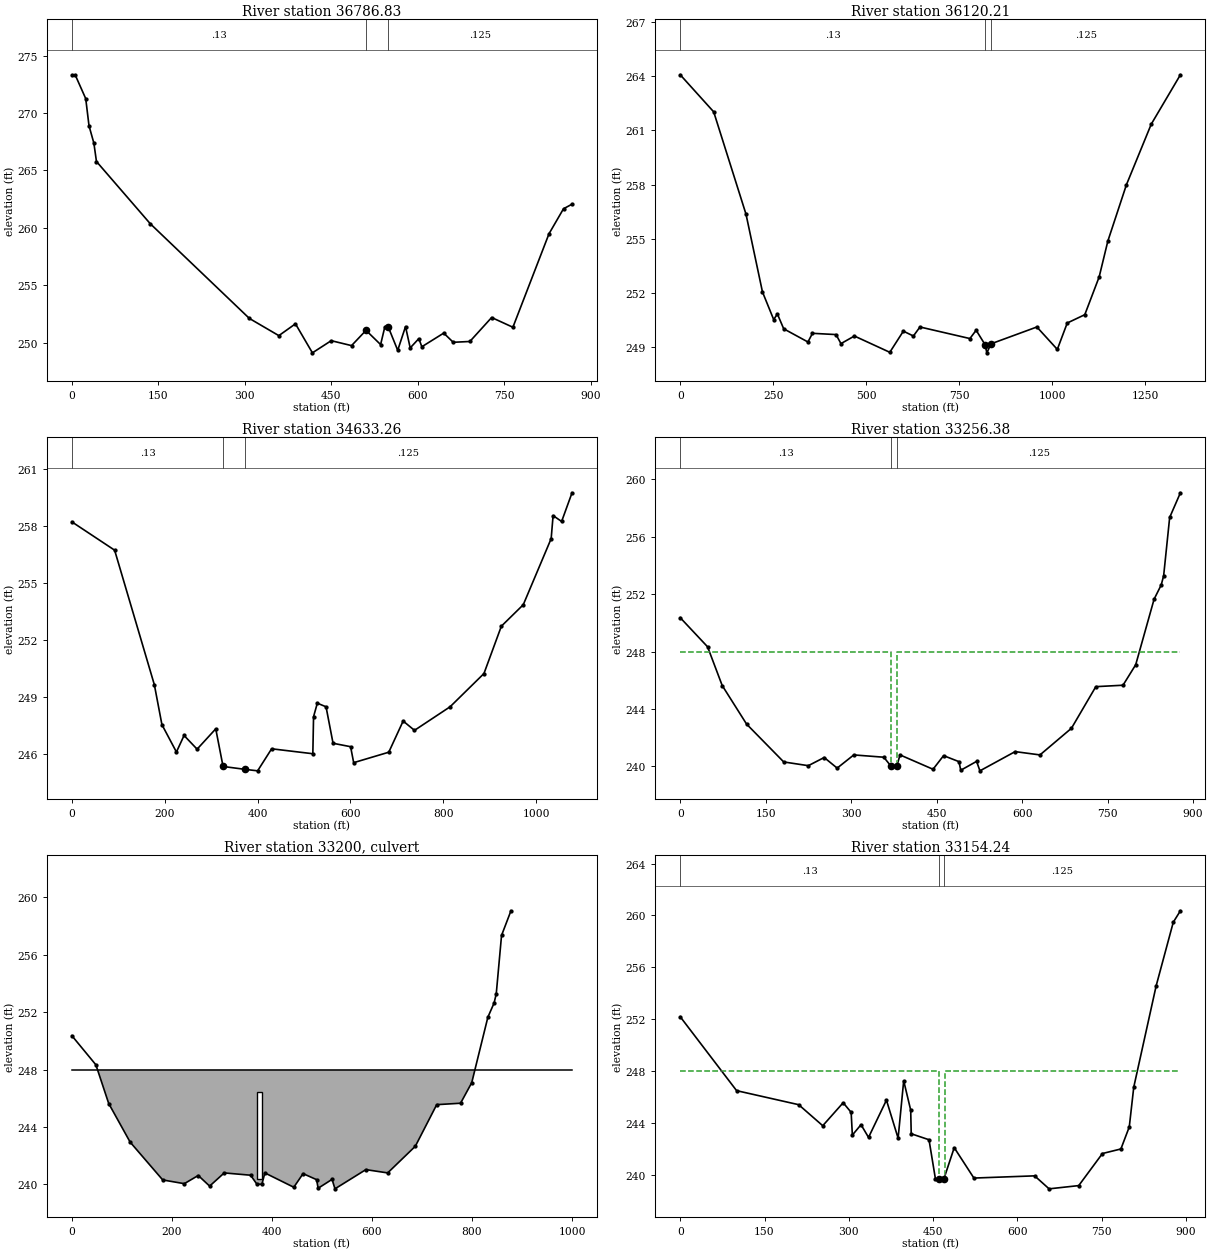
Type RM Length L Ch R = 1 ,36786.83,613.09,666.62,591.78
XS GIS Cut Line= 4
     1916843.941      442137.755     1916636.945      441951.459
     1916178.104      441713.413     1916112.556      441682.364
#Sta/Elev= 30
       0  273.28    5.67  273.34   24.06  271.26   29.77  268.89    38.2  267.38
   42.68  265.78  135.96  260.36  308.01   252.1  359.15   250.6  387.99  251.63
  417.41   249.1  450.07  250.16  485.31  249.73  510.44  251.06  535.74  249.82
  542.91  251.33  549.13  251.34  565.43  249.32  578.97  251.39   587.1  249.53
  602.08  250.34   607.3  249.63  645.26  250.82  661.76  250.02  690.63  250.09
  728.42  252.18  765.31  251.33  827.95  259.48  853.11  261.66  867.93  262.06
#Mann= 3 , 0 , 0
       0     .13       0  510.44     .05       0  549.13    .125       0
Bank Sta=510.44,549.13
XS Rating Curve= 0
Exp/Cntr=.3,.1

Type RM Length L Ch R = 1 ,36120.21,1352.36,1486.95,1340.48
XS GIS Cut Line= 5
     1917231.178      441577.285      1917175.21      441511.141
     1917078.538      441444.997     1916218.661      441134.627
     1916030.404      441007.427
#Sta/Elev= 30
       0  264.08      90  262.03  176.89  256.37  221.16  252.07  251.35  250.54
  261.29  250.85  278.26  250.03  343.47   249.3  355.66  249.78  419.05  249.71
  432.23  249.21  468.42  249.63  563.63  248.73  600.07   249.9  627.07  249.63
  644.72  250.13  779.02  249.49  795.85  249.95  819.86  249.15  824.57   248.7
  835.94   249.2  959.14  250.13 1014.12  248.89 1040.83  250.35 1088.01  250.81
 1126.67   252.9 1149.99  254.88 1200.04     258 1266.78  261.35 1345.16  264.08
#Mann= 3 , 0 , 0
       0     .13       0  819.86     .05       0  835.94    .125       0
Bank Sta=819.86,835.94
XS Rating Curve= 0
Exp/Cntr=.3,.1

Type RM Length L Ch R = 1 ,34633.26,1309.66,1376.88,1378.33
XS GIS Cut Line= 5
     1917633.132       440457.92     1917439.787      440442.656
     1917109.066      440351.071     1916854.664      440152.638
     1916651.143      440076.318
#Sta/Elev= 30
       0  258.22   92.07  256.73  177.64  249.65  193.95  247.55  225.18  246.11
  241.61  246.98  269.71  246.26  309.86  247.33  325.59  245.35  372.25   245.2
  400.01  245.12  430.19  246.28  518.93  246.02  520.47  247.97  528.59  248.68
  547.36  248.49  562.46  246.57  600.24  246.39  606.87  245.55  682.45   246.1
   713.4  247.74  737.83  247.25  814.49  248.49  887.43  250.24   924.9  252.73
  972.09  253.86 1032.18  257.34  1036.3  258.55 1054.66  258.24 1077.11  259.75
#Mann= 3 , 0 , 0
       0     .13       0  325.59     .05       0  372.25    .125       0
Bank Sta=325.59,372.25
XS Rating Curve= 0
Exp/Cntr=.5,.3

Type RM Length L Ch R = 1 ,33256.38,101.36,102.15,103.26
XS GIS Cut Line= 3
     1917892.621       439297.85     1917287.147      438941.689
     1917119.242      438890.808
#Sta/Elev= 30
       0  250.36      48  248.33   73.67  245.63  116.46  242.94  181.65   240.3
  224.79  240.04  252.68  240.61  275.45  239.87  304.61  240.79  357.35  240.63
     370     240     380     240  385.82  240.79  443.71  239.79  462.24  240.74
  489.28  240.32  492.35  239.72   520.2  240.34  526.01  239.68  587.81  241.02
  631.43  240.79   686.7  242.65  729.43  245.55  777.14  245.65  799.45  247.08
  831.72  251.65  844.18  252.64  848.47  253.28  859.05  257.35   877.9  259.07
#Mann= 3 , 0 , 0
       0     .13       0     370     .05       0     380    .125       0
#XS Ineff= 2 , 0
       0     370     248     380       0     248
Permanent Ineff=
       F       F
Bank Sta=370,380
XS Rating Curve= 0
Exp/Cntr=.5,.3

Type RM Length L Ch R = 2 ,33200   ,,,
BEGIN DESCRIPTION:
US401; NCDOT small pipes 46 2008
END DESCRIPTION:
Bridge Culvert--1,0,-1,-1, 0
Deck Dist Width WeirC Skew NumUp NumDn MinLoCord MaxHiCord MaxSubmerge Is_Ogee
43,30,2.6,0, 2, 2, , , .95, 0, 0,0,,
       0    1000
     248     248
                
       0    1000
     248     248
                
BR Coef=-1 , 1 , 0 ,, 0 ,,,.8,0,1.2,1,
WSPro=,,,, 1 ,,,, 0 ,,,, 0 ,,,,-1 ,-1 ,-1 , 0 , 0 , 0 , 0 , 0
Culvert=2,6,10,30,.03,.5,1,8,1,240.4,375,239.7,466,Culvert #1  , 0 ,43
Culvert Bottom n=.03
BC Design=,, 0 ,, 0 ,,,,,,

Type RM Length L Ch R = 1 ,33154.24,1004.2,1229.08,1427.33
XS GIS Cut Line= 3
     1917979.118      439165.562     1917363.467      438789.048
     1917215.914      438707.639
#Sta/Elev= 30
       0   252.2  100.33  246.51  210.78  245.43  253.65  243.81  289.99  245.58
  304.19  244.84  306.35  243.09  321.77  243.89  335.13  242.91  367.01  245.78
  387.77  242.85  397.71  247.27  410.18  245.01   411.1  243.19  442.75  242.73
  454.26   239.7  460.32   239.7  469.09   239.7  487.63  242.12  522.65  239.78
  630.69  239.95  656.49  238.95  709.23   239.2  751.43  241.67  784.28  242.02
  799.19  243.72  807.16  246.78  847.13   254.6   877.5  259.48  890.18  260.36
#Mann= 3 , 0 , 0
       0     .13       0  460.32     .05       0  469.09    .125       0
#XS Ineff= 2 , 0
       0     461     248     471       0     248
Permanent Ineff=
       F       F
Bank Sta=460.32,469.09
XS Rating Curve= 0
Exp/Cntr=.5,.3

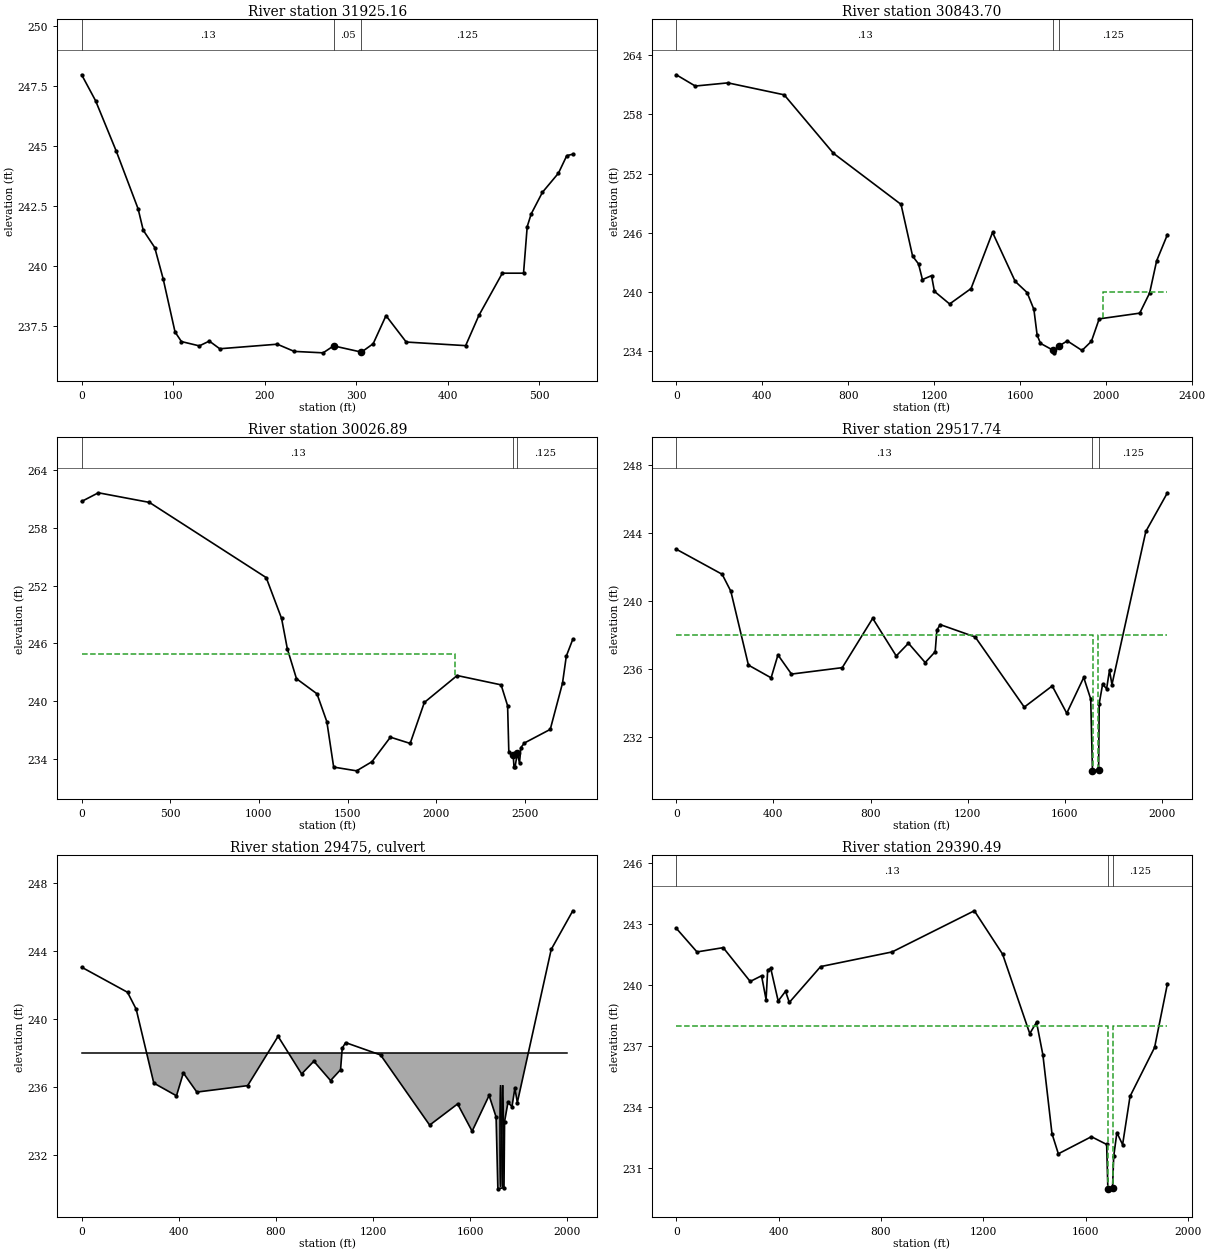
Type RM Length L Ch R = 1 ,31925.16,974.14,1081.45,967.14
XS GIS Cut Line= 3
     1918157.199      438682.199     1918264.047      438244.629
     1918304.751      438168.309
#Sta/Elev= 30
       0  247.97    15.2  246.89    37.9  244.78   61.73  242.38   67.32  241.49
   79.87  240.77   89.06  239.47  102.08  237.25  109.07  236.85  128.63  236.67
  139.57  236.87  150.95  236.55  213.83  236.74  232.36  236.44  263.98  236.38
  275.42  236.67  305.88  236.41  318.69  236.76  332.71  237.93  354.81  236.83
  419.77  236.68  434.25  237.94  459.89   239.7  483.06   239.7  487.07  241.64
  491.42  242.17  503.69  243.07  521.24  243.87  530.35   244.6  536.92  244.66
#Mann= 3 , 0 , 0
       0     .13       0  275.42     .05       0  305.88    .125       0
Bank Sta=275.42,305.88
XS Rating Curve= 0
Exp/Cntr=.3,.1

Type RM Length L Ch R = 1 ,30843.70,772.95,816.82,618.4
XS GIS Cut Line= 6
      1919272.97      439559.011     1918939.759      438545.765
     1918844.555      438151.348     1918887.422      437959.248
     1918924.634      437464.045      1918896.01      437346.684
#Sta/Elev= 30
       0  262.01   88.31  260.87  240.36  261.19  502.26  259.98  731.41  254.06
 1046.33  248.88 1100.18  243.64 1127.75  242.85 1145.94  241.26 1188.29  241.66
 1201.74  240.07 1272.53  238.79 1372.23  240.35 1472.37  246.04 1577.79  241.08
 1633.15  239.95 1664.87  238.24 1679.96  235.64 1695.62   234.8 1751.96  234.13
 1759.33  233.84 1781.68  234.53 1820.34  235.05 1888.92  234.08 1932.68  235.01
 1968.87  237.28 2157.53  237.86 2203.66   239.9 2236.34  243.16  2286.6  245.82
#Mann= 3 , 0 , 0
       0     .13       0 1751.96     .05       0 1781.68    .125       0
#XS Ineff= 2 , 0
                          1984.6          240.04
Permanent Ineff=
       F       F
Bank Sta=1751.96,1781.68
XS Rating Curve= 0
Exp/Cntr=.3,.1

Type RM Length L Ch R = 1 ,30026.89,679.3,509.14,349.73
XS GIS Cut Line= 6
      1920741.84      439783.422     1920150.214      439375.403
     1919946.205       439096.59     1919925.804      438804.177
     1919576.649      437835.795     1919420.696        437484.9
#Sta/Elev= 30
       0  260.75   94.32  261.65  382.09  260.65 1041.04  252.83 1127.88  248.58
 1160.24  245.43 1211.81  242.32 1327.44  240.75 1383.13  237.85 1421.64  233.13
 1550.92  232.74 1637.62  233.69 1741.76  236.24 1853.05  235.59 1933.16  239.85
 2118.12  242.65 2366.12  241.68 2402.86  239.51 2409.74  234.71 2434.56  234.34
 2438.93  233.13 2445.23  233.17 2457.62  234.57 2470.03  233.55 2477.56  235.16
 2498.17  235.64 2643.44  237.05 2712.55  241.85  2734.1  244.67 2770.68  246.42
#Mann= 3 , 0 , 0
       0     .13       0 2434.56     .05       0 2457.62    .125       0
#XS Ineff= 2 , 0
         2104.27  244.91
Permanent Ineff=
       F       F
Bank Sta=2434.56,2457.62
XS Rating Curve= 0
Exp/Cntr=.5,.3

Type RM Length L Ch R = 1 ,29517.74,112.01,127.25,124.36
XS GIS Cut Line= 6
      1921392.33      436782.201     1920943.184      436872.726
     1920080.472      437313.521     1919838.793      437360.161
     1919790.455      437369.489     1919490.261      437374.577
#Sta/Elev= 30
       0  243.06  188.88  241.58   224.6  240.58  297.05  236.22  390.48  235.47
  418.68  236.82  474.33  235.69  683.49  236.07  808.84  238.98  905.73  236.76
  956.12  237.51 1025.04  236.37 1066.17  237.01 1073.06  238.28 1086.89  238.61
 1230.98  237.88 1433.01  233.74 1548.14  234.99 1607.96  233.38 1677.88  235.49
 1706.63  234.22 1713.91  229.98 1739.24  230.05 1741.62  233.95 1755.49  235.08
 1772.11  234.83 1784.02  235.92  1794.1  235.07 1933.66  244.11 2022.58  246.39
#Mann= 3 , 0 , 0
       0     .13       0 1713.91     .05       0 1739.24    .125       0
#XS Ineff= 2 , 0
       0 1717.86     238  1736.9       0     238
Permanent Ineff=
       F       F
Bank Sta=1713.91,1739.24
XS Rating Curve= 0
Exp/Cntr=.5,.3

Type RM Length L Ch R = 2 ,29475   ,,,
BEGIN DESCRIPTION:
SR1139; NCDOT small pipes 46 2036 and 46 2037
END DESCRIPTION:
Bridge Culvert--1,0,-1,-1, 0
Deck Dist Width WeirC Skew NumUp NumDn MinLoCord MaxHiCord MaxSubmerge Is_Ogee
34,18,2.6,0, 2, 2, , , .95, 0, 0,0,,
       0    2000
     238     238
                
       0    2000
     238     238
                
Multiple Barrel Culv=1,6,,18,.028,.5,1,1,1,230.1,230, 2,Culvert #1  , 0 ,34
    1725    1693    1734    1702
Culvert Bottom n=.028
BC Design=,, 0 ,, 0 ,,,,,,

Type RM Length L Ch R = 1 ,29390.49,370.21,475.45,478.86
XS GIS Cut Line= 6
      1921385.36      436688.193     1920929.257      436799.609
      1920034.68      437206.672     1919887.127        437237.2
     1919832.488      437241.606      1919571.67       437262.64
#Sta/Elev= 30
       0  242.79    80.9  241.63  183.38  241.84   288.9  240.18  333.23  240.46
  350.89  239.29   357.1  240.73  369.21  240.82  398.21  239.22     427   239.7
  441.68  239.15  564.06  240.91  843.59  241.63 1164.82  243.65 1275.32  241.52
  1381.5  237.62 1407.95  238.18 1432.85  236.57 1468.31  232.71 1493.19  231.72
 1622.35  232.56 1682.01  232.18 1686.74     230 1704.87  230.03 1709.54  231.59
 1721.93  232.76  1744.3  232.17 1773.37  234.54 1869.36  236.94 1919.52  240.07
#Mann= 3 , 0 , 0
       0     .13       0 1686.74     .05       0 1704.87    .125       0
#XS Ineff= 2 , 0
       0 1686.79     238 1705.54       0     238
Permanent Ineff=
       F       F
Bank Sta=1686.74,1704.87
XS Rating Curve= 0
Exp/Cntr=.5,.3

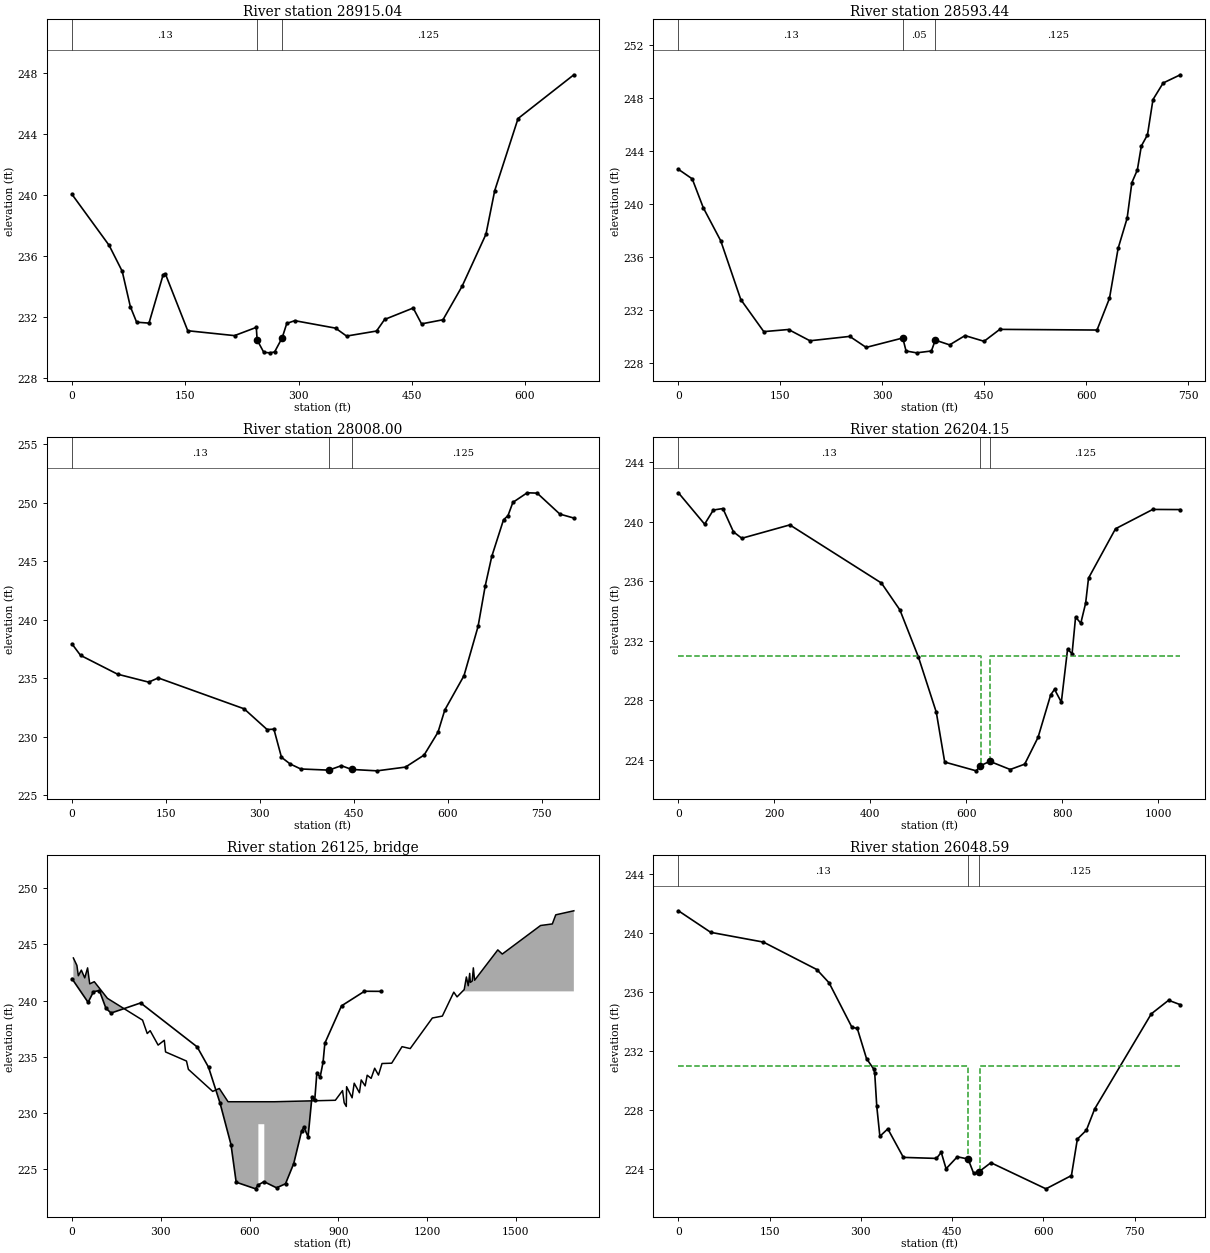
Type RM Length L Ch R = 1 ,28915.04,289.25,321.6,367.34
XS GIS Cut Line= 4
     1919832.029      436940.217     1919688.907       436943.08
     1919253.815      436877.243     1919173.667      436891.556
#Sta/Elev= 30
       0  240.07   49.23  236.72   66.56  235.02   77.32   232.7   85.66  231.68
  102.02  231.62  120.79   234.8  123.78  234.84  153.35  231.12  215.26   230.8
  244.12  231.34  245.22  230.51  254.06   229.7  262.36  229.67  268.37  229.73
  278.39  230.66  284.47   231.6  295.05  231.78   349.1  231.29  363.63  230.77
  403.32   231.1  414.03  231.86  451.87  232.61  462.93  231.57   491.3  231.84
  516.55  234.03  548.22  237.45  559.82  240.31  590.72  245.04  664.61  247.91
#Mann= 3 , 0 , 0
       0     .13       0  245.22     .05       0  278.39    .125       0
Bank Sta=245.22,278.39
XS Rating Curve= 0
Exp/Cntr=.3,.1

Type RM Length L Ch R = 1 ,28593.44,557.83,585.44,620.97
XS GIS Cut Line= 4
     1919897.869      436807.016     1919807.051      436764.278
     1919368.989      436475.798     1919283.513      436401.007
#Sta/Elev= 30
       0  242.61   20.34  241.89   36.62  239.71   62.27  237.22   91.76  232.79
   125.6  230.37  161.98  230.53  193.53  229.68  252.08  230.01  276.22  229.18
  330.11  229.89  334.93  228.91   350.4  228.77  372.24  228.91  377.96  229.73
  399.04  229.37  421.66  230.07  449.72  229.64  472.86  230.54  615.93  230.49
  634.23  232.88  646.96  236.65   660.2  238.92  667.19  241.61  675.23  242.56
  681.12  244.37  690.15  245.21  698.24  247.87  713.19  249.12  738.47  249.74
#Mann= 3 , 0 , 0
       0     .13       0  330.11     .05       0  377.96    .125       0
Bank Sta=330.11,377.96
XS Rating Curve= 0
Exp/Cntr=.3,.1

Type RM Length L Ch R = 1 ,28008.00,1747.4,1803.85,1756.35
XS GIS Cut Line= 4
     1920207.673      436514.701     1920029.592      436255.212
     1919836.247      436005.898     1919688.694      435919.402
#Sta/Elev= 30
       0  237.93   13.67  236.95   72.76  235.34  122.55  234.66  137.73  235.02
  274.87  232.38  311.53  230.61  322.41  230.64  334.47  228.24  348.25  227.67
  365.25  227.24  410.08  227.14  430.12  227.52  446.44   227.2  486.95  227.08
  532.49   227.4  562.19  228.43  584.37  230.38  595.23  232.28  625.86  235.21
  648.34  239.42  659.79  242.89   670.2   245.4  688.95  248.53  696.05  248.88
  703.91  250.02  726.76  250.84  742.68  250.81  778.87  249.02  801.25  248.68
#Mann= 3 , 0 , 0
       0     .13       0  410.08     .05       0  446.44    .125       0
Bank Sta=410.08,446.44
XS Rating Curve= 0
Exp/Cntr=.5,.3

Type RM Length L Ch R = 1 ,26204.15,146.29,155.56,162.5
XS GIS Cut Line= 3
     1921947.777      436168.715     1921408.446      435476.744
     1921240.542      435492.008
#Sta/Elev= 30
       0  241.95   54.61  239.84    72.8  240.79   92.75  240.89  114.73  239.32
  132.16  238.89  232.17  239.79  423.08  235.88  461.56  234.07  500.29  230.89
  537.41  227.19  554.91  223.84  620.59  223.25  629.27  223.59  648.83  223.89
  691.41  223.34  721.63   223.7  749.43   225.5  775.78  228.36  783.79  228.73
  797.95  227.87  811.04  231.45   820.3  231.11  827.64  233.59  838.53  233.18
  848.57  234.52  854.62  236.21  910.86  239.53  988.51  240.83 1045.92  240.82
#Mann= 3 , 0 , 0
       0     .13       0  629.27     .05       0  648.83    .125       0
#XS Ineff= 2 , 0
       0     630     231     650       0     231
Permanent Ineff=
       F       F
Bank Sta=629.27,648.83
XS Rating Curve= 0
Exp/Cntr=.5,.3

Type RM Length L Ch R = 3 ,26125   ,,,
BEGIN DESCRIPTION:
Unnamed Road; opening size estimated from similar road class
END DESCRIPTION:
Bridge Culvert--1,0,-1,-1, 0
Deck Dist Width WeirC Skew NumUp NumDn MinLoCord MaxHiCord MaxSubmerge Is_Ogee
70,20,2.6,0, 60, 60, , , .95, 0, 0,0,,
     4.8   16.76   21.58   31.74   43.21   52.89   60.06   75.48  119.89  238.62
  254.38  264.33  291.19  312.11  316.25  387.05  393.47  475.57  497.98  527.47
  606.78     630     650  684.08  890.05  914.38  919.96  927.06  928.05   946.7
  953.74  971.45  977.44   990.8  997.64 1010.96 1022.96 1035.75 1047.71 1080.46
 1115.41 1143.02 1217.84  1251.6 1290.29 1301.31 1325.52 1332.84 1339.14 1344.13
 1346.17 1352.49 1356.34 1360.58 1439.03 1454.08 1583.46 1623.29 1634.82    1696
  243.79  243.13  242.21  242.71  242.02  242.91  241.49  241.68   240.2  238.26
  237.07  237.32  236.04  236.47  235.43  234.62  233.88  231.92  232.18     231
     231     231     231     231  231.13  231.99   230.9  230.58  232.34  231.35
  232.65   231.8  232.94  232.41  233.36  233.08  233.98  233.37   234.4  234.43
   235.9  235.73  238.45  238.62  240.75  240.33  240.98   242.1  241.32  242.42
  241.62  241.74  242.91  241.81  244.51  244.14  246.68  246.82  247.63  247.99
                                                                                
                                                                                
             229     229
                                                                                
                                                                                
                                                                                
    1.81    81.8   84.62   88.43   96.97  100.38  110.33  137.19  158.11  162.25
  233.05  239.47  321.57  343.98  373.47  452.78     476     496  530.08  736.05
  760.38  765.96  773.06  774.05   792.7  799.74  817.45  823.44   836.8  843.64
  856.96  868.96  881.75  893.71  926.46  961.41  989.02 1063.84  1097.6 1136.29
 1147.31 1171.52 1178.84 1185.14 1190.13 1192.17 1198.49 1202.34 1206.58 1219.39
 1243.33 1246.69 1249.47 1279.96 1285.03 1300.08 1429.46 1469.29 1480.82    1542
  239.58  237.85  238.26  237.59  237.79  237.07  237.32  236.04  236.47  235.43
  234.62  233.88  231.92  232.18     231     231     231     231     231  231.13
  231.99   230.9  230.58  232.34  231.35  232.65   231.8  232.94  232.41  233.36
  233.08  233.98  233.37   234.4  234.43   235.9  235.73  238.45  238.62  240.75
  240.33  240.98   242.1  241.32  242.42  241.62  241.74  242.91  241.81  242.56
   242.7  243.52  242.92  243.88  244.51  244.14  246.68  246.82  247.63  247.99
                                                                                
                                                     229     229
                                                                                
                                                                                
                                                                                
                                                                                
BR Coef=-1 , 1 , 0 ,, 0 ,,,.8,0,1.2,1,
WSPro=,,,, 1 ,,,, 0 ,,,, 0 ,,,,-1 ,-1 ,-1 , 0 , 0 , 0 , 0 , 0
BC Design=,, 0 ,, 0 ,,,,,,

Type RM Length L Ch R = 1 ,26048.59,601.22,632.98,684.53
XS GIS Cut Line= 3
     1921973.217       435975.37     1921561.087      435425.864
     1921479.679      435313.927
#Sta/Elev= 30
       0  241.51   53.12  240.05  139.68  239.39  227.61  237.53  247.76  236.63
  285.45  233.61  294.07  233.55   309.3   231.5  321.16  230.79  322.76  230.53
  326.17  228.26  331.25  226.24  344.33  226.74   369.9  224.81  424.27  224.74
  432.17  225.15  440.15  224.04  458.56  224.85  476.31   224.7  485.37  223.74
  494.33  223.84   513.8  224.45  604.36  222.68  646.26  223.58     656  226.05
  670.81  226.65  684.44  228.09  777.55  234.53  806.02  235.45  825.29  235.15
#Mann= 3 , 0 , 0
       0     .13       0  476.31     .05       0  494.33    .125       0
#XS Ineff= 2 , 0
       0     476     231     496       0     231
Permanent Ineff=
       F       F
Bank Sta=476.31,494.33
XS Rating Curve= 0
Exp/Cntr=.5,.3

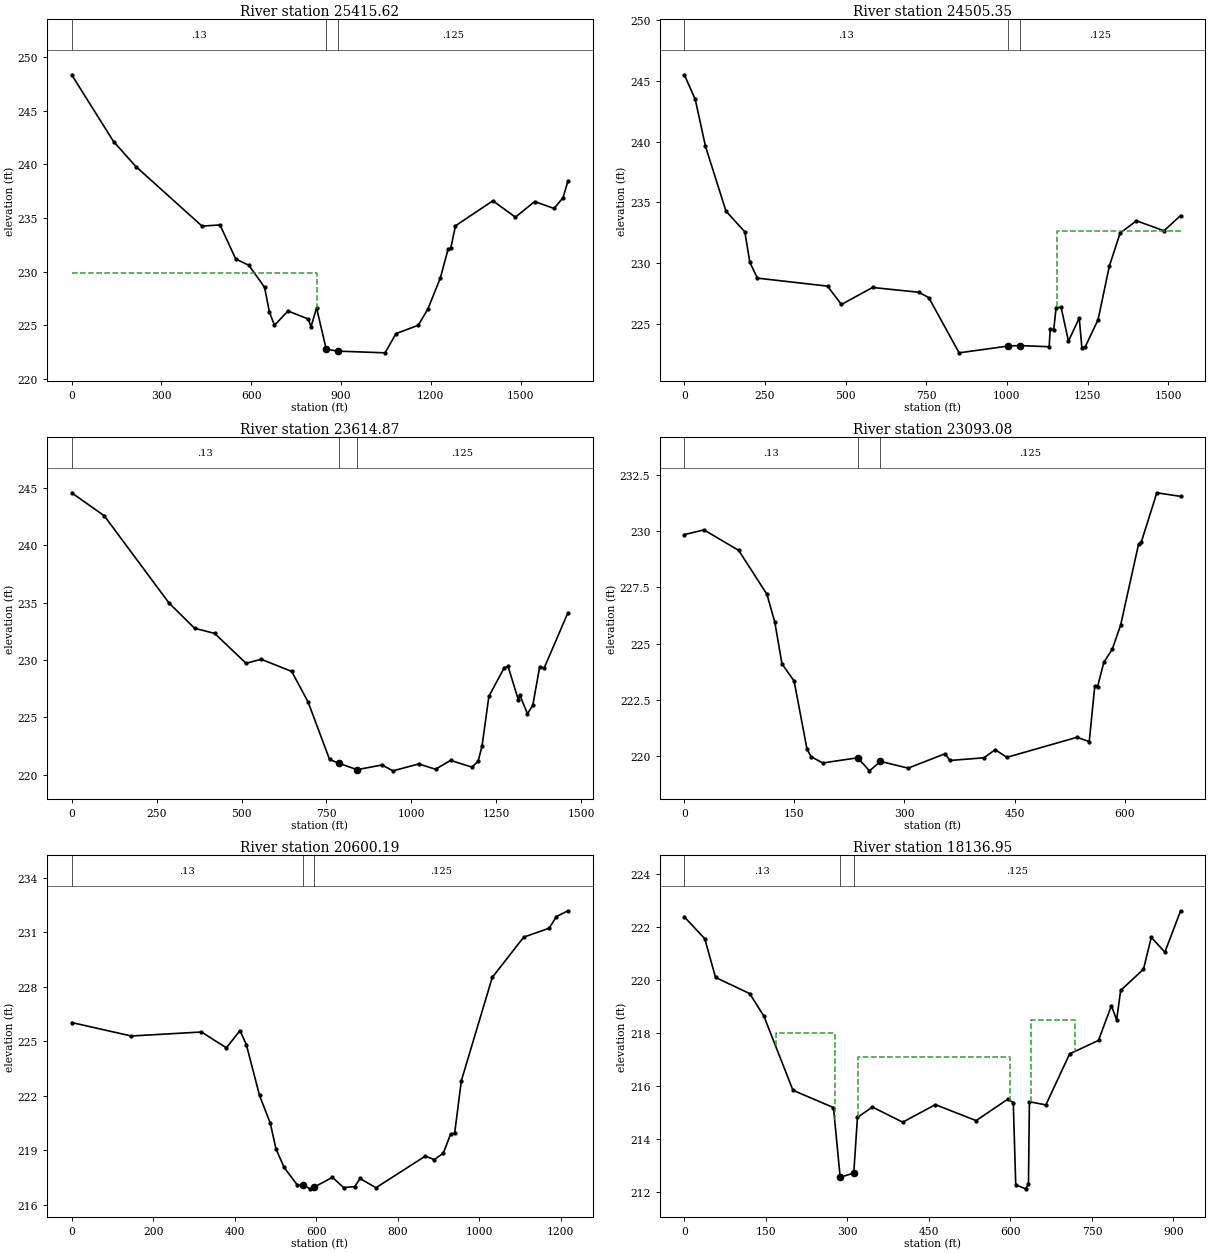
Type RM Length L Ch R = 1 ,25415.62,898.07,910.27,916.81
XS GIS Cut Line= 3
     1922403.374      435877.468      1921959.97      434873.129
     1921682.174      434386.987
#Sta/Elev= 30
       0  248.34  139.93  242.12  214.48  239.79   435.5  234.24  495.46  234.35
  548.18  231.17  591.97  230.59  644.32  228.54  660.68  226.22  677.55     225
  722.67  226.33  791.06  225.57  799.54  224.85  818.06  226.62  850.44  222.76
  889.17  222.59 1046.87  222.43 1083.49  224.22 1157.78     225  1189.9  226.51
 1231.77  229.42  1257.4  232.08 1266.72  232.23 1282.19  234.27 1407.11   236.6
 1482.29  235.07  1546.8  236.53 1611.39  235.88 1641.53  236.89 1657.78  238.44
#Mann= 3 , 0 , 0
       0     .13       0  850.44     .05       0  889.17    .125       0
#XS Ineff= 2 , 0
          818.96  229.85
Permanent Ineff=
       F       F
Bank Sta=850.44,889.17
XS Rating Curve= 0
Exp/Cntr=.3,.1

Type RM Length L Ch R = 1 ,24505.35,931.51,890.48,737.89
XS GIS Cut Line= 6
     1922807.653      435665.001     1922873.798      435466.568
     1922858.533      434856.005     1922787.301      434403.171
     1922772.037       434326.85     1922665.189      434179.298
#Sta/Elev= 30
       0   245.5   33.81  243.47   65.39  239.62  129.01  234.28  187.47  232.57
  203.05  230.05  226.51  228.76  443.97   228.1  486.84  226.59  583.35  227.99
  726.02   227.6  757.55  227.16  851.78  222.61 1004.39  223.17 1040.59  223.21
 1130.86  223.11 1134.39  224.61 1144.88  224.49 1152.48  226.34 1167.95  226.35
 1190.73  223.57 1224.06  225.48  1232.3  223.03 1242.56   223.1 1282.42  225.33
 1317.67  229.77 1350.88  232.47 1401.53  233.48 1486.87  232.66 1538.33  233.91
#Mann= 3 , 0 , 0
       0     .13       0 1004.39     .05       0 1040.59    .125       0
#XS Ineff= 2 , 0
                          1156.4           232.6
Permanent Ineff=
       F       F
Bank Sta=1004.39,1040.59
XS Rating Curve= 0
Exp/Cntr=.3,.1

Type RM Length L Ch R = 1 ,23614.87,488.33,521.79,490.59
XS GIS Cut Line= 4
     1924059.465      434691.494     1923765.643      434429.724
     1923071.153      433991.662     1922852.122      433879.475
#Sta/Elev= 30
       0  244.55   95.84  242.55  286.19  234.97  361.67  232.76  420.91  232.31
  513.35  229.71  557.91  230.06  647.66     229  695.76  226.35  759.18  221.34
  787.48     221  839.93  220.45  913.35  220.86  945.64  220.35 1021.62  220.95
 1071.03  220.49  1115.4  221.26 1178.44  220.67 1196.35  221.19 1207.78  222.48
 1228.12  226.84 1273.48  229.33  1284.5  229.44 1314.92  226.52 1319.05  226.96
 1341.59  225.31 1357.32  226.05 1377.41  229.38 1391.02  229.31 1460.71  234.11
#Mann= 3 , 0 , 0
       0     .13       0  787.48     .05       0  839.93    .125       0
Bank Sta=787.48,839.93
XS Rating Curve= 0
Exp/Cntr=.3,.1

Type RM Length L Ch R = 1 ,23093.08,2426.71,2492.89,2409.56
XS GIS Cut Line= 4
     1923626.825      433848.576     1923509.801      433751.904
     1923173.991      433533.118     1923051.878      433512.766
#Sta/Elev= 30
       0  229.85   26.71  230.06   74.05  229.15  112.51   227.2  123.28  225.96
  133.03  224.11  149.64  223.34  167.18  220.31  172.79  219.98  188.63   219.7
  236.25  219.93  252.35  219.35  267.26  219.77  305.03  219.47  355.32  220.11
  361.83  219.81  408.29  219.93   423.7  220.29  439.57  219.95  535.01  220.84
  551.85  220.65  559.39  223.12  563.19  223.09  571.72  224.17  583.25  224.76
  594.66  225.83  619.05  229.42  622.81  229.52  643.99  231.71  676.38  231.55
#Mann= 3 , 0 , 0
       0     .13       0  236.25     .05       0  267.26    .125       0
Bank Sta=236.25,267.26
XS Rating Curve= 0
Exp/Cntr=.3,.1

Type RM Length L Ch R = 1 ,20600.19,2397.17,2463.25,2540.29
XS GIS Cut Line= 4
      1925366.93       432291.64     1924975.152      431950.743
     1924603.726      431742.134     1924344.237      431660.725
#Sta/Elev= 30
       0  226.04  146.29   225.3  318.36  225.52  379.51  224.65  413.02   225.6
  428.65  224.81  460.78  222.03  487.12  220.51  501.13  219.09  521.09  218.07
  553.45   217.1  566.74   217.1  585.55  216.89  594.25  216.98  639.64  217.52
  667.08  216.96  694.29  217.01  707.38  217.46   746.4  216.95  867.46  218.69
  889.63   218.5  911.56  218.85   929.8  219.92  939.43  219.94  955.88  222.84
 1031.65  228.52 1108.83  230.74 1171.23  231.23 1189.04  231.87 1217.29  232.19
#Mann= 3 , 0 , 0
       0     .13       0  566.74     .05       0  594.25    .125       0
Bank Sta=566.74,594.25
XS Rating Curve= 0
Exp/Cntr=.5,.3

Type RM Length L Ch R = 1 ,18136.95,151.32,157.57,158.7
XS GIS Cut Line= 4
     1927025.626      430958.578     1926964.569      430744.881
     1926664.376      430368.367     1926476.119      430276.783
#Sta/Elev= 30
       0  222.37    37.5  221.55   57.41  220.09  120.33  219.48  146.44  218.63
  199.86  215.84  274.43  215.19  286.69  212.57  311.72  212.72  318.52  214.82
  346.02  215.21   401.8  214.64  461.93   215.3  536.81   214.7  594.76   215.5
  605.24  215.38  609.78  212.28  627.99  212.13   633.2  212.31  634.93  215.41
   665.2  215.29  708.91  217.21  762.09  217.72  785.81  219.03  795.43  218.49
  802.82   219.6   844.8   220.4  859.22   221.6   884.2  221.04  913.14   222.6
#Mann= 3 , 0 , 0
       0     .13       0  286.69     .05       0  311.72    .125       0
#XS Ineff= 3 ,-1
  168.25  277.25     218  319.91  599.53   217.1  637.44  718.01   218.5
Permanent Ineff=
       F       F       F
Bank Sta=286.69,311.72
XS Rating Curve= 0
Exp/Cntr=.5,.3

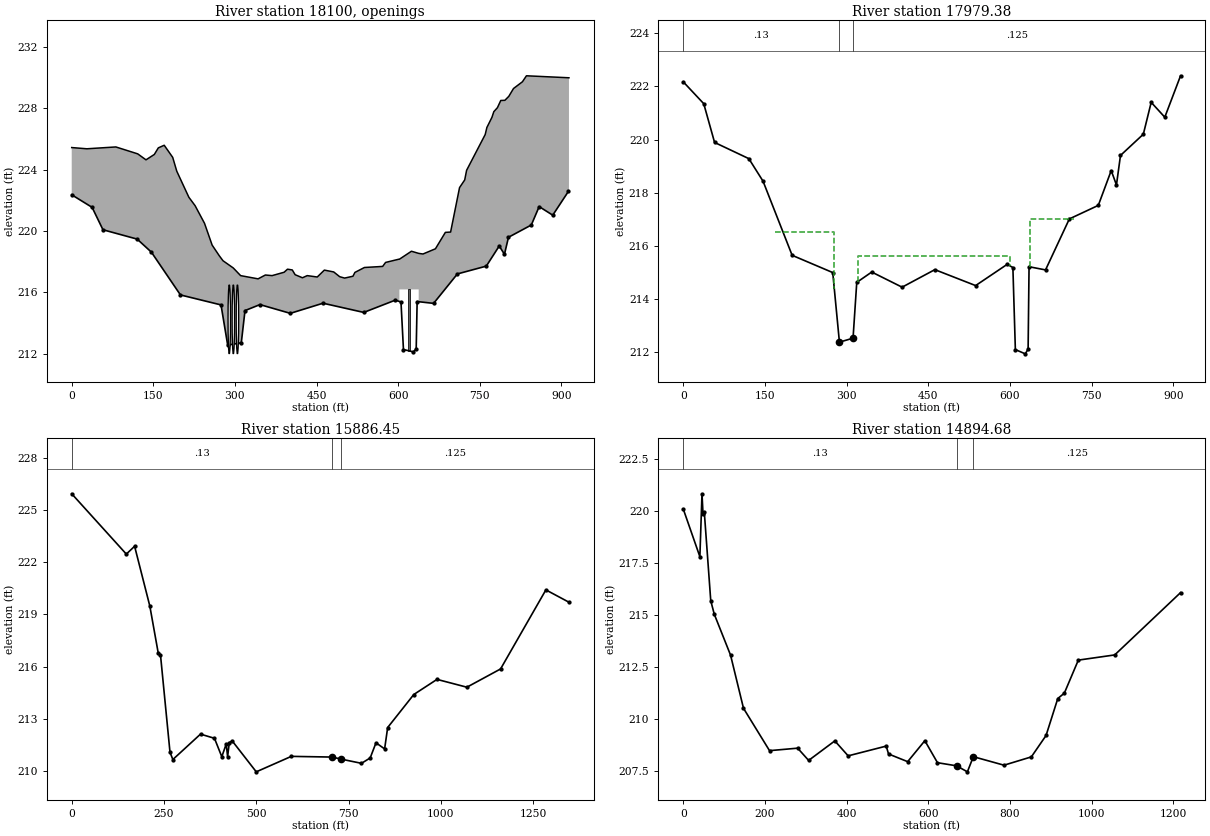
Type RM Length L Ch R = 4 ,18100   ,,,
BEGIN DESCRIPTION:
SR1116; NCDOT structure 23 and Small pipes 46 2030, 46 2031, and 46 2032
END DESCRIPTION:
Bridge Culvert--1,0,-1,-1, 0
Deck Dist Width WeirC Skew NumUp NumDn MinLoCord MaxHiCord MaxSubmerge Is_Ogee
72,29,2.6,0, 60, 60, , , .95, 0, 1.5,1.5,,
       0   27.78   81.15  121.29  136.51  151.82   159.2  170.02  185.65  193.11
  215.34  226.81  244.12  258.13  271.16  278.09  296.93  310.45  342.55  355.96
  368.27  390.39  396.64  405.42  410.66  424.08   432.9  451.29  464.38   481.6
  492.55  501.61  516.94  520.56  538.03  571.52  576.91  601.26  602.34  624.46
   637.8  645.68  668.56   686.8  696.43  712.88  722.36  725.87  760.03  763.13
   772.4  775.88  782.49  788.65  796.17  803.42  812.06  828.47  835.85     914
  225.45  225.37  225.49  225.04  224.65     225  225.43   225.6  224.81  223.91
  222.21  221.66  220.51  219.09   218.4  218.07   217.6   217.1  216.89  217.14
   217.1  217.32  217.52  217.47  217.16  216.96   217.1  217.01  217.46  217.34
  217.03  216.94  217.06  217.31  217.63   217.7  217.96  218.17  218.17  218.69
  218.55  218.51  218.85  219.92  219.94  222.84  223.34  223.97   226.3  226.76
  227.42  227.79  228.05  228.52  228.53  228.79   229.3  229.74  230.13     230
                                                                                
                                                                                
                                                                                
                                                                   216.2   216.2
   216.2
                                                                                
       0   27.78   81.15  121.29  136.51  151.82   159.2  170.02  185.65  193.11
  215.34  226.81  244.12  258.13  271.16  278.09  296.93  310.45  342.55  355.96
  368.27  390.39  396.64  405.42  410.66  424.08   432.9  451.29  464.38   481.6
  492.55  501.61  516.94  520.56  538.03  571.52  576.91  601.26  602.34  624.46
   637.8  645.68  668.56   686.8  696.43  712.88  722.36  725.87  760.03  763.13
   772.4  775.88  782.49  788.65  796.17  803.42  812.06  828.47  835.85     933
  225.45  225.37  225.49  225.04  224.65     225  225.43   225.6  224.81  223.91
  222.21  221.66  220.51  219.09   218.4  218.07   217.6   217.1  216.89  217.14
   217.1  217.32  217.52  217.47  217.16  216.96   217.1  217.01  217.46  217.34
  217.03  216.94  217.06  217.31  217.63   217.7  217.96  218.17  218.17  218.69
  218.55  218.51  218.85  219.92  219.94  222.84  223.34  223.97   226.3  226.76
  227.42  227.79  228.05  228.52  228.53  228.79   229.3  229.74  230.13     230
                                                                                
                                                                                
                                                                                
                                                                   216.2   216.2
   216.2
                                                                                
Pier Skew, UpSta & Num, DnSta & Num=  ,620, 2 ,620, 2 , 0 , 0 , 0 ,,
       2       2
     200   216.2
       2       2
     200   216.2
BR Coef=-1 , 1 , 0 ,, 0 ,,.31,.8,0,1.2,1,
WSPro=,,,, 1 ,,,, 0 ,,,, 0 ,,,,-1 ,-1 ,-1 , 0 , 0 , 0 , 0 , 0
Multiple Barrel Culv=1,4.5,,29,.028,.5,1,1,1,212,211.8, 3,Culvert #1  , 0 ,72
   289.6   289.6   297.1   297.1   304.6   304.6
Culvert Bottom n=.028
BC Mult= 2 ,0,500,0,500
BC Mult= 3 ,450,914,450,914
BC Design=,, 0 ,, 0 ,,,,,,

Type RM Length L Ch R = 1 ,17979.38,2034.03,2092.93,2199.36
XS GIS Cut Line= 5
     1927198.618      430917.874     1927076.506       430643.12
     1926995.097      430510.832     1926827.193      430332.751
     1926684.728      430149.582
#Sta/Elev= 30
       0  222.17    37.5  221.35   57.41  219.89  120.33  219.28  146.44  218.43
  199.86  215.64  274.43  214.99  286.69  212.37  311.72  212.52  318.52  214.62
  346.02  215.01   401.8  214.44  461.93   215.1  536.81   214.5  594.76   215.3
  605.24  215.18  609.78  212.09  627.99  211.93   633.2  212.11  634.93  215.21
   665.2  215.09  708.91  217.01  762.09  217.52  785.81  218.83  795.43  218.29
  802.82   219.4   844.8   220.2  859.22   221.4   884.2  220.84  913.14   222.4
#Mann= 3 , 0 , 0
       0     .13       0  286.69     .05       0  311.72    .125       0
#XS Ineff= 3 ,-1
  168.25  277.25   216.5  319.91  599.53   215.6  637.44  718.01     217
Permanent Ineff=
       F       F       F
Bank Sta=286.69,311.72
XS Rating Curve= 0
Exp/Cntr=.5,.3

Type RM Length L Ch R = 1 ,15886.45,1033.71,991.77,864.57
XS GIS Cut Line= 5
     1928892.931      430597.328     1928938.723      430337.839
     1928928.547      429681.484     1928887.843      429452.523
     1928780.994      429289.706
#Sta/Elev= 30
       0  225.94  147.94  222.47   170.4  222.92  211.63  219.48  234.28  216.79
  240.51  216.67  266.32  211.06  274.06  210.65  348.97  212.11  386.77  211.87
  406.61  210.81  418.65  211.54  422.37  210.81  426.92  211.62   434.8  211.72
     500  209.94     595  210.83  705.93  210.79  730.19  210.67  785.13  210.43
  808.68  210.74  824.38  211.61  847.79  211.26  856.02  212.49  926.85  214.39
  989.72  215.26 1070.65  214.81 1161.91  215.86 1284.71  220.41 1347.23   219.7
#Mann= 3 , 0 , 0
       0     .13       0  705.93     .05       0  730.19    .125       0
Bank Sta=705.93,730.19
XS Rating Curve= 0
Exp/Cntr=.3,.1

Type RM Length L Ch R = 1 ,14894.68,0,0,0
BEGIN DESCRIPTION:
cp raft1
END DESCRIPTION:
XS GIS Cut Line= 4
     1930007.208      430124.142     1929986.856      429951.149
     1929620.518       429330.41     1929350.853      429152.329
#Sta/Elev= 30
       0  220.09   40.59   217.8   45.77  220.83   48.29  219.86   51.46  219.94
   67.23  215.68   75.87  215.03  115.75  213.06  147.44   210.5  211.22  208.46
  280.12  208.58  307.04  207.99  371.17  208.93  403.83  208.21  497.07  208.68
  502.76   208.3  549.63  207.93   591.7  208.94  622.65  207.88   669.5  207.73
  695.93  207.44  710.51  208.17  785.63  207.76  852.58  208.16  888.63  209.19
  917.37  210.97  933.44  211.23  967.69  212.82 1056.85  213.07 1218.12  216.07
#Mann= 3 , 0 , 0
       0     .13       0   669.5     .05       0  710.51    .125       0
Bank Sta=669.5,710.51
XS Rating Curve= 0
Exp/Cntr=.3,.1

River Reach=Raft Swamp      ,three
Reach XY= 30
      1930208.59      428992.227      1930413.15       428812.02
      1930508.38        428602.5      1930527.43       428469.18
      1930451.24       428012.06      1930441.72       427707.31
      1930470.29       427278.76      1930489.34         427174.
      1930594.09       427040.67      1930889.32       426412.13
      1930889.32       426250.23      1930965.51       425983.58
       1931003.6       425745.49      1930975.03       425155.04
      1930879.79       424945.53      1930784.56        424850.3
      1930765.51       424726.49      1930898.84       424383.65
      1930860.75       424231.28      1930970.27       423993.19
      1930970.27       423907.48      1931055.98       423583.69
      1931170.26        423383.7       1931189.3       423193.23
      1931122.64       423117.04      1931132.16       423031.33
      1931246.44       422698.02      1931255.97       422507.55
      1931360.73       422212.32      1931381.15       421997.83