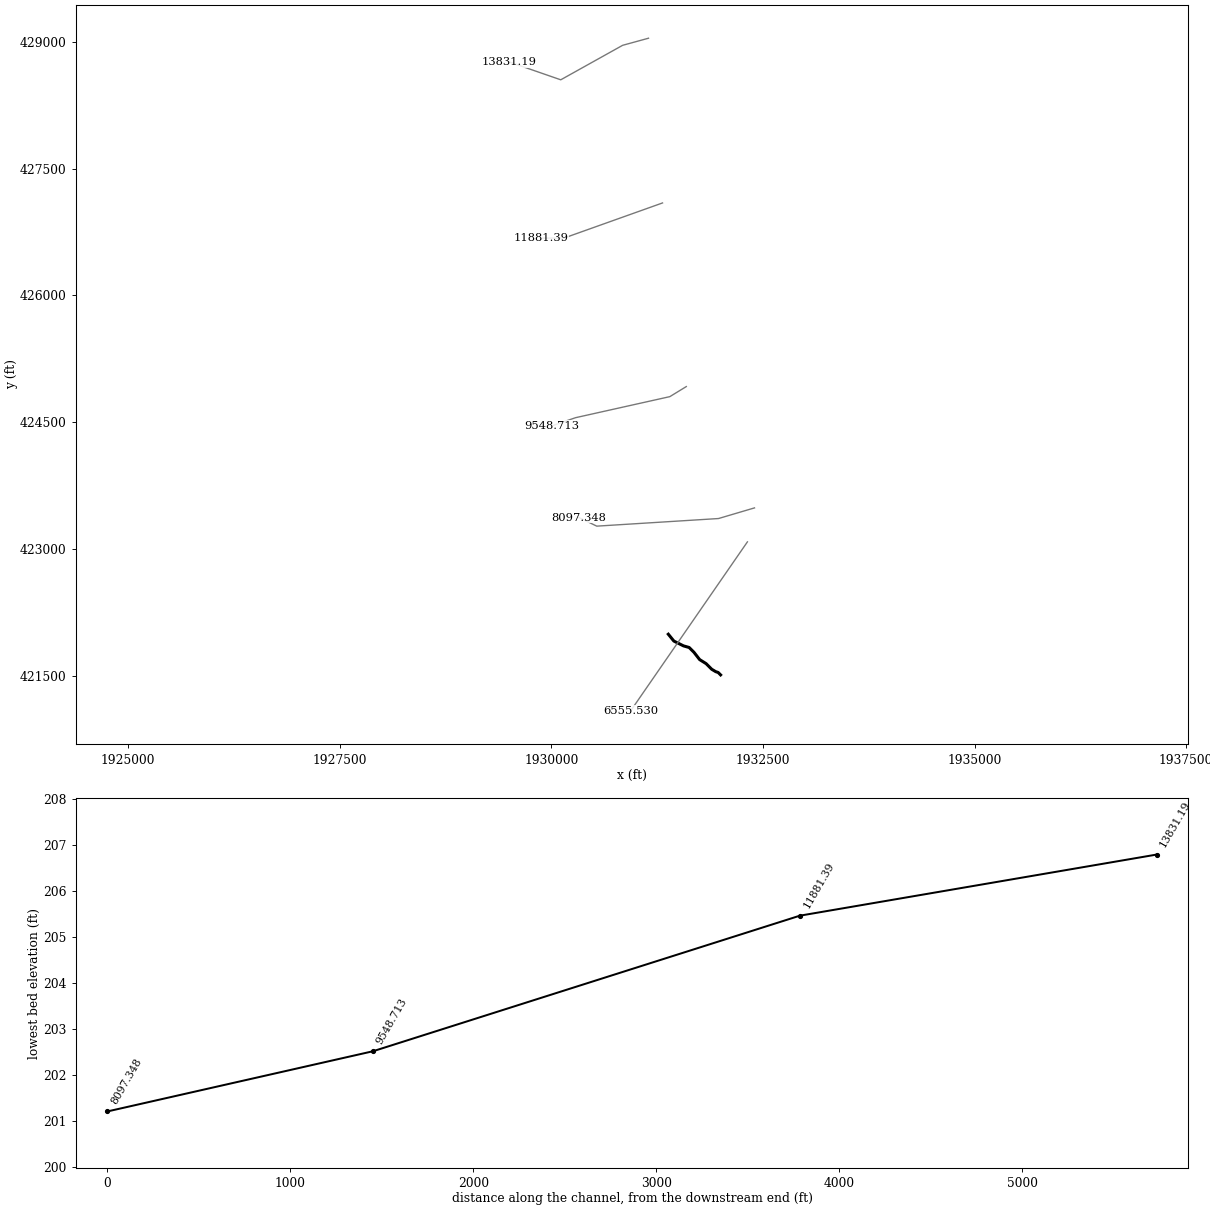
HEC-RAS study upraft.prj: Upper Raft Swamp

--- upraft.g04 (geometry) --- (continued)

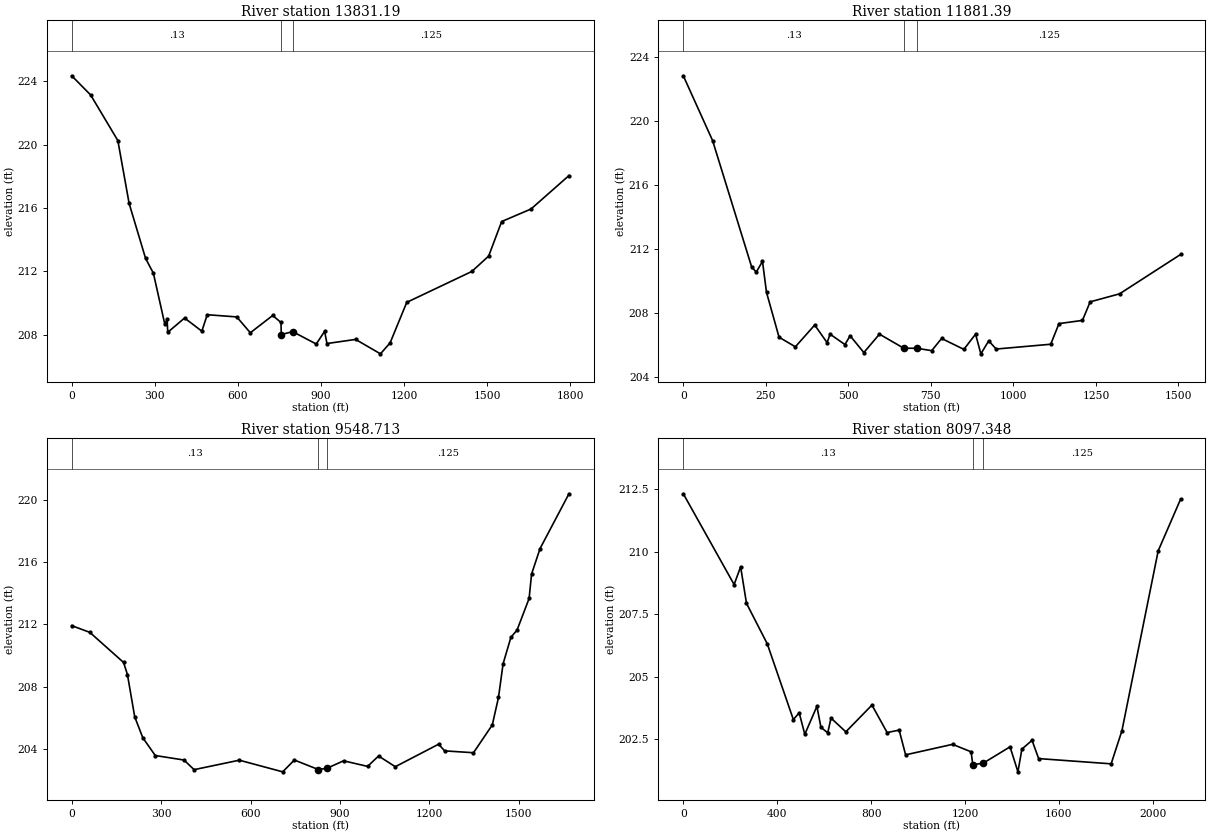
Type RM Length L Ch R = 1 ,13831.19,1962.32,1949.8,1935.41
XS GIS Cut Line= 4
     1931147.093      429040.014      1930841.45      428956.112
     1930110.305      428548.589     1929505.013      428758.343
#Sta/Elev= 30
       0  224.34   68.25  223.13  166.52  220.25  207.22  216.28  266.65  212.81
  294.73  211.88  335.85  208.67  344.29  208.96  346.57  208.15  407.26  209.05
  469.67  208.22  489.06  209.26  595.63  209.12  644.62  208.12  725.22  209.21
  755.21  208.77  756.41  208.01  797.63  208.19  882.48  207.41  912.74  208.21
  921.16  207.44 1024.54   207.7 1114.28  206.79 1149.04  207.48 1209.21  210.04
 1444.07  211.99 1504.71  212.96 1551.73  215.14 1657.55  215.93  1794.6  218.04
#Mann= 3 , 0 , 0
       0     .13       0  756.41     .05       0  797.63    .125       0
Bank Sta=756.41,797.63
XS Rating Curve= 0
Exp/Cntr=.3,.1

Type RM Length L Ch R = 1 ,11881.39,2265.21,2332.68,2185.89
XS GIS Cut Line= 3
       1931312.9      427093.597     1930148.039      426678.345
     1929878.396      426678.345
#Sta/Elev= 30
       0  222.84   88.72  218.79   207.2  210.88  221.07  210.57  239.87  211.24
  252.04   209.3  290.05   206.5  339.42   205.9  398.06  207.26  435.58  206.16
  444.59  206.69  489.66  206.04  505.28  206.59  546.94  205.54  594.19  206.69
  667.97  205.81  706.67  205.81  752.43  205.66  782.44  206.42  849.87  205.74
  885.37  206.69  901.37  205.46  925.21  206.27  947.76  205.76 1113.06  206.06
 1138.05  207.35 1209.12  207.55  1232.5  208.71  1321.5  209.21 1506.31  211.67
#Mann= 3 , 0 , 0
       0     .13       0  667.97     .05       0  706.67    .125       0
Bank Sta=667.97,706.67
XS Rating Curve= 0
Exp/Cntr=.3,.1

Type RM Length L Ch R = 1 ,9548.713,1455.69,1451.36,1362.2
XS GIS Cut Line= 4
     1931593.753      424923.973     1931398.937      424804.919
     1930284.156      424555.987     1930002.755      424458.579
#Sta/Elev= 30
       0  211.92   60.65  211.49  174.06  209.55  186.94  208.77  211.39  206.05
  238.32  204.71  280.36  203.56  376.68  203.27  410.58  202.65  562.34  203.26
  707.81  202.51  746.98  203.27  827.26  202.66  856.42  202.74  912.17  203.22
  992.68  202.86 1029.52  203.53 1085.62  202.84 1231.04  204.29 1251.07  203.86
 1348.03  203.74 1411.12  205.53  1431.9   207.3 1447.24  209.46 1473.56  211.17
 1494.25  211.64 1534.59  213.67 1542.85  215.24 1571.26  216.88 1668.33  220.41
#Mann= 3 , 0 , 0
       0     .13       0  827.26     .05       0  856.42    .125       0
Bank Sta=827.26,856.42
XS Rating Curve= 0
Exp/Cntr=.3,.1

Type RM Length L Ch R = 1 ,8097.348,0,0,0
BEGIN DESCRIPTION:
cp raft2
END DESCRIPTION:
XS GIS Cut Line= 4
     1932399.629      423490.501     1931974.127      423364.648
     1930535.808      423274.753     1930326.053      423376.634
#Sta/Elev= 30
       0  212.32  216.48  208.69  244.09   209.4  269.12  207.94   357.6  206.32
  468.76  203.29   493.6  203.56  517.54   202.7   569.1  203.82  586.19  202.98
  615.19  202.76  629.11  203.35  692.23   202.8  803.61  203.87  868.24  202.77
  919.35  202.87  946.92  201.88  1147.1   202.3 1225.86     202 1233.13  201.49
 1276.25  201.54 1391.77   202.2 1425.35   201.2 1442.26  202.11 1485.45  202.46
 1513.54  201.73 1822.35  201.52 1868.22  202.84 2022.85  210.04 2118.04   212.1
#Mann= 3 , 0 , 0
       0     .13       0 1233.13     .05       0 1276.25    .125       0
Bank Sta=1233.13,1276.25
XS Rating Curve= 0
Exp/Cntr=.3,.1

River Reach=Raft Swamp      ,four
Reach XY= 30
      1931381.15       421997.83      1931385.71       421992.21
     1931425.634      421942.838      1931427.97       421939.93
      1931446.44        421917.1     1931458.549      421911.035
      1931459.76       421910.44      1931473.56       421903.53
     1931491.564      421894.538     1931493.303      421893.658
      1931497.02       421891.81      1931527.52       421876.55
      1931560.72       421859.96      1931627.38       421840.91
      1931684.52       421783.77      1931697.99       421766.46
      1931698.29       421766.06     1931707.411      421754.328
     1931709.954      421751.075      1931741.59       421710.39
     1931744.513      421706.647      1931751.18       421698.06
      1931804.95       421664.45     1931807.797      421662.686
     1931810.603      421660.918      1931827.37       421650.44
      1931894.03       421583.78      1931941.65       421555.21
      1931970.22       421545.69      1931998.79       421517.12

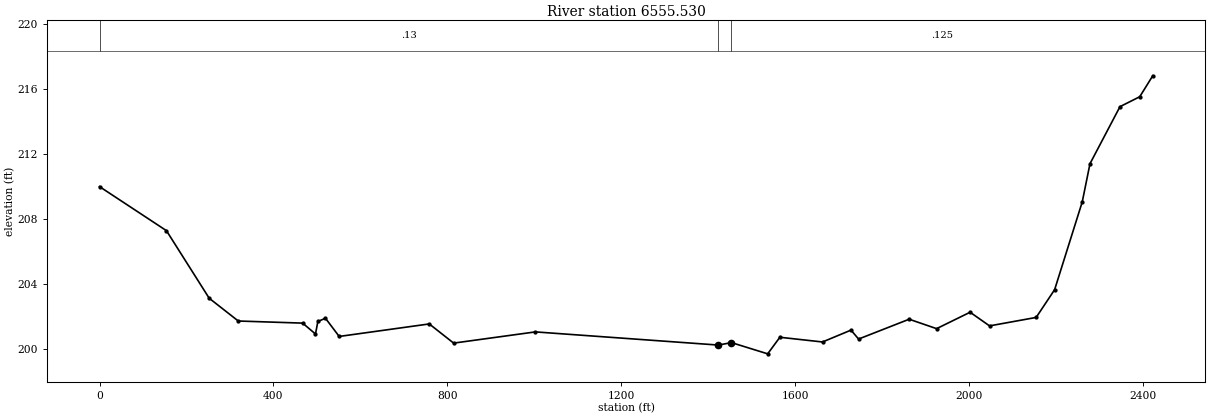
Type RM Length L Ch R = 1 ,6555.530,323.87,333.09,354.64
XS GIS Cut Line= 3
     1932315.727       423088.97     1930949.324      421111.281
     1930943.331      421093.302
#Sta/Elev= 30
       0  209.97  153.91  207.26  252.33   203.1  319.21   201.7  467.28  201.57
   496.8   200.9  502.26  201.67  519.76  201.87   551.3  200.75  758.53  201.52
  814.63  200.34 1002.61  201.03 1423.38  200.22 1453.74  200.37 1536.96  199.68
 1565.02   200.7 1663.09  200.41 1728.66  201.14 1746.07  200.59 1862.44  201.81
 1925.53  201.23 2002.61  202.24 2047.36   201.4 2154.56  201.92 2197.06  203.63
 2260.58  209.03 2278.38  211.38 2347.37  214.89 2392.81   215.5 2422.76  216.79
#Mann= 3 , 0 , 0
       0     .13       0 1423.38     .05       0 1453.74    .125       0
Bank Sta=1423.38,1453.74
XS Rating Curve= 0
Exp/Cntr=.3,.1