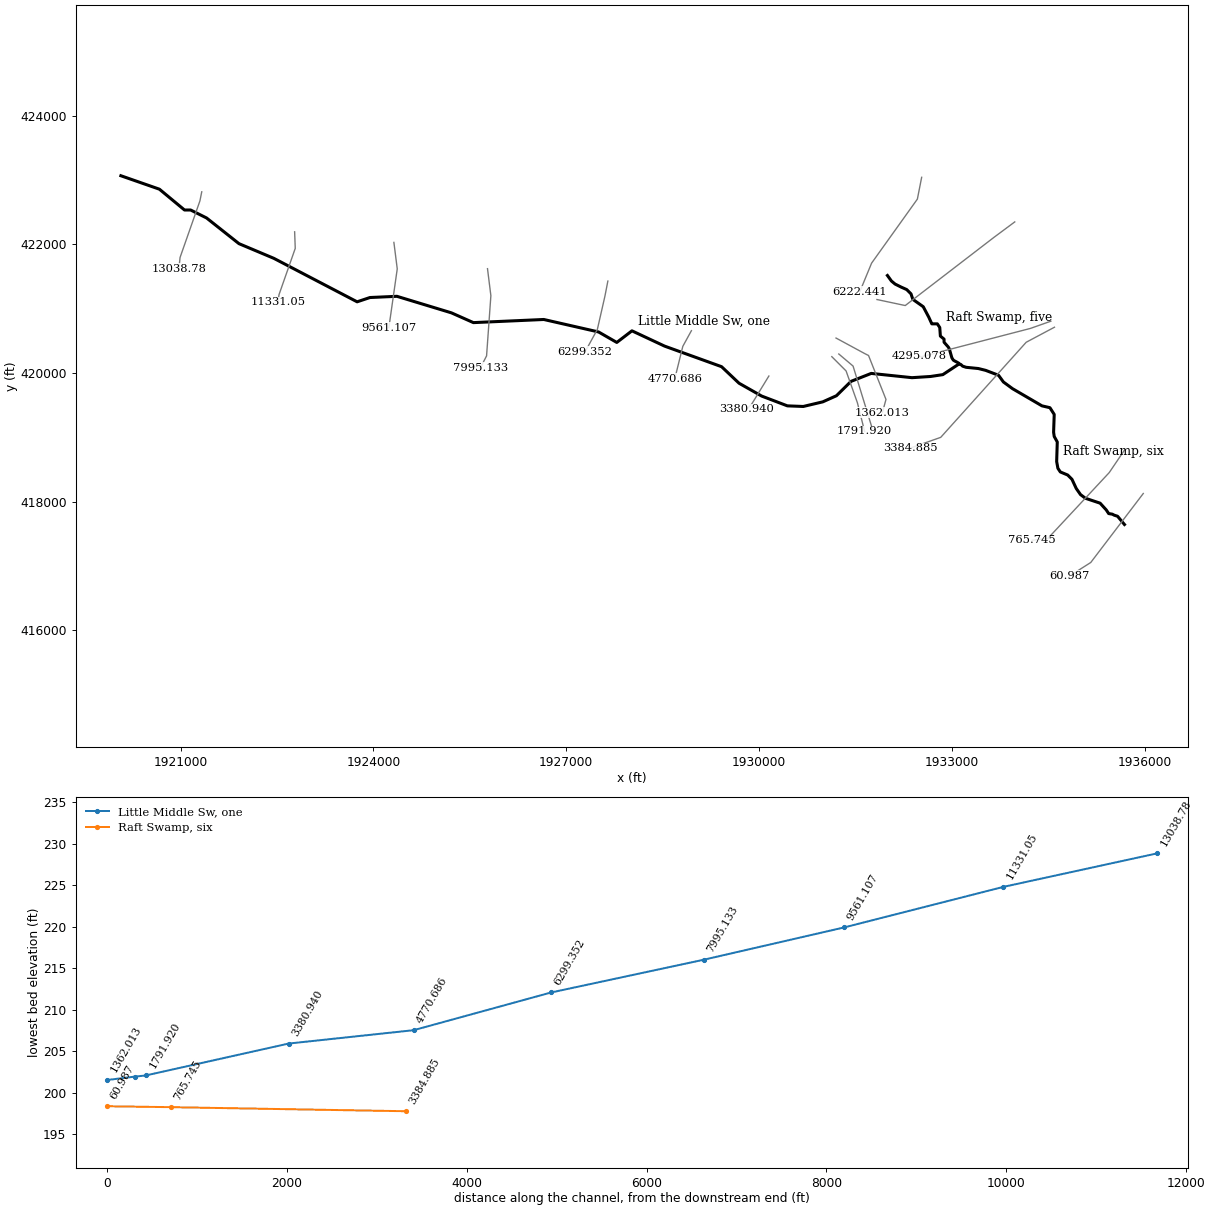
HEC-RAS study upraft.prj: Upper Raft Swamp

--- upraft.g04 (geometry) --- (continued)

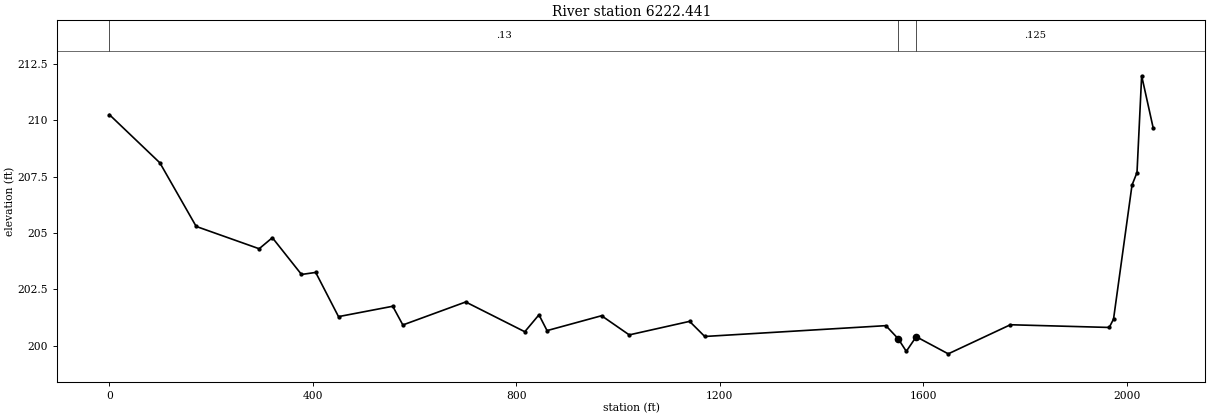
Type RM Length L Ch R = 1 ,6222.441,0,0,0
XS GIS Cut Line= 4
     1932531.283      423044.855     1932464.504      422705.393
     1931752.191      421709.268     1931568.547      421264.072
#Sta/Elev= 30
       0  210.25   99.41  208.11  170.79  205.29  294.58   204.3  320.55  204.79
  377.82  203.16  405.76  203.25  450.58  201.29   557.2  201.75  577.06  200.92
   700.6  201.94  816.79  200.62  844.63  201.37  860.53  200.67  967.69  201.33
 1022.11  200.48 1140.74  201.08 1170.52  200.41 1526.61  200.89 1550.81  200.31
 1566.76  199.75 1586.26   200.4 1649.21  199.64 1771.39  200.93  1965.7  200.81
 1974.14  201.18 2010.45  207.12 2020.28  207.68 2029.42  211.97 2052.16  209.65
#Mann= 3 , 0 , 0
       0     .13       0 1550.81     .05       0 1586.26    .125       0
Bank Sta=1550.81,1586.26
XS Rating Curve= 0
Exp/Cntr=.3,.1

River Reach=Raft Swamp      ,five
Reach XY= 30
      1931998.79       421517.12      1932060.69       421431.41
      1932117.83       421383.79      1932213.07       421336.17
      1932298.78       421298.08      1932365.44       421231.42
      1932394.01       421145.71      1932549.94       421035.63
      1932555.91       421031.43      1932590.65       420965.79
      1932641.62       420869.53     1932678.191      420789.078
     1932681.171      420782.499      1932689.24       420764.77
      1932774.95       420764.77      1932813.04       420707.63
      1932822.56        420574.3       1932879.7       420526.69
       1932879.7       420479.07      1932946.37       420402.88
      1932962.42       420373.99     1932974.296      420331.086
      1933001.32       420236.52      1933001.44       420235.16
      1933024.37        420199.9      1933051.12       420183.85
     1933076.945      420170.933      1933104.07      420154.621
     1933109.776      420146.557      1933113.06      420140.871

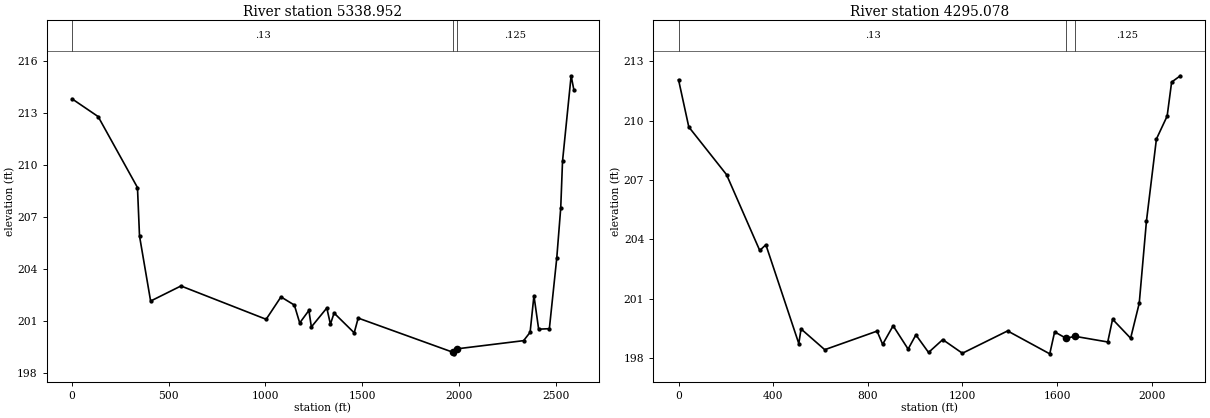
Type RM Length L Ch R = 1 ,5338.952,1037.37,1043.87,916.96
XS GIS Cut Line= 4
     1933980.094      422351.082     1933652.353      422107.617
     1932275.836      421049.479     1931835.726      421143.119
#Sta/Elev= 30
       0   213.8  134.74  212.78  338.17  208.69  348.71   205.9  406.13  202.15
  562.97  203.02 1003.44   201.1 1080.08  202.39  1149.3  201.92 1177.02  200.89
 1224.45  201.61 1237.27  200.66 1317.08  201.75 1335.81  200.82 1354.72  201.46
 1458.77  200.32 1479.31  201.17 1969.33   199.2 1976.66  199.11  1991.5   199.4
 2334.64  199.87 2368.21  200.35 2388.07  202.46 2412.44  200.53  2467.8  200.56
 2506.07  204.63  2526.6  207.52 2535.86  210.21 2580.34  215.13 2594.46  214.32
#Mann= 3 , 0 , 0
       0     .13       0 1969.33     .05       0  1991.5    .125       0
Bank Sta=1969.33,1991.5
XS Rating Curve= 0
Exp/Cntr=.3,.1

Type RM Length L Ch R = 1 ,4295.078,0,0,0
BEGIN DESCRIPTION:
cp raft3
END DESCRIPTION:
XS GIS Cut Line= 4
     1934541.938      420806.013      1934223.56      420693.645
     1932528.666      420253.534 1932496.5037136  420258.6799672
#Sta/Elev= 30
       0  212.07   43.37  209.68  202.78  207.27  343.29  203.43  369.21  203.72
  508.41  198.72   517.9  199.46  618.09  198.41  839.28  199.35  862.84  198.68
  907.17  199.62  970.54  198.44 1003.39  199.16 1056.94  198.27 1116.87  198.92
 1200.03  198.23 1391.06  199.36 1569.31   198.2 1589.93  199.31 1639.54  198.98
 1674.25  199.09 1814.47   198.8 1834.89  199.95 1911.18  198.99 1947.58  200.76
 1978.11  204.92 2020.24  209.07 2065.57  210.23 2084.54  211.95  2121.3  212.27
#Mann= 3 , 0 , 0
       0     .13       0 1639.54     .05       0 1674.25    .125       0
Bank Sta=1639.54,1674.25
XS Rating Curve= 0
Exp/Cntr=.3,.1

River Reach=Little Middle Sw,one
Reach XY= 30
      1920070.76       423069.43      1920670.74       422859.91
       1921061.2       422536.12      1921156.43       422536.12
      1921404.04       422412.31      1921908.78       422012.33
      1922451.61       421783.77      1923746.79       421107.61
      1923946.78       421174.28      1924365.81       421193.32
      1925213.39       420936.19      1925556.23       420783.82
      1926651.46       420832.61     1927504.235      420638.315
     1927787.365      420475.301     1928023.307      420656.088
      1928531.49      420418.156      1929417.96       420098.14
      1929689.37         419841.      1930041.74       419641.01
      1930441.72       419488.64      1930689.33       419479.12
      1930992.87       419551.01     1931205.204      419646.183
      1931432.15       419869.57      1931746.42       419993.38
     1932380.904      419927.173      1932670.19       419945.76
      1932860.66       419974.33      1933113.06      420140.871

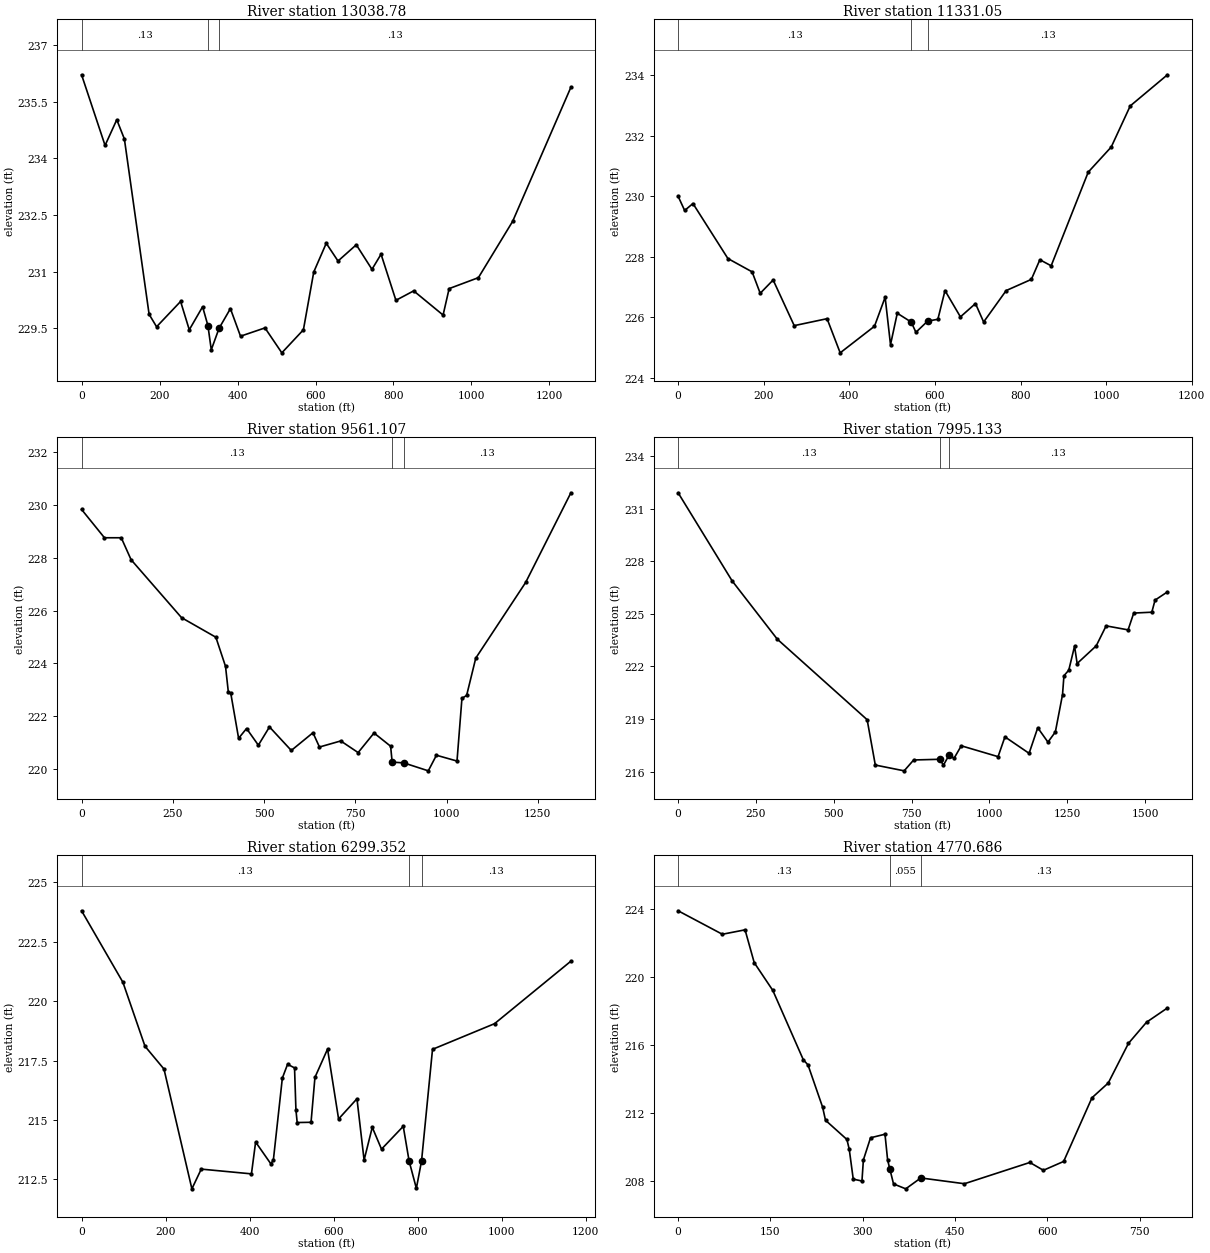
Type RM Length L Ch R = 1 ,13038.78,1679.94,1707.73,1691.82
XS GIS Cut Line= 4
     1921329.256      422819.285     1921301.164      422678.824
      1920992.15      421798.603     1920973.422      421620.686
#Sta/Elev= 30
       0  236.21   60.26  234.34    90.3  235.02  109.83  234.51  173.22  229.87
  192.39  229.54  253.97  230.21  276.26  229.46  310.43  230.07  324.08  229.57
  332.67  228.93  352.65   229.5  381.74  230.02  407.64  229.29  470.38  229.51
  513.61  228.85  568.96  229.46  595.51  230.99  627.55  231.75  657.73  231.28
  704.61  231.71   744.8  231.06  768.12  231.46  806.23  230.24   851.8  230.49
  927.21  229.85  942.71  230.55 1017.78  230.84  1105.6  232.33 1255.03  235.88
#Mann= 3 , 0 , 0
       0     .13       0  324.08    .055       0  352.65     .13       0
Bank Sta=324.08,352.65
XS Rating Curve= 0
Exp/Cntr=.3,.1

Type RM Length L Ch R = 1 ,11331.05,1711.53,1769.94,1773.48
XS GIS Cut Line= 4
     1922774.656      422196.945     1922784.213      421938.904
      1922530.95      421217.344     1922516.615       421097.88
#Sta/Elev= 30
       0     230   15.28  229.53   34.67  229.76  116.34  227.94  172.85   227.5
  191.81  226.79  222.03  227.23  271.27  225.72  348.01  225.95  378.66  224.82
  458.82   225.7   483.7  226.66  496.23  225.09  512.04  226.13   544.5  225.84
  555.62   225.5  583.01  225.87  606.87  225.93  623.56  226.88  659.58  226.01
  694.75  226.45  713.83  225.84  766.44  226.88  825.31  227.25  845.21   227.9
  871.58   227.7  958.22   230.8 1011.94  231.63 1056.35  232.99 1143.26  234.02
#Mann= 3 , 0 , 0
       0     .13       0   544.5    .055       0  583.01     .13       0
Bank Sta=544.5,583.01
XS Rating Curve= 0
Exp/Cntr=.3,.1

Type RM Length L Ch R = 1 ,9561.107,1546.6,1565.97,1572.4
XS GIS Cut Line= 3
     1924319.089      422032.202     1924371.419      421620.105
     1924240.594      420704.334
#Sta/Elev= 30
       0  229.82   62.67  228.75   108.7  228.75  135.65  227.92  273.84  225.73
  367.89  224.99  394.32  223.89  402.11  222.91  408.62  222.88  430.19  221.17
  451.96  221.54  484.28  220.91  514.76   221.6  574.51  220.71  633.88  221.38
  651.66  220.84     710  221.07  757.62  220.63  801.15  221.37  846.61  220.87
  850.82  220.27   882.8  220.24   949.8  219.94  972.08  220.53 1028.46  220.31
 1041.99  222.68 1054.82  222.79 1079.83   224.2 1216.49  227.06 1340.47  230.45
#Mann= 3 , 0 , 0
       0     .13       0  850.82    .055       0   882.8     .13       0
Bank Sta=850.82,882.8
XS Rating Curve= 0
Exp/Cntr=.3,.1

Type RM Length L Ch R = 1 ,7995.133,1743.93,1695.78,1657.42
XS GIS Cut Line= 4
     1925775.583       421623.52     1925828.147      421203.008
     1925761.247      420266.413     1925665.676       420080.05
#Sta/Elev= 30
       0  231.92   173.5  226.89  318.63  223.56  607.38  218.96  633.61  216.37
  726.32  216.04  756.79  216.66  840.04   216.7  852.66  216.37  870.37  216.93
  886.75  216.76   909.8  217.47    1028  216.85 1050.09  217.98 1127.67  217.04
 1155.47   218.5 1188.28  217.68 1212.07  218.26 1235.09  220.39 1239.66  221.47
  1255.2  221.79 1273.77  223.16 1282.09  222.17 1343.44  223.18  1375.2  224.32
 1445.76  224.09 1463.91  225.05 1522.01   225.1  1532.4  225.79 1572.21  226.26
#Mann= 3 , 0 , 0
       0     .13       0  840.04    .055       0  870.37     .13       0
Bank Sta=840.04,870.37
XS Rating Curve= 0
Exp/Cntr=.3,.1

Type RM Length L Ch R = 1 ,6299.352,1402.95,1528.67,1425.52
XS GIS Cut Line= 4
     1927648.571       421430.41     1927602.783      421194.926
     1927485.041      420678.169     1927295.345      420331.485
#Sta/Elev= 30
       0   223.8   98.46  220.79  151.01   218.1  196.22  217.14  262.66   212.1
  284.94  212.93  404.46  212.73  414.41  214.07  450.73  213.15  456.71  213.32
  478.04  216.76  490.45  217.34  507.07  217.19  510.39  215.42  513.37  214.89
  546.35   214.9  555.65  216.79  585.67  217.98  611.94  215.04  655.69  215.89
  672.68  213.31  692.15  214.69  714.13  213.77   765.9  214.73  779.85  213.27
  797.12  212.12  809.46  213.27  835.58  217.97  983.34  219.05 1165.08  221.68
#Mann= 3 , 0 , 0
       0     .13       0  779.85    .055       0  809.46     .13       0
Bank Sta=779.85,809.46
XS Rating Curve= 0
Exp/Cntr=.3,.1

Type RM Length L Ch R = 1 ,4770.686,1393.77,1389.75,1311.83
XS GIS Cut Line= 3
     1928948.537      420658.254     1928814.738      420414.548
     1928690.496        419912.8
#Sta/Elev= 30
       0   223.9   71.87  222.52  108.75  222.78  123.66  220.85  153.84  219.22
  203.33  215.15  211.01  214.84  234.73  212.36  239.44  211.59  274.23  210.46
  278.02  209.88  284.51  208.13  298.66  208.02  300.98  209.26   312.6  210.56
  336.07  210.77  340.37  209.25     344208.7184  349.93  207.85  369.78  207.56
  394.24   208.2  465.15  207.86   571.4  209.11  593.39  208.65  626.31  209.17
  672.29  212.91  698.78  213.78  731.59  216.11  760.91  217.35  794.92  218.19
#Mann= 3 , 0 , 0
       0     .13       0     344    .055       0  394.24     .13       0
Bank Sta=344,394.24
XS Rating Curve= 0
Exp/Cntr=.3,.1

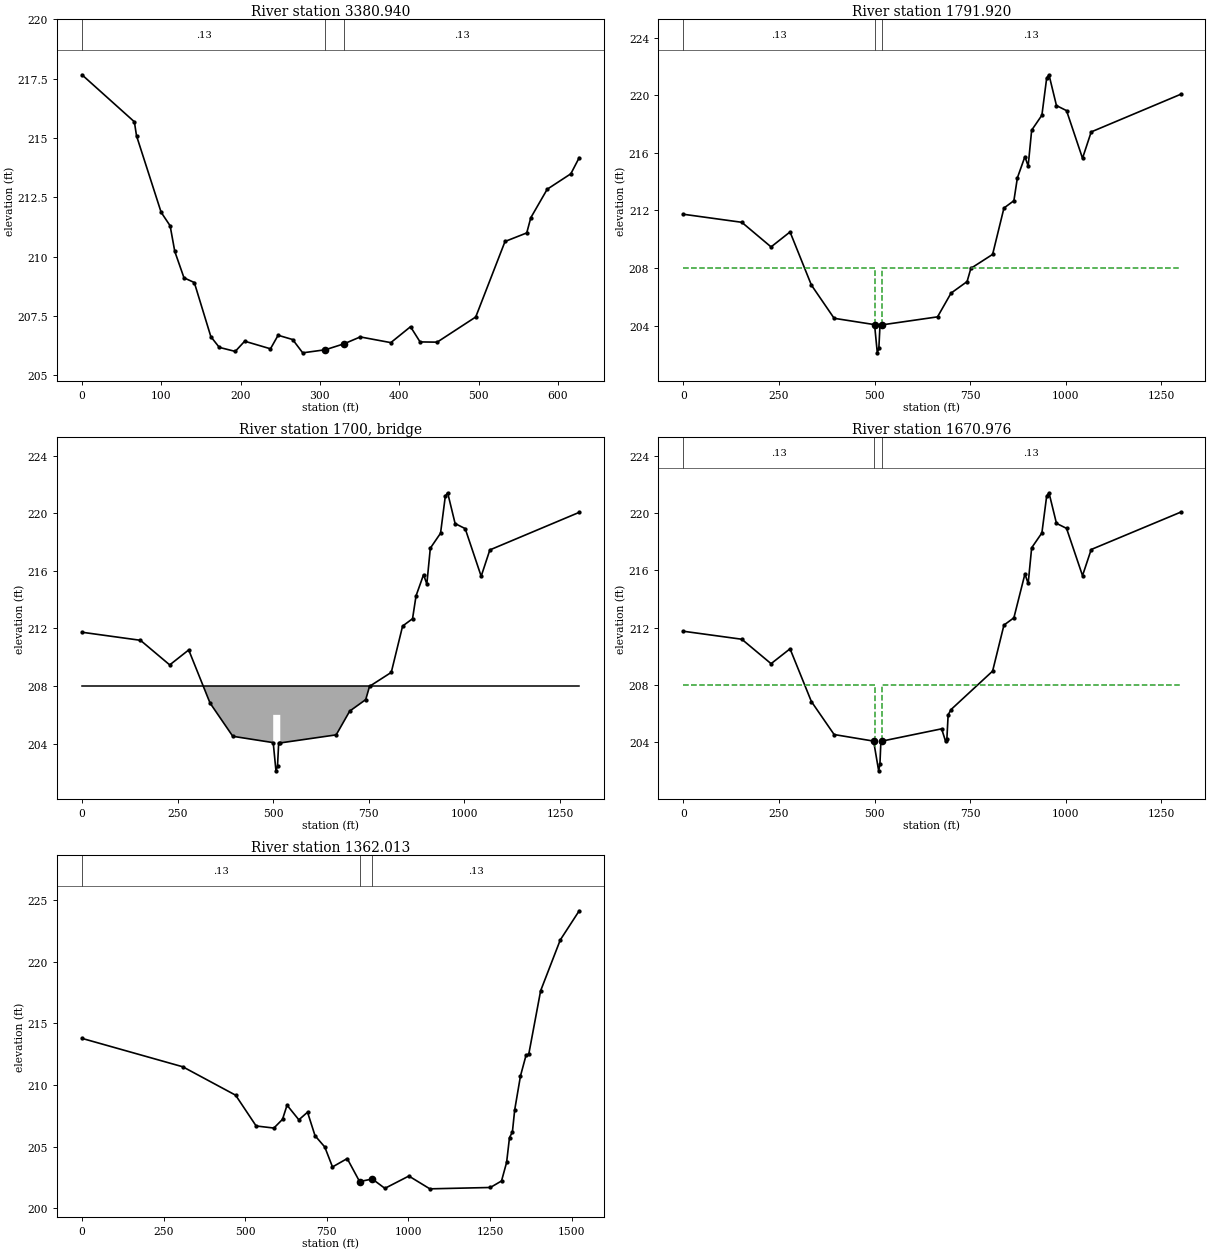
Type RM Length L Ch R = 1 ,3380.940,1464.33,1589.02,1716.02
XS GIS Cut Line= 3
     1930153.729      419952.617     1929889.987       419521.42
     1929806.259      419433.506
#Sta/Elev= 30
       0  217.66   66.06  215.68   68.78  215.09    99.8  211.87  111.15   211.3
  117.01  210.22  128.61  209.11  141.64  208.91   162.5  206.63  173.12  206.18
  193.24  206.01  205.13  206.44  237.63  206.12  247.28  206.69  265.61  206.51
   278.3  205.95   306.8  206.08  330.36  206.33  350.84  206.62  389.37  206.38
  414.19  207.05  426.26  206.41  447.79   206.4  496.42  207.46  533.35  210.64
  560.71     211  565.83  211.64  586.52  212.84   616.3  213.49  626.87  214.17
#Mann= 3 , 0 , 0
       0     .13       0   306.8    .055       0  330.36     .13       0
Bank Sta=306.8,330.36
XS Rating Curve= 0
Exp/Cntr=.5,.3

Type RM Length L Ch R = 1 ,1791.920,125.13,120.94,111.9
XS GIS Cut Line= 4
     1931133.342      420254.037      1931355.22      420032.158
     1931531.048      419538.165     1931644.081      419090.222
#Sta/Elev= 30
       0  211.74  152.93  211.18  229.46  209.47  279.08  210.51  334.87  206.82
  394.36  204.51  500.05  204.07  507.23  202.11  511.26  202.43  514.27  204.01
  518.62  204.05   664.7  204.61  700.07  206.26  741.95  207.06  751.89  207.98
  808.71  208.95  838.35  212.17  864.34  212.68   873.5  214.27  893.15  215.74
  901.69  215.09  910.82  217.58  937.56  218.62  950.12  221.21  956.12  221.43
  975.66  219.29 1001.99  218.94 1043.79  215.63 1066.49  217.46 1300.12  220.07
#Mann= 3 , 0 , 0
       0     .13       0  500.05    .055       0  518.62     .13       0
#XS Ineff= 2 , 0
       0     500     208   518.5       0     208
Permanent Ineff=
       F       F
Bank Sta=500.05,518.62
XS Rating Curve= 0
Exp/Cntr=.5,.3

Type RM Length L Ch R = 3 ,1700    ,,,
BEGIN DESCRIPTION:
SR1134; No. 96 from NCDOT database
END DESCRIPTION:
Bridge Culvert--1,0,-1,-1, 0
Deck Dist Width WeirC Skew NumUp NumDn MinLoCord MaxHiCord MaxSubmerge Is_Ogee
47.3,29.3,2.6,0, 7, 7, , , .95, 0, 1.5,1.5,,
       0  494.13  497.61     500   518.5  518.75 1300.12
     208     208     208     208     208     208     208
                             206     206
       0  494.13  497.61     500   518.5  518.75 1300.12
     208     208     208     208     208     208     208
                             206     206
BR Coef=-1 , 1 , 0 ,, 0 ,,,.8,0,1.2,1,
WSPro=,,,, 1 ,,,, 0 ,,,, 0 ,,,,-1 ,-1 ,-1 , 0 , 0 , 0 , 0 , 0
BC Design=,, 0 ,, 0 ,,,,,,

Type RM Length L Ch R = 1 ,1670.976,299.62,308.96,331.3
XS GIS Cut Line= 5
 1931241.7568271   420295.822505     1931464.066      420107.513
 1931657.5136529   419477.779737 1931708.9018836  419310.4948012
 1931760.2901143  419143.2098654
#Sta/Elev= 30
       0  211.74  152.93  211.18  229.46  209.47  279.08  210.51  334.87  206.82
  394.36  204.51  497.61  204.05   510.8  201.97   514.1  202.44   516.6  204.02
  519.26  204.05  675.44  204.91  685.58  204.05  689.16  204.22  692.47  205.89
  700.07  206.26  808.71  208.95  838.35  212.17  864.34  212.68  893.15  215.74
  901.69  215.09  910.82  217.58  937.56  218.62  950.12  221.21  956.12  221.43
  975.66  219.29 1001.99  218.94 1043.79  215.63 1066.49  217.46 1300.12  220.07
#Mann= 3 , 0 , 0
       0     .13       0  497.61    .055       0  519.26     .13       0
#XS Ineff= 2 , 0
       0     500     208   518.5       0     208
Permanent Ineff=
       F       F
Bank Sta=497.61,519.26
XS Rating Curve= 0
Exp/Cntr=.5,.3

Type RM Length L Ch R = 1 ,1362.013,0,0,0
XS GIS Cut Line= 5
      1931198.97       420543.82     1931648.445      420300.354
     1931704.629      420272.262     1931976.187      419588.686
     1931920.002      419382.677
#Sta/Elev= 30
       0  213.79   308.8  211.48  470.72  209.17  533.48  206.67  587.85   206.5
  614.25  207.21  628.17  208.36  664.33  207.17  690.91  207.79  713.86  205.88
  743.76  204.96  767.35  203.34  812.45  204.02  850.41  202.15  889.28  202.36
  927.85   201.6 1001.26   202.6 1065.58  201.56 1250.92  201.67  1285.1   202.2
 1300.69  203.71 1309.54  205.73 1318.38  206.17 1325.41  207.97  1343.2  210.74
 1360.23  212.42 1368.52   212.5 1404.91  217.66 1465.06  221.79 1523.07  224.16
#Mann= 3 , 0 , 0
       0     .13       0  850.41    .055       0  889.28     .13       0
Bank Sta=850.41,889.28
XS Rating Curve= 0
Exp/Cntr=.3,.1

River Reach=Raft Swamp      ,six
Reach XY= 30
      1933113.06      420140.871     1933139.274      420133.492
      1933169.14       420106.41      1933222.54       420088.61
      1933413.01       420069.56      1933527.29       420040.99
      1933727.28       419964.81      1933803.47       419860.05
      1933946.32       419755.29      1934403.44       419488.64
      1934527.25       419460.07      1934593.91       419355.31
      1934584.39       419079.13      1934593.91       419012.47
      1934641.53       418926.76        1934632.       418622.01
      1934651.05       418517.26      1934689.14       418460.12
      1934803.42        418412.5      1934870.09       418345.83
      1934936.75       418202.98      1935003.41       418107.75
       1935079.6       418050.61      1935308.16       417974.42
       1935403.4       417869.67      1935441.49       417812.53
      1935498.01       417803.11     1935527.721      417787.338
     1935579.294      417771.102     1935686.983      417642.269

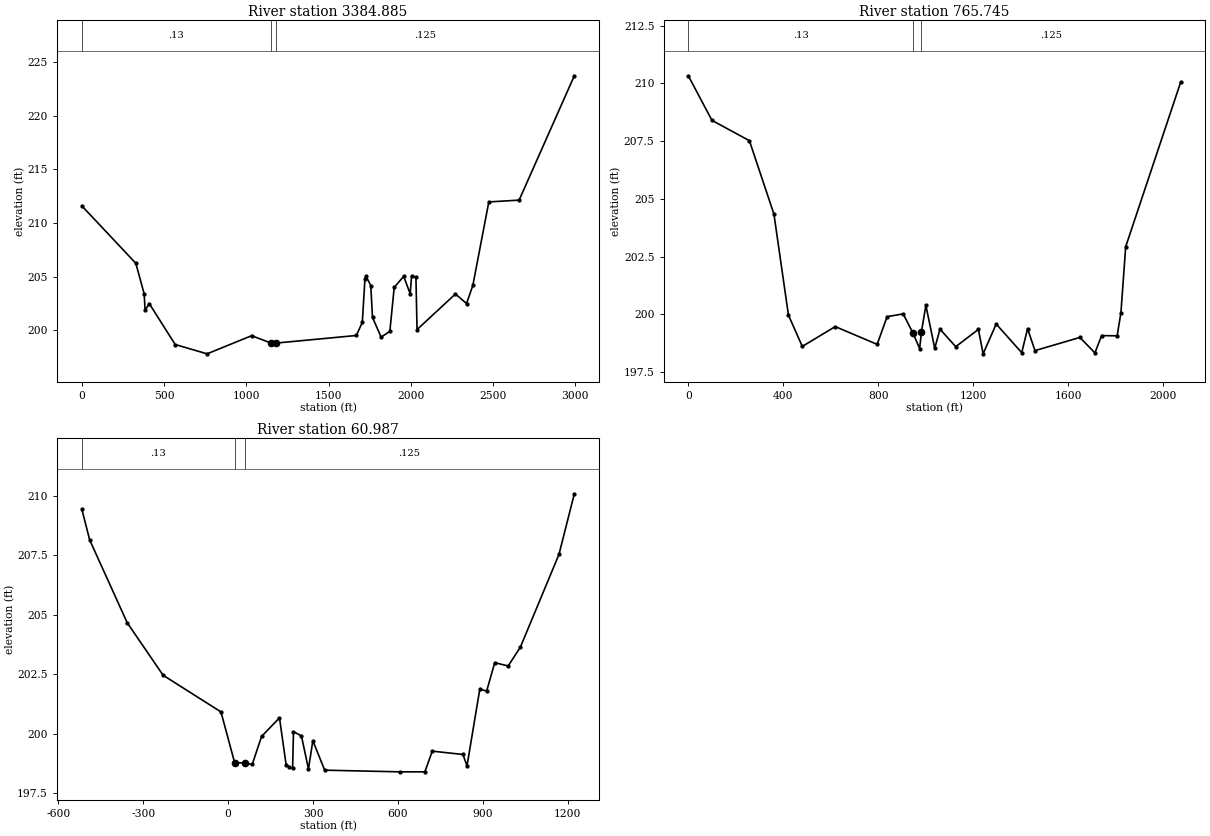
Type RM Length L Ch R = 1 ,3384.885,2483.27,2619.14,2527.97
XS GIS Cut Line= 4
     1934598.122      420712.373     1934158.012      420478.271
     1932828.316      418998.751     1932350.749      418830.198
#Sta/Elev= 30
       0  211.59  328.29  206.24  379.07  203.38   384.5  201.84  409.71  202.49
  567.51  198.67   761.3   197.8    1032  199.49 1149.83  198.81 1178.22   198.8
 1668.79  199.51 1705.21  200.73 1721.33  204.82 1728.45  205.02 1756.41  204.17
 1767.13  201.19 1819.38  199.36 1872.49  199.89 1899.17     204 1956.68  205.02
 1996.22   203.4 2005.03  205.09 2031.17  204.93 2037.89  200.06 2271.31  203.38
 2338.86  202.49  2377.2  204.18 2474.26  211.96 2658.57  212.13 2994.18  223.72
#Mann= 3 , 0 , 0
       0     .13       0 1149.83     .05       0 1178.22    .125       0
Bank Sta=1149.83,1178.22
XS Rating Curve= 0
Exp/Cntr=.3,.1

Type RM Length L Ch R = 1 ,765.745 ,673.57,704.89,711.85
XS GIS Cut Line= 4
     1935689.784      418803.978     1935450.064      418450.392
     1934495.118      417425.589     1934251.652      417397.497
#Sta/Elev= 30
       0  210.33   99.43   208.4  257.08  207.52   360.4  204.34  421.44  199.97
  479.68  198.61   618.5  199.47  794.93   198.7  836.68   199.9   904.6  200.02
  945.06   199.2   973.7  198.52  981.45  199.25  999.97  200.39  1037.3  198.53
 1059.32  199.36 1125.73   198.6 1221.13  199.35  1240.9  198.29 1296.04  199.58
 1403.49  198.34 1428.03  199.38 1459.26  198.43 1648.33     199 1711.62  198.33
 1739.69  199.08 1805.11  199.07 1821.01  200.07 1841.11  202.93 2073.03  210.07
#Mann= 3 , 0 , 0
       0     .13       0  945.06     .05       0  981.45    .125       0
Bank Sta=945.06,981.45
XS Rating Curve= 0
Exp/Cntr=.3,.1

Type RM Length L Ch R = 1 ,60.987  ,0,0,0
XS GIS Cut Line= 5
 1935979.6782533  418124.8787906 1935812.0251485  417904.6399537
      1935666.45      417713.404     1935162.334      417051.168
     1934831.908      416841.475
#Sta/Elev= 30
 -517.13  209.44  -489.5  208.15 -356.91  204.67 -229.83  202.46  -25.41  200.92
   22.78  198.79   58.18  198.77   85.08  198.71   118.2  199.89  181.48  200.67
  204.83   198.7  216.84  198.59  227.86  198.56  230.95  200.09  259.07  199.91
  283.88  198.52  299.35  199.71  341.17  198.47  607.73   198.4  695.35   198.4
  721.46  199.27  829.98  199.13  844.27  198.65   889.4  201.87  913.84   201.8
  942.35  202.99  989.79  202.85 1032.84  203.64 1169.32  207.54 1223.63  210.09
#Mann= 3 , 0 , 0
 -517.13     .13       0   22.78     .05       0   58.18    .125       0
Bank Sta=22.78,58.18
XS Rating Curve= 0
Exp/Cntr=.3,.1

Chan Stop Cuts=-1